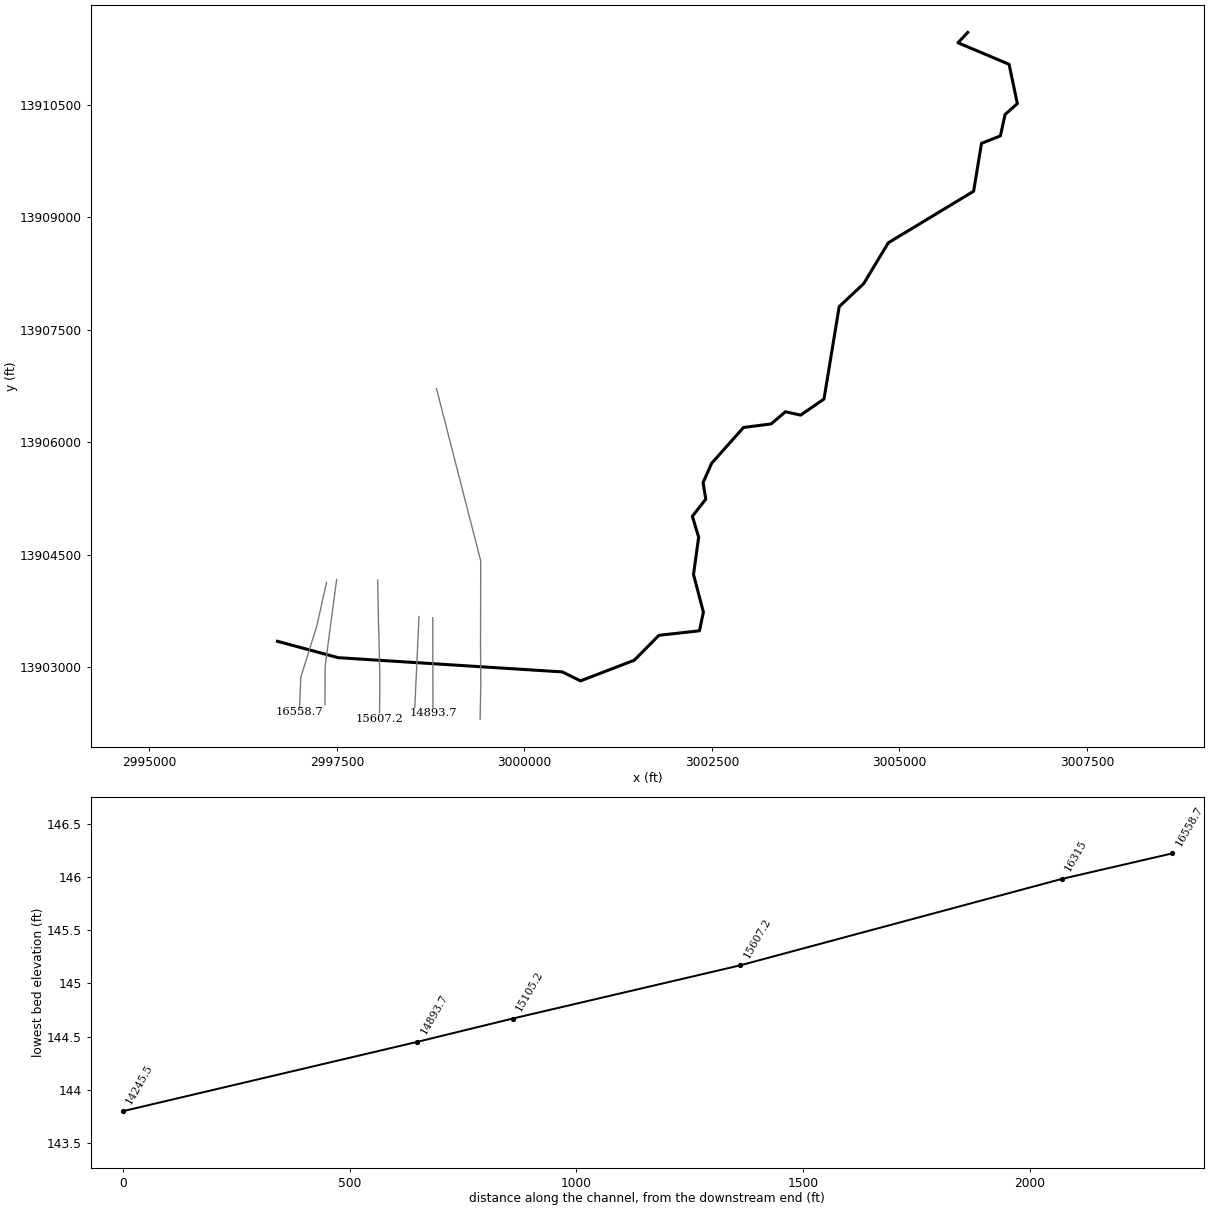
--- K150-00-00.prj (project) ---

Proj Title=K150-00-00
Current Plan=p01
Default Exp/Contr=.3,.1
English Units
Geom File=g01
Flow File=f01
Flow File=f02
Plan File=p01
Plan File=p02
Y Axis Title=Elevation
X Axis Title(PF)=Main Channel Distance
X Axis Title(XS)=Station
BEGIN DESCRIPTION:
HCFCD MODEL SUMMARY METADATA
The purpose of this summary is to document the high points of hydrologic and hydraulic models filed within the HCFCD Model and Map Management (M3) system.  The document includes references to the project that prompted the creation or update of the model.
DESCRIPTION OF PROJECT:
The following model was the hydraulic model which represented the effective condition of Harris County's watersheds.
PURPOSE OF PROJECT:
Development of effective models to support the National Flood Insurance Program.
HCFCD Watershed Unit ID: K
M3 Study Identifier: 2007_Effective_K
Engineer: HCFCD
Project Name: EffectiveFEMA Study for watershed Cypress Creek (K)
Study Completion Date: 6/18/2007
FEMA Case Number: [No Data]
FEMA Approval Date: [No Date in Database]
Vertical Datum: NAVD 1988
Datum Note: 2001 ADJ
HYDRAULICS
HCFCD Unit No.:  K150-00-00 & K150-00-01
Hydraulic Program Name: HEC-RAS
Hydraulic Program Version: 3.0.1
Steady Hydraulic Model: Yes
Unsteady Hydraulic Model: No
Update 1: The effective FEMA hydraulic model for unit number K150-00-00 has been updated by FEMA LOMR 07-06-01885P with an effective date of 11/28/2008.
Update 2: The effective FEMA hydraulic model for unit number K150-00-00 has been updated by FEMA LOMR 16-06-0557P with an effective date of 11/4/2016.
Update 3: The effective FEMA hydraulic model for unit number K150-00-00 has been updated by FEMA LOMR 17-06-0430X with an effective date of 8/14/2017.
END DESCRIPTION:
DSS Export Rating Curves= 0
DSS Export Rating Curve Sorted= 0
DSS Export Volume Flow Curves= 0
DXF Filename=k15001.dxf
DXF OffsetX= 0
DXF OffsetY= 0
DXF ScaleX= 1
DXF ScaleY= 1

--- K150-00-00.p01 (plan) ---

Plan Title=FEMA Effective Multi-Profile 2017
Version=Version 3.0.1  May 2012
Short Identifier=K150_MP
Simulation Date=01JAN1983,1200,03JAN1983,2200
Geom File=g01
Flow File=f01
Subcritical Flow
K Sum by GR= 0
Std Step Tol= 0.005
Critical Tol= 0.01
Num of Std Step Trials= 20
Max Error Tol= 0.3
Flow Tol Ratio= 0.001
Split Flow NTrial= 30
Split Flow Tol= 0.02
Split Flow Ratio= 0.02
Log Output Level= 0
Friction Slope Method= 1
Unsteady Friction Slope Method= 2
Secant Critical Depth
Global Vel Dist= 0 , 0 , 0
Global Log Level= 0
CheckData=True
Encroach Param=-1 ,0,0, 0
BEGIN DESCRIPTION:
FEMA Effective Multi-Profile June 2007 + LOMR 07-06-1885P + LOMR 16-06-0557P + 17-06-0430X
END DESCRIPTION:
Computation Interval=10SEC
Output Interval=15MIN
Run HTab= 1
Run UNet= 1
Run PostProcess= 1
UNET Theta= 1
UNET ZTol= 0.005
UNET ZSATol= 0.05
UNET MxIter= 40
UNET MaxInSteps= 200
UNET DtIC= 0
UNET DtMin= 0
UNET MaxCRTS= 40
UNET WFStab= 2
UNET SFStab= 1
UNET WFX= 1
UNET SFX= 1
UNET Convert EG Bridges= 0
UNET Use Existing IB Tables=-1
Instantaneous Interval=4HOUR
DSS File=dss
Write IC File= 0
IC Time=0
Write Velocity= 0
Write Detailed= 0
Stage Flow Hydrograph=K100-00-00      ,US K150 Div     ,274030
Stage Flow Hydrograph=K100-00-00      ,US K150 Div     ,272601
Stage Flow Hydrograph=K100-00-00      ,US K150 Div     ,271395
Stage Flow Hydrograph=K100-00-00      ,US K150 Div     ,270356
Stage Flow Hydrograph=K100-00-00      ,US K150 Div     ,269458
Stage Flow Hydrograph=K100-00-00      ,US K150 Div     ,268288
Stage Flow Hydrograph=K100-00-00      ,US K150 Div     ,266491
Stage Flow Hydrograph=K100-00-00      ,US K150 Div     ,266161.
Stage Flow Hydrograph=K100-00-00      ,US K150 Div     ,266065
Stage Flow Hydrograph=K100-00-00      ,US K150 Div     ,266005
Stage Flow Hydrograph=K100-00-00      ,US K150 Div     ,265916.
Stage Flow Hydrograph=K100-00-00      ,US K150 Div     ,265696
Stage Flow Hydrograph=K100-00-00      ,US K150 Div     ,264165
Stage Flow Hydrograph=K100-00-00      ,US K150 Div     ,262916
Stage Flow Hydrograph=K100-00-00      ,US K150 Div     ,262434
Stage Flow Hydrograph=K100-00-00      ,US K150 Div     ,260447
Stage Flow Hydrograph=K100-00-00      ,US K150 Div     ,259337
Stage Flow Hydrograph=K100-00-00      ,US K150 Div     ,257633
Stage Flow Hydrograph=K100-00-00      ,US K150 Div     ,256348
Stage Flow Hydrograph=K100-00-00      ,US K150 Div     ,255599
Stage Flow Hydrograph=K100-00-00      ,US K150 Div     ,254087
Stage Flow Hydrograph=K100-00-00      ,US K150 Div     ,252373
Stage Flow Hydrograph=K100-00-00      ,US K150 Div     ,251646.
Stage Flow Hydrograph=K100-00-00      ,US K150 Div     ,251527
Stage Flow Hydrograph=K100-00-00      ,US K150 Div     ,251475
Stage Flow Hydrograph=K100-00-00      ,US K150 Div     ,251450
Stage Flow Hydrograph=K100-00-00      ,US K150 Div     ,251429
Stage Flow Hydrograph=K100-00-00      ,US K150 Div     ,251335
Stage Flow Hydrograph=K100-00-00      ,US K150 Div     ,250102
Stage Flow Hydrograph=K100-00-00      ,US K150 Div     ,249192
Stage Flow Hydrograph=K100-00-00      ,US K150 Div     ,248048
Stage Flow Hydrograph=K100-00-00      ,US K150 Div     ,247215
Stage Flow Hydrograph=K100-00-00      ,US K150 Div     ,245509
Stage Flow Hydrograph=K100-00-00      ,US K150 Div     ,245355.
Stage Flow Hydrograph=K100-00-00      ,US K150 Div     ,245276
Stage Flow Hydrograph=K100-00-00      ,US K150 Div     ,245253
Stage Flow Hydrograph=K100-00-00      ,US K150 Div     ,245155.
Stage Flow Hydrograph=K100-00-00      ,US K150 Div     ,244597
Stage Flow Hydrograph=K100-00-00      ,US K150 Div     ,243570
Stage Flow Hydrograph=K100-00-00      ,US K150 Div     ,242425
Stage Flow Hydrograph=K100-00-00      ,US K150 Div     ,240447
Stage Flow Hydrograph=K100-00-00      ,US K150 Div     ,240049.
Stage Flow Hydrograph=K100-00-00      ,US K150 Div     ,239947
Stage Flow Hydrograph=K100-00-00      ,US K150 Div     ,239899
Stage Flow Hydrograph=K100-00-00      ,US K150 Div     ,239803.
Stage Flow Hydrograph=K100-00-00      ,US K150 Div     ,238992
Stage Flow Hydrograph=K100-00-00      ,US K150 Div     ,237222
Stage Flow Hydrograph=K100-00-00      ,US K150 Div     ,236252
Stage Flow Hydrograph=K100-00-00      ,US K150 Div     ,234886
Stage Flow Hydrograph=K100-00-00      ,US K150 Div     ,234132
Stage Flow Hydrograph=K100-00-00      ,US K150 Div     ,233592
Stage Flow Hydrograph=K100-00-00      ,US K150 Div     ,232118
Stage Flow Hydrograph=K100-00-00      ,US K150 Div     ,230913
Stage Flow Hydrograph=K100-00-00      ,US K150 Div     ,229343
Stage Flow Hydrograph=K100-00-00      ,US K150 Div     ,228591
Stage Flow Hydrograph=K100-00-00      ,US K150 Div     ,226696
Stage Flow Hydrograph=K100-00-00      ,US K150 Div     ,225959
Stage Flow Hydrograph=K100-00-00      ,US K150 Div     ,224004
Stage Flow Hydrograph=K100-00-00      ,US K150 Div     ,222338
Stage Flow Hydrograph=K100-00-00      ,US K150 Div     ,222073.
Stage Flow Hydrograph=K100-00-00      ,US K150 Div     ,221973
Stage Flow Hydrograph=K100-00-00      ,US K150 Div     ,221911
Stage Flow Hydrograph=K100-00-00      ,US K150 Div     ,221811.
Stage Flow Hydrograph=K100-00-00      ,US K150 Div     ,221801
Stage Flow Hydrograph=K100-00-00      ,US K150 Div     ,221068
Stage Flow Hydrograph=K100-00-00      ,US K150 Div     ,219947
Stage Flow Hydrograph=K100-00-00      ,US K150 Div     ,219081
Stage Flow Hydrograph=K100-00-00      ,US K150 Div     ,217788
Stage Flow Hydrograph=K100-00-00      ,US K150 Div     ,216172
Stage Flow Hydrograph=K100-00-00      ,US K150 Div     ,214318
Stage Flow Hydrograph=K100-00-00      ,US K150 Div     ,213508
Stage Flow Hydrograph=K100-00-00      ,US K150 Div     ,211854
Stage Flow Hydrograph=K100-00-00      ,US K150 Div     ,210086
Stage Flow Hydrograph=K100-00-00      ,US K150 Div     ,209229
Stage Flow Hydrograph=K100-00-00      ,US K150 Div     ,207906
Stage Flow Hydrograph=K100-00-00      ,US K150 Div     ,206984
Stage Flow Hydrograph=K100-00-00      ,US K150 Div     ,205406
Stage Flow Hydrograph=K100-00-00      ,US K150 Div     ,204585
Stage Flow Hydrograph=K100-00-00      ,US K150 Div     ,203403
Stage Flow Hydrograph=K100-00-00      ,US K150 Div     ,202422
Stage Flow Hydrograph=K100-00-00      ,US K150 Div     ,201289
Stage Flow Hydrograph=K100-00-00      ,US K150 Div     ,200580
Stage Flow Hydrograph=K100-00-00      ,US K150 Div     ,199171
Stage Flow Hydrograph=K100-00-00      ,US K150 Div     ,197996
Stage Flow Hydrograph=K100-00-00      ,US K150 Div     ,196391
Stage Flow Hydrograph=K100-00-00      ,US K150 Div     ,195672
Stage Flow Hydrograph=K100-00-00      ,US K150 Div     ,194416
Stage Flow Hydrograph=K100-00-00      ,US K150 Div     ,194075
Stage Flow Hydrograph=K100-00-00      ,US K150 Div     ,193386
Stage Flow Hydrograph=K100-00-00      ,DS K150 Div     ,191951
Stage Flow Hydrograph=K100-00-00      ,DS K150 Div     ,190807
Stage Flow Hydrograph=K100-00-00      ,DS K150 Div     ,190457.
Stage Flow Hydrograph=K100-00-00      ,DS K150 Div     ,190362
Stage Flow Hydrograph=K100-00-00      ,DS K150 Div     ,190317
Stage Flow Hydrograph=K100-00-00      ,DS K150 Div     ,190211.
Stage Flow Hydrograph=K100-00-00      ,DS K150 Div     ,189564
Stage Flow Hydrograph=K100-00-00      ,DS K150         ,187983
Stage Flow Hydrograph=K100-00-00      ,DS K150         ,186937
Stage Flow Hydrograph=K100-00-00      ,DS K150         ,185713
Stage Flow Hydrograph=K100-00-00      ,DS K150         ,185488.
Stage Flow Hydrograph=K100-00-00      ,DS K150         ,185278
Stage Flow Hydrograph=K100-00-00      ,DS K150         ,185222
Stage Flow Hydrograph=K100-00-00      ,DS K150         ,185028.
Stage Flow Hydrograph=K100-00-00      ,DS K150         ,184753
Stage Flow Hydrograph=K100-00-00      ,DS K150         ,183827
Stage Flow Hydrograph=K100-00-00      ,DS K150         ,182368
Stage Flow Hydrograph=K100-00-00      ,DS K150         ,180551
Stage Flow Hydrograph=K100-00-00      ,DS K150         ,178635
Stage Flow Hydrograph=K100-00-00      ,DS K150         ,176773
Stage Flow Hydrograph=K100-00-00      ,DS K150         ,175264
Stage Flow Hydrograph=K100-00-00      ,DS K150         ,174850.
Stage Flow Hydrograph=K100-00-00      ,DS K150         ,174737
Stage Flow Hydrograph=K100-00-00      ,DS K150         ,174712
Stage Flow Hydrograph=K100-00-00      ,DS K150         ,174645
Stage Flow Hydrograph=K100-00-00      ,DS K150         ,174614
Stage Flow Hydrograph=K100-00-00      ,DS K150         ,174515
Stage Flow Hydrograph=K100-00-00      ,DS K150         ,174446
Stage Flow Hydrograph=K100-00-00      ,DS K150         ,174414
Stage Flow Hydrograph=K100-00-00      ,DS K150         ,174181
Stage Flow Hydrograph=K100-00-00      ,DS K150         ,174160
Stage Flow Hydrograph=K100-00-00      ,DS K150         ,174137
Stage Flow Hydrograph=K100-00-00      ,DS K150         ,173866.
Stage Flow Hydrograph=K100-00-00      ,DS K150         ,173590
Stage Flow Hydrograph=K100-00-00      ,DS K150         ,172338
Stage Flow Hydrograph=K100-00-00      ,DS K150         ,170765
Stage Flow Hydrograph=K100-00-00      ,DS K150         ,170585
Stage Flow Hydrograph=K100-00-00      ,DS K150         ,170526
Stage Flow Hydrograph=K100-00-00      ,DS K150         ,170401.
Stage Flow Hydrograph=K100-00-00      ,DS K150         ,170004
Stage Flow Hydrograph=K100-00-00      ,DS K150         ,168614
Stage Flow Hydrograph=K100-00-00      ,DS K150         ,167592
Stage Flow Hydrograph=K100-00-00      ,DS K150         ,166998
Stage Flow Hydrograph=K100-00-00      ,DS K150         ,166479
Stage Flow Hydrograph=K100-00-00      ,DS K150         ,164989
Stage Flow Hydrograph=K100-00-00      ,DS K150         ,163957
Stage Flow Hydrograph=K100-00-00      ,DS K150         ,162447
Stage Flow Hydrograph=K100-00-00      ,DS K150         ,160778
Stage Flow Hydrograph=K100-00-00      ,DS K150         ,160351.
Stage Flow Hydrograph=K100-00-00      ,DS K150         ,160245
Stage Flow Hydrograph=K100-00-00      ,DS K150         ,160148
Stage Flow Hydrograph=K100-00-00      ,DS K150         ,160042.
Stage Flow Hydrograph=K100-00-00      ,DS K150         ,159764
Stage Flow Hydrograph=K100-00-00      ,DS K150         ,158469
Stage Flow Hydrograph=K100-00-00      ,DS K150         ,156881
Stage Flow Hydrograph=K100-00-00      ,DS K150         ,155825
Stage Flow Hydrograph=K100-00-00      ,DS K150         ,154677
Stage Flow Hydrograph=K100-00-00      ,DS K150         ,153727
Stage Flow Hydrograph=K100-00-00      ,DS K150         ,152335
Stage Flow Hydrograph=K100-00-00      ,DS K150         ,151314.
Stage Flow Hydrograph=K100-00-00      ,DS K150         ,151214
Stage Flow Hydrograph=K100-00-00      ,DS K150         ,151153
Stage Flow Hydrograph=K100-00-00      ,DS K150         ,151057.
Stage Flow Hydrograph=K100-00-00      ,DS K150         ,149704
Stage Flow Hydrograph=K100-00-00      ,DS K150         ,149014
Stage Flow Hydrograph=K100-00-00      ,DS K150         ,148434
Stage Flow Hydrograph=K100-00-00      ,DS K150         ,147865
Stage Flow Hydrograph=K100-00-00      ,DS K150         ,146710
Stage Flow Hydrograph=K100-00-00      ,DS K150         ,145901
Stage Flow Hydrograph=K100-00-00      ,DS K150         ,144516
Stage Flow Hydrograph=K100-00-00      ,DS K150         ,143628
Stage Flow Hydrograph=K100-00-00      ,DS K150         ,142175
Stage Flow Hydrograph=K100-00-00      ,DS K150         ,141381
Stage Flow Hydrograph=K100-00-00      ,DS K150         ,140143
Stage Flow Hydrograph=K100-00-00      ,DS K150         ,139166
Stage Flow Hydrograph=K100-00-00      ,DS K150         ,138523.
Stage Flow Hydrograph=K100-00-00      ,DS K150         ,138420
Stage Flow Hydrograph=K100-00-00      ,DS K150         ,138363
Stage Flow Hydrograph=K100-00-00      ,DS K150         ,138264.
Stage Flow Hydrograph=K100-00-00      ,DS K150         ,137950
Stage Flow Hydrograph=K100-00-00      ,DS K150         ,135966
Stage Flow Hydrograph=K100-00-00      ,DS K150         ,134226
Stage Flow Hydrograph=K100-00-00      ,DS K150         ,134004.
Stage Flow Hydrograph=K100-00-00      ,DS K150         ,133905
Stage Flow Hydrograph=K100-00-00      ,DS K150         ,133844
Stage Flow Hydrograph=K100-00-00      ,DS K150         ,133720.
Stage Flow Hydrograph=K100-00-00      ,DS K150         ,133259
Stage Flow Hydrograph=K100-00-00      ,DS K150         ,131653
Stage Flow Hydrograph=K100-00-00      ,DS K150         ,130112
Stage Flow Hydrograph=K100-00-00      ,DS K150         ,128649
Stage Flow Hydrograph=K100-00-00      ,DS K150         ,127383.
Stage Flow Hydrograph=K100-00-00      ,DS K150         ,127187
Stage Flow Hydrograph=K100-00-00      ,DS K150         ,127079
Stage Flow Hydrograph=K100-00-00      ,DS K150         ,126877.
Stage Flow Hydrograph=K100-00-00      ,DS K150         ,125669
Stage Flow Hydrograph=K100-00-00      ,DS K150         ,124910.
Stage Flow Hydrograph=K100-00-00      ,DS K150         ,124810
Stage Flow Hydrograph=K100-00-00      ,DS K150         ,124694
Stage Flow Hydrograph=K100-00-00      ,DS K150         ,124593.
Stage Flow Hydrograph=K100-00-00      ,DS K150         ,124097
Stage Flow Hydrograph=K100-00-00      ,DS K150         ,123437.
Stage Flow Hydrograph=K100-00-00      ,DS K150         ,123344
Stage Flow Hydrograph=K100-00-00      ,DS K150         ,123316
Stage Flow Hydrograph=K100-00-00      ,DS K150         ,123212.
Stage Flow Hydrograph=K100-00-00      ,DS K150         ,122086
Stage Flow Hydrograph=K100-00-00      ,DS K150         ,120997
Stage Flow Hydrograph=K100-00-00      ,DS K150         ,119576
Stage Flow Hydrograph=K100-00-00      ,DS K150         ,118501.
Stage Flow Hydrograph=K100-00-00      ,DS K150         ,118399
Stage Flow Hydrograph=K100-00-00      ,DS K150         ,118064
Stage Flow Hydrograph=K100-00-00      ,DS K150         ,117950.
Stage Flow Hydrograph=K100-00-00      ,DS K150         ,116864
Stage Flow Hydrograph=K100-00-00      ,DS K150         ,115085
Stage Flow Hydrograph=K100-00-00      ,DS K150         ,113128
Stage Flow Hydrograph=K100-00-00      ,DS K150         ,111804
Stage Flow Hydrograph=K100-00-00      ,DS K150         ,111533.
Stage Flow Hydrograph=K100-00-00      ,DS K150         ,111378
Stage Flow Hydrograph=K100-00-00      ,DS K150         ,111284
Stage Flow Hydrograph=K100-00-00      ,DS K150         ,111078.
Stage Flow Hydrograph=K100-00-00      ,DS K150         ,110864
Stage Flow Hydrograph=K100-00-00      ,DS K150         ,109706
Stage Flow Hydrograph=K100-00-00      ,DS K150         ,109583.
Stage Flow Hydrograph=K100-00-00      ,DS K150         ,109428
Stage Flow Hydrograph=K100-00-00      ,DS K150         ,109400
Stage Flow Hydrograph=K100-00-00      ,DS K150         ,109300.
Stage Flow Hydrograph=K100-00-00      ,DS K150         ,108918
Stage Flow Hydrograph=K100-00-00      ,DS K150         ,108501.
Stage Flow Hydrograph=K100-00-00      ,DS K150         ,108274
Stage Flow Hydrograph=K100-00-00      ,DS K150         ,108188
Stage Flow Hydrograph=K100-00-00      ,DS K150         ,107974.
Stage Flow Hydrograph=K100-00-00      ,DS K150         ,107642
Stage Flow Hydrograph=K100-00-00      ,DS K150         ,106632
Stage Flow Hydrograph=K100-00-00      ,DS K150         ,104790
Stage Flow Hydrograph=K100-00-00      ,DS K150         ,103431
Stage Flow Hydrograph=K100-00-00      ,DS K150         ,103030
Stage Flow Hydrograph=K100-00-00      ,DS K150         ,102901
Stage Flow Hydrograph=K100-00-00      ,DS K150         ,102875
Stage Flow Hydrograph=K100-00-00      ,DS K150         ,102762.
Stage Flow Hydrograph=K100-00-00      ,DS K150         ,102667
Stage Flow Hydrograph=K100-00-00      ,DS K150         ,101787
Stage Flow Hydrograph=K100-00-00      ,DS K150         ,100946
Stage Flow Hydrograph=K100-00-00      ,DS K150         ,99588
Stage Flow Hydrograph=K100-00-00      ,DS K150         ,98945
Stage Flow Hydrograph=K100-00-00      ,DS K150         ,98740
Stage Flow Hydrograph=K100-00-00      ,DS K150         ,98634
Stage Flow Hydrograph=K100-00-00      ,DS K150         ,98373
Stage Flow Hydrograph=K100-00-00      ,DS K150         ,97287
Stage Flow Hydrograph=K100-00-00      ,DS K150         ,96543
Stage Flow Hydrograph=K100-00-00      ,DS K150         ,95525
Stage Flow Hydrograph=K100-00-00      ,DS K150         ,94445
Stage Flow Hydrograph=K100-00-00      ,DS K150         ,93663
Stage Flow Hydrograph=K100-00-00      ,DS K150         ,91723
Stage Flow Hydrograph=K100-00-00      ,DS K150         ,91077
Stage Flow Hydrograph=K100-00-00      ,DS K150         ,90869
Stage Flow Hydrograph=K100-00-00      ,DS K150         ,90765
Stage Flow Hydrograph=K100-00-00      ,DS K150         ,90551
Stage Flow Hydrograph=K100-00-00      ,DS K150         ,89785
Stage Flow Hydrograph=K100-00-00      ,DS K150         ,88708
Stage Flow Hydrograph=K100-00-00      ,DS K150         ,87603
Stage Flow Hydrograph=K100-00-00      ,DS K150         ,86475
Stage Flow Hydrograph=K100-00-00      ,DS K150         ,85145
Stage Flow Hydrograph=K100-00-00      ,DS K150         ,83550
Stage Flow Hydrograph=K100-00-00      ,DS K150         ,82323
Stage Flow Hydrograph=K100-00-00      ,DS K150         ,80450
Stage Flow Hydrograph=K100-00-00      ,DS K150         ,78955
Stage Flow Hydrograph=K100-00-00      ,DS K150         ,78178
Stage Flow Hydrograph=K100-00-00      ,DS K150         ,76574
Stage Flow Hydrograph=K100-00-00      ,DS K150         ,75290
Stage Flow Hydrograph=K100-00-00      ,DS K150         ,73539
Stage Flow Hydrograph=K100-00-00      ,DS K150         ,71757
Stage Flow Hydrograph=K100-00-00      ,DS K150         ,71520
Stage Flow Hydrograph=K100-00-00      ,DS K150         ,71432
Stage Flow Hydrograph=K100-00-00      ,DS K150         ,71179.
Stage Flow Hydrograph=K100-00-00      ,DS K150         ,70967
Stage Flow Hydrograph=K100-00-00      ,DS K150         ,69993
Stage Flow Hydrograph=K100-00-00      ,DS K150         ,69040
Stage Flow Hydrograph=K100-00-00      ,DS K150         ,67953
Stage Flow Hydrograph=K100-00-00      ,DS K150         ,67762.
Stage Flow Hydrograph=K100-00-00      ,DS K150         ,67655
Stage Flow Hydrograph=K100-00-00      ,DS K150         ,67633
Stage Flow Hydrograph=K100-00-00      ,DS K150         ,67533
Stage Flow Hydrograph=K100-00-00      ,DS K150         ,65757
Stage Flow Hydrograph=K100-00-00      ,DS K150         ,63900
Stage Flow Hydrograph=K100-00-00      ,DS K150         ,62702
Stage Flow Hydrograph=K100-00-00      ,DS K150         ,61150
Stage Flow Hydrograph=K100-00-00      ,DS K150         ,60282
Stage Flow Hydrograph=K100-00-00      ,DS K150         ,58980
Stage Flow Hydrograph=K100-00-00      ,DS K150         ,57388
Stage Flow Hydrograph=K100-00-00      ,DS K150         ,55399
Stage Flow Hydrograph=K100-00-00      ,DS K150         ,53569
Stage Flow Hydrograph=K100-00-00      ,DS K150         ,52461
Stage Flow Hydrograph=K100-00-00      ,DS K150         ,51407
Stage Flow Hydrograph=K100-00-00      ,DS K150         ,51161
Stage Flow Hydrograph=K100-00-00      ,DS K150         ,50807
Stage Flow Hydrograph=K100-00-00      ,DS K150         ,50514
Stage Flow Hydrograph=K100-00-00      ,DS K150         ,49972
Stage Flow Hydrograph=K100-00-00      ,DS K150         ,49009
Stage Flow Hydrograph=K100-00-00      ,DS K150         ,47721
Stage Flow Hydrograph=K100-00-00      ,DS K150         ,46141
Stage Flow Hydrograph=K100-00-00      ,DS K150         ,46131
Stage Flow Hydrograph=K100-00-00      ,DS K150         ,46121
Stage Flow Hydrograph=K100-00-00      ,DS K150         ,45596
Stage Flow Hydrograph=K100-00-00      ,DS K150         ,44408
Stage Flow Hydrograph=K100-00-00      ,DS K150         ,42486
Stage Flow Hydrograph=K100-00-00      ,DS K150         ,42017.
Stage Flow Hydrograph=K100-00-00      ,DS K150         ,41696
Stage Flow Hydrograph=K100-00-00      ,DS K150         ,41578
Stage Flow Hydrograph=K100-00-00      ,DS K150         ,41496
Stage Flow Hydrograph=K100-00-00      ,DS K150         ,41366
Stage Flow Hydrograph=K100-00-00      ,DS K150         ,41320
Stage Flow Hydrograph=K100-00-00      ,DS K150         ,41272
Stage Flow Hydrograph=K100-00-00      ,DS K150         ,41055.
Stage Flow Hydrograph=K100-00-00      ,DS K150         ,40546
Stage Flow Hydrograph=K100-00-00      ,DS K150         ,39789
Stage Flow Hydrograph=K100-00-00      ,DS K150         ,38150
Stage Flow Hydrograph=K100-00-00      ,DS K150         ,36814
Stage Flow Hydrograph=K100-00-00      ,DS K150         ,35492
Stage Flow Hydrograph=K100-00-00      ,DS K150         ,34622
Stage Flow Hydrograph=K100-00-00      ,DS K150         ,33472
Stage Flow Hydrograph=K100-00-00      ,DS K150         ,32385.
Stage Flow Hydrograph=K100-00-00      ,DS K150         ,32215
Stage Flow Hydrograph=K100-00-00      ,DS K150         ,32130
Stage Flow Hydrograph=K100-00-00      ,DS K150         ,32081
Stage Flow Hydrograph=K100-00-00      ,DS K150         ,32056
Stage Flow Hydrograph=K100-00-00      ,DS K150         ,31954.
Stage Flow Hydrograph=K100-00-00      ,DS K150         ,30887
Stage Flow Hydrograph=K100-00-00      ,DS K150         ,29226
Stage Flow Hydrograph=K100-00-00      ,DS K150         ,28109
Stage Flow Hydrograph=K100-00-00      ,DS K150         ,26635
Stage Flow Hydrograph=K100-00-00      ,DS K150         ,26405
Stage Flow Hydrograph=K100-00-00      ,DS K150         ,26344
Stage Flow Hydrograph=K100-00-00      ,DS K150         ,26152.
Stage Flow Hydrograph=K100-00-00      ,DS K150         ,25956
Stage Flow Hydrograph=K100-00-00      ,DS K150         ,24423
Stage Flow Hydrograph=K100-00-00      ,DS K150         ,23894
Stage Flow Hydrograph=K100-00-00      ,DS K150         ,23289
Stage Flow Hydrograph=K100-00-00      ,DS K150         ,22568
Stage Flow Hydrograph=K100-00-00      ,DS K150         ,20680
Stage Flow Hydrograph=K100-00-00      ,DS K150         ,19313
Stage Flow Hydrograph=K100-00-00      ,DS K150         ,18611
Stage Flow Hydrograph=K100-00-00      ,DS K150         ,17183
Stage Flow Hydrograph=K100-00-00      ,DS K150         ,16487
Stage Flow Hydrograph=K100-00-00      ,DS K150         ,14603
Stage Flow Hydrograph=K100-00-00      ,DS K150         ,12763
Stage Flow Hydrograph=K100-00-00      ,DS K150         ,11417
Stage Flow Hydrograph=K100-00-00      ,DS K150         ,10889.
Stage Flow Hydrograph=K100-00-00      ,DS K150         ,10629
Stage Flow Hydrograph=K100-00-00      ,DS K150         ,10534
Stage Flow Hydrograph=K100-00-00      ,DS K150         ,10280.
Stage Flow Hydrograph=K100-00-00      ,DS K150         ,9768
Stage Flow Hydrograph=K100-00-00      ,DS K150         ,8114
Stage Flow Hydrograph=K100-00-00      ,DS K150         ,7033
Stage Flow Hydrograph=K100-00-00      ,DS K150         ,5279
Stage Flow Hydrograph=K100-00-00      ,DS K150         ,3988
Stage Flow Hydrograph=K150-00-00      ,REVISED ALIGN   ,13542.7
Stage Flow Hydrograph=K150-00-00      ,REVISED ALIGN   ,13537.7
Stage Flow Hydrograph=K150-00-00      ,REVISED ALIGN   ,13466.7
Stage Flow Hydrograph=K150-00-00      ,REVISED ALIGN   ,13357.7
Stage Flow Hydrograph=K150-00-00      ,REVISED ALIGN   ,12721.7
Stage Flow Hydrograph=K150-00-00      ,REVISED ALIGN   ,12180.7
Stage Flow Hydrograph=K150-00-00      ,REVISED ALIGN   ,11980.7
Stage Flow Hydrograph=K150-00-00      ,REVISED ALIGN   ,11904.7
Stage Flow Hydrograph=K150-00-00      ,REVISED ALIGN   ,11804.7
Stage Flow Hydrograph=K150-00-00      ,REVISED ALIGN   ,11289.7
Stage Flow Hydrograph=K150-00-00      ,REVISED ALIGN   ,10797.7
Stage Flow Hydrograph=K150-00-00      ,REVISED ALIGN   ,10697.7
Stage Flow Hydrograph=K150-00-00      ,REVISED ALIGN   ,10631.7
Stage Flow Hydrograph=K150-00-00      ,REVISED ALIGN   ,10531.7
Stage Flow Hydrograph=K150-00-00      ,REVISED ALIGN   ,10166.7
Stage Flow Hydrograph=K150-00-00      ,REVISED ALIGN   ,9910.7
Stage Flow Hydrograph=K150-00-00      ,REVISED ALIGN   ,9810.7
Stage Flow Hydrograph=K150-00-00      ,REVISED ALIGN   ,9749.7
Stage Flow Hydrograph=K150-00-00      ,REVISED ALIGN   ,9649.7
Stage Flow Hydrograph=K150-00-00      ,REVISED ALIGN   ,9119.7
Stage Flow Hydrograph=K150-00-00      ,REVISED ALIGN   ,8378.7
Stage Flow Hydrograph=K150-00-00      ,REVISED ALIGN   ,7862.7
Stage Flow Hydrograph=K150-00-00      ,REVISED ALIGN   ,7751.7
Stage Flow Hydrograph=K150-00-00      ,REVISED ALIGN   ,7715.7
Stage Flow Hydrograph=K150-00-00      ,REVISED ALIGN   ,7615.7
Stage Flow Hydrograph=K150-00-00      ,REVISED ALIGN   ,7097.7
Stage Flow Hydrograph=K150-00-00      ,REVISED ALIGN   ,7068.7
Stage Flow Hydrograph=K150-00-00      ,REVISED ALIGN   ,7046.7
Stage Flow Hydrograph=K150-00-00      ,REVISED ALIGN   ,6981.7
Stage Flow Hydrograph=K150-00-00      ,REVISED ALIGN   ,6537.7
Stage Flow Hydrograph=K150-00-00      ,REVISED ALIGN   ,6113.6
Stage Flow Hydrograph=K150-00-00      ,REVISED ALIGN   ,5523.2
Stage Flow Hydrograph=K150-00-00      ,REVISED ALIGN   ,5478.1
Stage Flow Hydrograph=K150-00-00      ,REVISED ALIGN   ,5444.1
Stage Flow Hydrograph=K150-00-00      ,REVISED ALIGN   ,5396.6
Stage Flow Hydrograph=K150-00-00      ,REVISED ALIGN   ,5343.7
Stage Flow Hydrograph=K150-00-00      ,REVISED ALIGN   ,5139.7
Stage Flow Hydrograph=K150-00-00      ,REVISED ALIGN   ,4673.4
Stage Flow Hydrograph=K150-00-00      ,REVISED ALIGN   ,4588.9
Stage Flow Hydrograph=K150-00-00      ,REVISED ALIGN   ,4457.2
Stage Flow Hydrograph=K150-00-00      ,REVISED ALIGN   ,4139.1
Stage Flow Hydrograph=K150-00-00      ,REVISED ALIGN   ,3935
Stage Flow Hydrograph=K150-00-00      ,REVISED ALIGN   ,3781.8
Stage Flow Hydrograph=K150-00-00      ,REVISED ALIGN   ,3510.5
Stage Flow Hydrograph=K150-00-00      ,REVISED ALIGN   ,3090.7
Stage Flow Hydrograph=K150-00-00      ,REVISED ALIGN   ,2949.1
Stage Flow Hydrograph=K150-00-00      ,REVISED ALIGN   ,2819.8
Stage Flow Hydrograph=K150-00-00      ,REVISED ALIGN   ,2548.4
Stage Flow Hydrograph=K150-00-00      ,REVISED ALIGN   ,2319
Stage Flow Hydrograph=K150-00-00      ,REVISED ALIGN   ,1991.9
Stage Flow Hydrograph=K150-00-00      ,REVISED ALIGN   ,1827
Stage Flow Hydrograph=K150-00-00      ,REVISED ALIGN   ,1622.4
Stage Flow Hydrograph=K150-00-00      ,REVISED ALIGN   ,1553.9
Stage Flow Hydrograph=K150-00-00      ,REVISED ALIGN   ,1249.3
Stage Flow Hydrograph=K150-00-00      ,REVISED ALIGN   ,1197
Stage Flow Hydrograph=K150-00-00      ,REVISED ALIGN   ,879.9
Stage Flow Hydrograph=K150-00-00      ,REVISED ALIGN   ,610.2
Stage Flow Hydrograph=K150-00-00      ,REVISED ALIGN   ,459.5
Stage Flow Hydrograph=K150-00-00      ,REVISED ALIGN   ,307.5
Stage Flow Hydrograph=K150-00-00      ,REVISED ALIGN   ,189.5
Stage Flow Hydrograph=K150-00-00      ,REVISED ALIGN   ,153
Stage Flow Hydrograph=K150-00-00      ,REVISED ALIGN   ,113
Stage Flow Hydrograph=K150-00-00      ,REVISED ALIGN   ,15
Stage Flow Hydrograph=K150-00-00      ,REVISED ALIGN   ,10
Stage Flow Hydrograph=K150-00-00      ,REVISED ALIGN   ,0
Stage Flow Hydrograph=K150-00-00      ,DS_DIVERSION    ,6515
Stage Flow Hydrograph=K150-00-00      ,DS_DIVERSION    ,6500
Stage Flow Hydrograph=K150-00-00      ,DS_DIVERSION    ,5654
Stage Flow Hydrograph=K150-00-00      ,DS_DIVERSION    ,5554
Stage Flow Hydrograph=K150-00-00      ,DS_DIVERSION    ,5462
Stage Flow Hydrograph=K150-00-00      ,DS_DIVERSION    ,5352
Stage Flow Hydrograph=K150-00-00      ,DS_DIVERSION    ,4365
Stage Flow Hydrograph=K150-00-00      ,DS_DIVERSION    ,3442
Stage Flow Hydrograph=K150-00-00      ,DS_DIVERSION    ,2605
Stage Flow Hydrograph=K150-00-00      ,DS_DIVERSION    ,2145
Stage Flow Hydrograph=K150-00-00      ,DS_DIVERSION    ,2095
Stage Flow Hydrograph=K150-00-00      ,DS_DIVERSION    ,1797
Stage Flow Hydrograph=K150-00-00      ,DS_DIVERSION    ,1795
Stage Flow Hydrograph=K150-00-00      ,DS_DIVERSION    ,1751
Stage Flow Hydrograph=K150-00-00      ,DS_DIVERSION    ,1642
Stage Flow Hydrograph=K150-00-00      ,DS_DIVERSION    ,1585
Stage Flow Hydrograph=K150-00-00      ,DS_DIVERSION    ,1385
Stage Flow Hydrograph=K150-00-00      ,DS_DIVERSION    ,862
Stage Flow Hydrograph=K150-00-00      ,DS_DIVERSION    ,740
Stage Flow Hydrograph=K150-00-00      ,DS_DIVERSION    ,705
Stage Flow Hydrograph=K150-00-00      ,DS_DIVERSION    ,605
Stage Flow Hydrograph=K150-00-00      ,DS_DIVERSION    ,409
Stage Flow Hydrograph=K150-00-00      ,DS_DIVERSION    ,400
Stage Flow Hydrograph=K150-00-00      ,DS_DIVERSION    ,380

--- K150-00-00.p02 (plan) ---

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Plan Title=FEMA Effective Floodway 2017
Short Identifier=K150_FW
Geom File=g01
Flow File=f02
Encroach Param=-1 ,0,0, 2
Encroach River=K150-00-00
Encroach Reach=REVISED ALIGN
Encroach Node=16558.7
       1 4975.15 5024.13
Encroach Node=16315
       1 4975.27  5023.2
Encroach Node=15607.2
       1 4975.91 5024.68
Encroach Node=15105.2
       1 4972.23 5025.08
Encroach Node=14893.7
       1  4975.4 5022.76
Encroach Node=14245.5
       1 4977.36 5028.87
Encroach Node=13706.5
       1 4976.31  5024.5
Encroach Node=13451
       1 4976.71 5026.36
Encroach Node=13247
       1 4920.06 5122.51
Encroach Node=13216.8
       1 4909.36 5157.34
Encroach Node=12691.3
       1 4639.31 5159.27
Encroach Node=12204.8
       1 4681.54 5306.15
Encroach Node=11899.1
       1 4654.09 5205.93
Encroach Node=11605.2
       1 4689.26 5234.58
Encroach Node=11052.6
       1 4738.94 5255.01
Encroach Node=10728.7
       1  4869.2 5130.01
Encroach Node=10404.9
       1 4817.84 5177.61
Encroach Node=9931.9
       1 4765.02 5267.77
Encroach Node=9662
       1 4800.79 5208.05
Encroach Node=9439.7
       1 4892.09 5280.46
Encroach Node=9095.9
       1 4815.22 5216.77
Encroach Node=8865.5
       1 4909.84 5087.39
Encroach Node=8699.1
       1 4900.35 5110.72
Encroach Node=8376.5
       1 4485.68  5255.1
Encroach Node=7881.8
       1 4755.02 5254.63
Encroach Node=7544.8
       1 4766.94 5186.35
Encroach Node=7370.6
       1 4801.65 5275.65
Encroach Node=7004.1
       1 4942.69  5088.6
Encroach Node=6912.7
       1 4864.43 5137.07
Encroach Node=6839.9
       1 4836.57 5120.43
Encroach Node=6666
       1 4816.75 5142.84
Encroach Node=6537.7
       1 4798.84 5142.67
Encroach Node=6113.6
       1 4818.29 5218.42
Encroach Node=5523.2
       1 4625.62 5280.95
Encroach Node=5478.1
       1 4584.22 5239.55
Encroach Node=5444.1
       1 3846.94 5271.25
Encroach Node=5396.6
       1 3825.74 5286.83
Encroach Node=5343.7
       1 4697.74 5283.87
Encroach Node=5139.7
       1 4862.58 5215.08
Encroach Node=4673.4
       1 4857.74 5131.52
Encroach Node=4588.9
       1 4878.88 5169.23
Encroach Node=4457.2
       1 4824.42 5121.61
Encroach Node=4139.1
       1 4896.69 5117.24
Encroach Node=3935
       1 4804.73 5140.66
Encroach Node=3781.8
       1 4871.89 5080.85
Encroach Node=3510.5
       1  4843.9    5216
Encroach Node=3090.7
       1  4811.5 5173.81
Encroach Node=2949.1
       1 4770.87 5165.83
Encroach Node=2819.8
       1 4812.41 5322.28
Encroach Node=2548.4
       1 4881.29 5115.09
Encroach Node=2500.6
       1 4868.83 5127.22
Encroach Node=2319
       1 4856.58 5225.93
Encroach Node=1991.9
       1 4741.11 5157.11
Encroach Node=1827
       1 4788.56 5201.78
Encroach Node=1622.4
       1 4917.37 5085.39
Encroach Node=1553.9
       1 4744.79 5467.12
Encroach Node=1274.1
       1 4885.79 5087.29
Encroach Node=1261.5
       1  4892.9 5078.02
Encroach Node=1249.3
       1    4900 5068.75
Encroach Node=1197
       1 4942.72 5057.28
Encroach Node=879.9
       1 4940.48 5059.52
Encroach Node=610.2
       1 4938.16 5061.84
Encroach Node=459.5
       1 4936.48 5063.52
Encroach Node=307.5
       1 4936.48 5063.52
Encroach Node=189.5
       1 4934.56 5065.44
Encroach Node=153
       1    4955    5045
Encroach Node=113
       1    4953    5047
Encroach Node=15
       1    4933    5067
Encroach Node=10
       1    4933    5067
Encroach Node=0
       1    4930    5070
FEMA Effective Floodway June 2007 + LOMR 07-06-1885P + LOMR 16-06-0557P + 17-06-0430X

--- K150-00-00.f01 (steady flow) ---

Flow Title=Effective Multi-Profile 2017
Program Version=3.13
Number of Profiles= 4
Profile Names=10 YR,50 YR,100 YR,500 YR
River Rch & RM=K150-00-00,REVISED ALIGN   ,16558.7
   192.3  406.82   547.5  1029.1
River Rch & RM=K150-00-00,REVISED ALIGN   ,14245.5
  198.82  438.28  587.54 1107.46
River Rch & RM=K150-00-00,REVISED ALIGN   ,13706.5
  208.12  457.06  613.56 1159.15
River Rch & RM=K150-00-00,REVISED ALIGN   ,12204.8
  229.59  499.27  675.04 1276.98
River Rch & RM=K150-00-00,REVISED ALIGN   ,10404.9
  241.66  515.64  713.78 1320.88
River Rch & RM=K150-00-00,REVISED ALIGN   ,7004.1
     237     528     775    1050
River Rch & RM=K150-00-00,REVISED ALIGN   ,6537.7
  272.75   451.4     641  852.13
River Rch & RM=K150-00-00,REVISED ALIGN   ,5444.1
     372     597     900    1258
River Rch & RM=K150-00-00,REVISED ALIGN   ,4673.4
  373.15  623.54     900 1312.15
River Rch & RM=K150-00-00,REVISED ALIGN   ,3510.5
     411     683    1002    1400
River Rch & RM=K150-00-00,REVISED ALIGN   ,1991.9
  436.39  730.56    1060 1538.88
River Rch & RM=K150-00-00,REVISED ALIGN   ,1197
     358     665     992    1478
Boundary for River Rch & Prof#=K150-00-00,REVISED ALIGN   , 1
Up Type= 0
Dn Type= 3
Dn Slope=0.00021
Boundary for River Rch & Prof#=K150-00-00,REVISED ALIGN   , 2
Up Type= 0
Dn Type= 3
Dn Slope=0.00021
Boundary for River Rch & Prof#=K150-00-00,REVISED ALIGN   , 3
Up Type= 0
Dn Type= 3
Dn Slope=0.00021
Boundary for River Rch & Prof#=K150-00-00,REVISED ALIGN   , 4
Up Type= 0
Dn Type= 3
Dn Slope=0.00021
DSS Import GetInterval= 0
DSS Import GetPeak= 0
DSS Import FillOption= 0

--- K150-00-00.f02 (steady flow) ---

Flow Title=Effective Floodway 2017
Program Version=3.13
Number of Profiles= 2
Profile Names=100YR,FW
River Rch & RM=K150-00-00,REVISED ALIGN   ,16558.7
   547.5   547.5
River Rch & RM=K150-00-00,REVISED ALIGN   ,14245.5
  587.54  587.54
River Rch & RM=K150-00-00,REVISED ALIGN   ,13706.5
  613.56  613.56
River Rch & RM=K150-00-00,REVISED ALIGN   ,12204.8
  675.04  675.04
River Rch & RM=K150-00-00,REVISED ALIGN   ,10404.9
  713.78  713.78
River Rch & RM=K150-00-00,REVISED ALIGN   ,7004.1
     775     775
River Rch & RM=K150-00-00,REVISED ALIGN   ,6537.7
     641     641
River Rch & RM=K150-00-00,REVISED ALIGN   ,5444.1
     900     900
River Rch & RM=K150-00-00,REVISED ALIGN   ,4673.4
     900     900
River Rch & RM=K150-00-00,REVISED ALIGN   ,3510.5
    1002    1002
River Rch & RM=K150-00-00,REVISED ALIGN   ,1991.9
    1060    1060
River Rch & RM=K150-00-00,REVISED ALIGN   ,1197
     992     992
Boundary for River Rch & Prof#=K150-00-00,REVISED ALIGN   , 1
Up Type= 0
Dn Type= 3
Dn Slope=0.00021
Boundary for River Rch & Prof#=K150-00-00,REVISED ALIGN   , 2
Up Type= 0
Dn Type= 3
Dn Slope=0.00021
DSS Import GetInterval= 0
DSS Import GetPeak= 0
DSS Import FillOption= 0

--- K150-00-00.g01 (geometry) ---

Geom Title=K150-00-00 2017
Program Version=3.13

River Reach=K150-00-00      ,REVISED ALIGN
Reach XY= 30
      2996707.59     13903346.65     2997518.082     13903128.39
     3000504.123     13902938.73     3000747.375     13902819.03
     3001464.674     13903094.83     3001792.716     13903426.79
     3002333.099     13903486.86     3002386.018     13903734.46
     3002253.862     13904238.15     3002322.665      13904733.8
      3002238.69      13905013.7     3002417.622     13905242.14
     3002381.212      13905461.7     3002495.884     13905720.34
     3002920.937     13906197.52     3003288.171     13906244.77
     3003479.474     13906407.05      3003682.53     13906362.32
     3003993.662     13906576.55     3004196.214     13907808.69
      3004523.57     13908116.05     3004850.859     13908659.61
     3005988.591       13909347.     3006093.504     13909985.32
     3006345.401     13910084.96     3006408.153     13910370.62
     3006571.588     13910515.32      3006461.07     13911039.81
     3005780.028     13911326.45   3005909.8681213911464.4523724

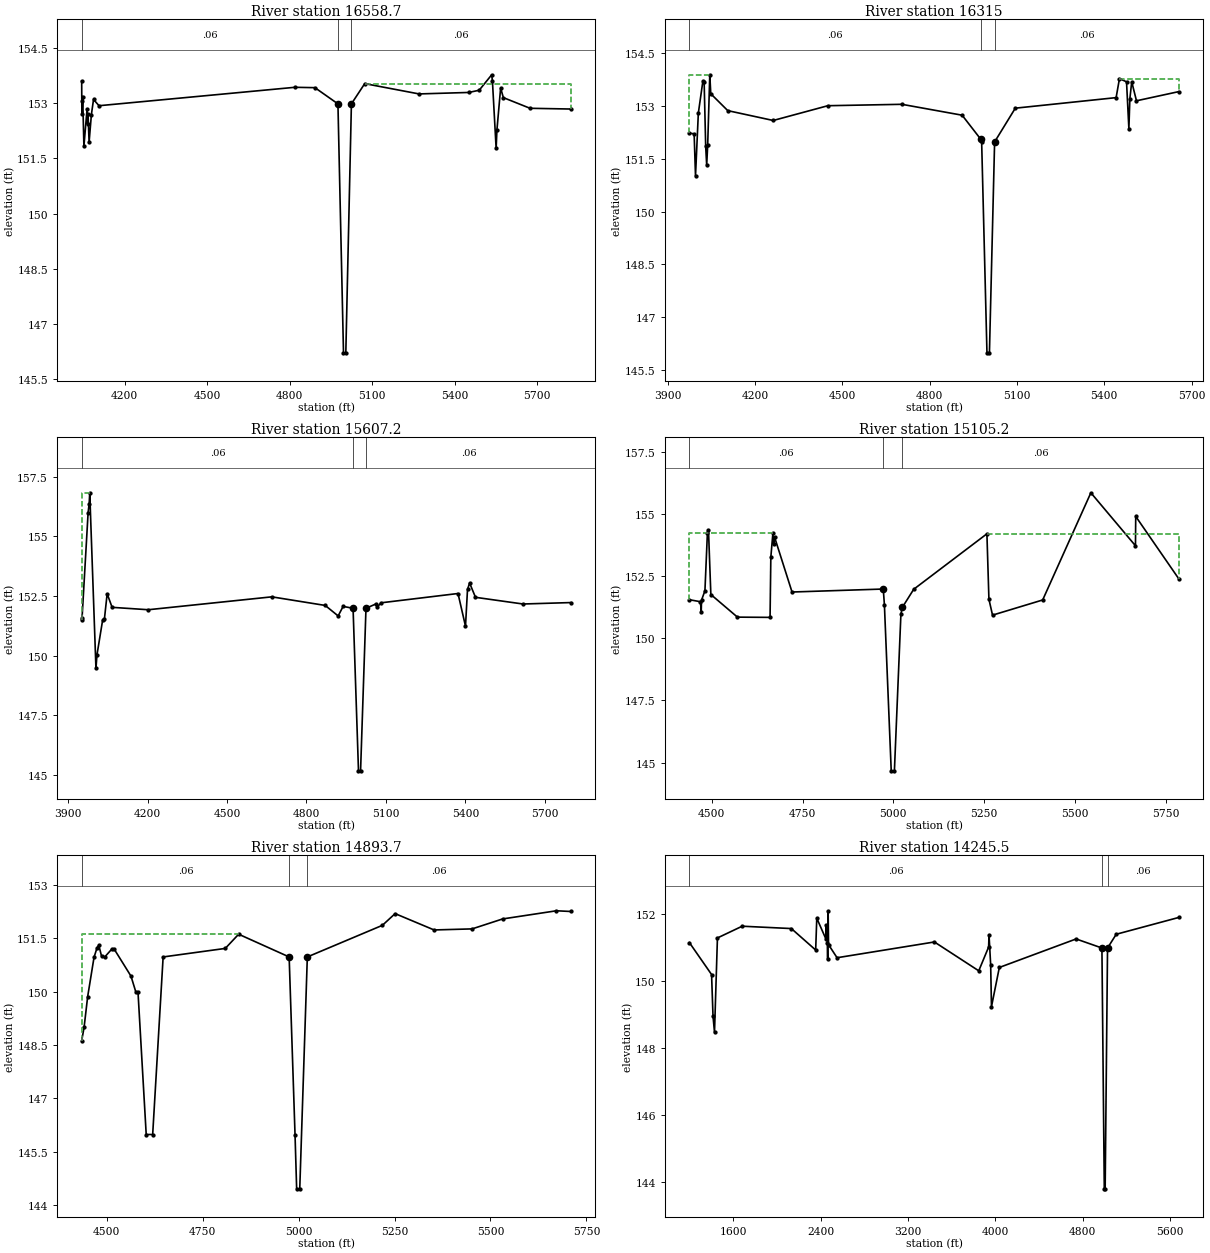
Type RM Length L Ch R = 1 ,16558.7 ,243.7,243.7,243.7
XS GIS Cut Line= 4
  2997361.21608813904133.0085046 2997232.500138413903553.0795463
 2997018.252207313902868.2521758 2996999.447126813902401.3485821
#Sta/Elev= 30
 4043.36   153.6  4043.7  153.05 4044.18  152.71 4046.98  153.18 4051.44  151.83
 4062.93  152.84 4064.57  152.43  4066.4  152.71  4070.3  151.94 4078.64  152.69
 4086.41   153.1 4106.34  152.93 4818.55  153.43 4891.44  153.42 4975.15  152.98
 4995.37  146.22  5003.8  146.22 5024.13  152.98 5072.55  153.53 5270.13  153.25
 5450.72  153.29 5488.72  153.35 5534.27  153.77 5536.95   153.6 5550.41  151.77
 5553.27  152.27 5566.75  153.41 5576.62  153.15 5673.75  152.86 5822.24  152.84
#Mann= 3 ,-1 , 0
 4043.36     .06       0 4975.15     .04       0 5024.13     .06       0
#XS Ineff= 2 , 0
       0 4818.55  153.43 5072.55       0  153.53
Permanent Ineff=
       F       F
Bank Sta=4975.15,5024.13
Exp/Cntr=0.3,0.1

Type RM Length L Ch R = 1 ,16315   ,706.02,707.8,706.02
XS GIS Cut Line= 6
  2997496.31391513904170.1695195 2997425.338335413903640.2325872
 2997417.672668313903581.8232552 2997343.505165713903016.7056191
 2997341.711534113902750.4046425 2997340.956614413902499.6863119
#Sta/Elev= 30
 3974.81  152.23    3991  152.21 3995.67  151.01 4005.42   152.8 4021.02  153.71
 4025.33  153.69 4030.67  151.85 4034.09  151.32 4037.48  151.88 4044.72  153.89
 4048.17  153.35 4106.54  152.87 4262.62  152.59 4450.41  153.01 4704.52  153.05
 4911.63  152.74 4975.27  152.06 4978.69  151.98 4996.93  145.98 5005.41  145.98
  5023.2  151.98  5094.3  152.94 5440.62  153.24 5452.08  153.78 5476.39  153.69
 5484.46  152.36 5487.87  153.21 5494.23  153.69 5510.58  153.15 5655.38  153.41
#Mann= 3 ,-1 , 0
 3974.81     .06       0 4975.27     .04       0  5023.2     .06       0
#XS Ineff= 2 , 0
       0 4044.72  153.89 5452.08       0  153.78
Permanent Ineff=
       F       F
Bank Sta=4975.27,5023.2
Exp/Cntr=0.3,0.1

Type RM Length L Ch R = 1 ,15607.2 ,508.82,502,508.82
XS GIS Cut Line= 6
  2998042.79707413904163.1964363 2998054.725856113903573.3718286
  2998060.45353513903370.1452009 2998071.450888313902910.4315534
 2998070.689078813902588.0942716 2998067.5424316 13902316.297243
#Sta/Elev= 30
 3951.17  151.51  3952.6  151.58 3975.41  155.99 3979.43  156.37 3981.59  156.82
 4005.01  149.46  4008.9  150.03 4030.03  151.47  4037.1  151.54 4047.33  152.59
 4066.05  152.02 4202.71  151.92 4669.11  152.46 4870.74   152.1 4919.58  151.66
 4938.35  152.06 4975.91  151.98 4996.39  145.17 5004.24  145.17 5024.68  151.98
 5061.66  152.16 5067.05  152.03 5081.51  152.21 5372.18   152.6 5400.45  151.23
 5408.04  152.77 5415.92  153.04 5438.19  152.44 5617.54  152.16 5798.42  152.22
#Mann= 3 ,-1 , 0
 3951.17     .06       0 4975.91     .04       0 5024.68     .06       0
#XS Ineff= 2 , 0
       0 3981.59  156.82               0
Permanent Ineff=
       F       F
Bank Sta=4975.91,5024.68
Exp/Cntr=0.3,0.1

Type RM Length L Ch R = 1 ,15105.2 ,205.41,211.5,205.41
XS GIS Cut Line= 6
  2998594.22510513903676.0064658 2998592.633244913903645.6971432
 2998591.236594113903615.4439229 2998572.603757413903211.8633652
 2998541.010972813902527.5832377 2998532.217027113902329.8260873
#Sta/Elev= 30
 4438.28  151.55 4468.57  151.47 4470.81  151.07 4471.54  151.53 4480.98  151.91
 4487.82  154.24 4490.76  154.35 4497.29  151.76 4570.56  150.85  4660.4  150.84
 4662.52  153.26 4668.18  154.22 4670.38  153.78 4672.95  154.06 4720.91  151.86
 4972.23  151.98 4975.37  151.35 4994.17  144.67 5002.93  144.67 5020.89  150.98
 5025.08  151.25 5056.12  151.97 5257.75   154.2  5263.3  151.57 5273.22  150.93
 5411.37  151.54 5544.11  155.85 5666.99  153.72 5667.68   154.9 5785.89   152.4
#Mann= 3 ,-1 , 0
 4438.28     .06       0 4972.23     .04       0 5025.08     .06       0
#XS Ineff= 2 , 0
       0 4668.18  154.22 5257.75       0   154.2
Permanent Ineff=
       F       F
Bank Sta=4972.23,5025.08
Exp/Cntr=0.3,0.1

Type RM Length L Ch R = 1 ,14893.7 ,647.66,648.2,647.66
XS GIS Cut Line= 6
  2998777.45833413903661.8791975   2998777.63714 13903616.074171
 2998778.506232713903211.5247832 2998779.807411213902605.7353124
  2998779.84579713902587.9938781 2998779.841531913902387.2446076
#Sta/Elev= 30
 4434.85  148.62 4441.12     149 4450.38  149.86 4467.02  150.97 4474.96  151.24
 4479.42  151.31 4486.65     151 4494.97  150.98 4514.02  151.21 4520.13  151.19
 4563.28  150.44  4576.3  149.98 4581.63  149.98 4602.96  145.98 4619.81  145.98
 4647.06  150.98 4808.99  151.22 4843.82  151.62  4975.4  150.98  4990.7  145.98
 4994.95  144.45 5003.03  144.45 5022.76  150.98 5218.25  151.87 5251.52   152.2
 5353.07  151.74 5452.08  151.77 5531.58  152.05 5671.79  152.28 5709.49  152.26
#Mann= 3 ,-1 , 0
 4434.85     .06       0  4975.4     .04       0 5022.76     .06       0
#XS Ineff= 2 , 0
       0 4843.82  151.62               0
Permanent Ineff=
       F       F
Bank Sta=4975.4,5022.76
Exp/Cntr=0.3,0.1

Type RM Length L Ch R = 1 ,14245.5 ,541.71,539,541.71
XS GIS Cut Line= 6
  2998826.80994113906716.7598987 2999417.000034513904419.0000586
 2999414.294987413903302.7608212 2999414.673923613903251.5227347
 2999418.082053313902790.6043652 2999409.080102813902307.0600567
#Sta/Elev= 30
 1196.19  151.14 1399.13  150.19 1412.34  148.95 1426.02  148.47  1452.9  151.28
 1679.76  151.63 2130.39  151.56 2353.42  150.92 2363.54  151.87 2446.89  151.25
 2448.05  151.67  2460.8  151.13 2463.38  150.64 2467.68  152.09 2471.35  151.08
 2549.44  150.69 3441.79  151.16 3848.36   150.3 3938.92  151.01 3942.31  151.38
 3957.56  150.48 3964.94  149.23 4036.97   150.4 4740.64  151.25 4977.36  150.98
 4999.15   143.8 5007.03   143.8 5028.87  150.98 5108.66  151.39 5680.58  151.89
#Mann= 3 ,-1 , 0
 1196.19     .06       0 4977.36     .04       0 5028.87     .06       0
Bank Sta=4977.36,5028.87
Exp/Cntr=0.3,0.1