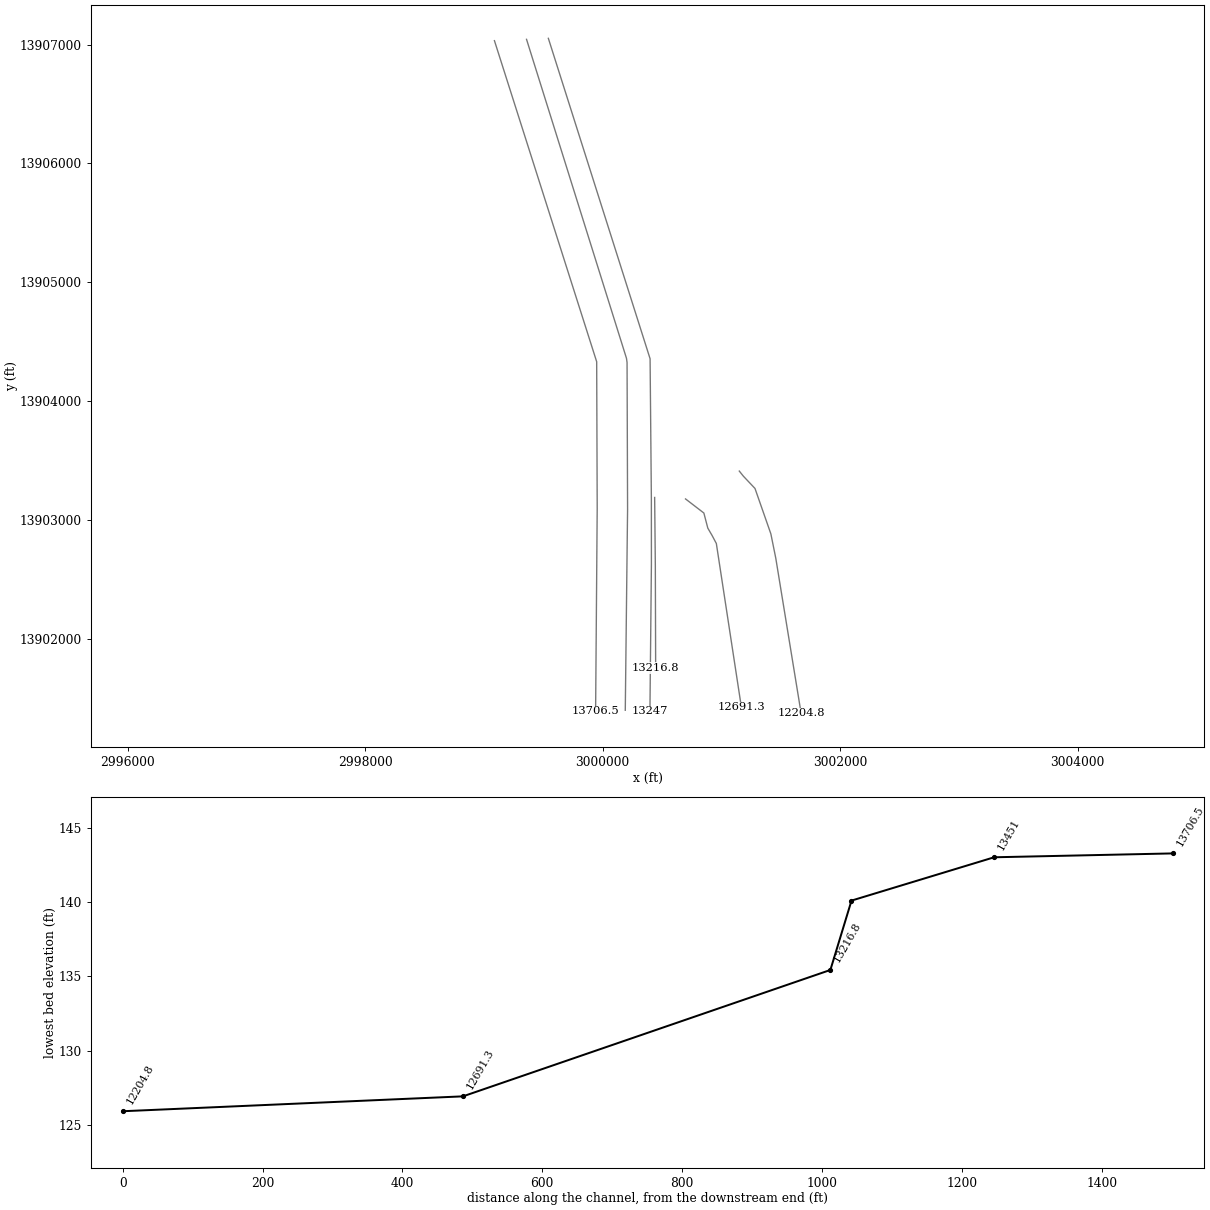
HEC-RAS study K150-00-00.prj: K150-00-00

--- K150-00-00.g01 (geometry) --- (continued)

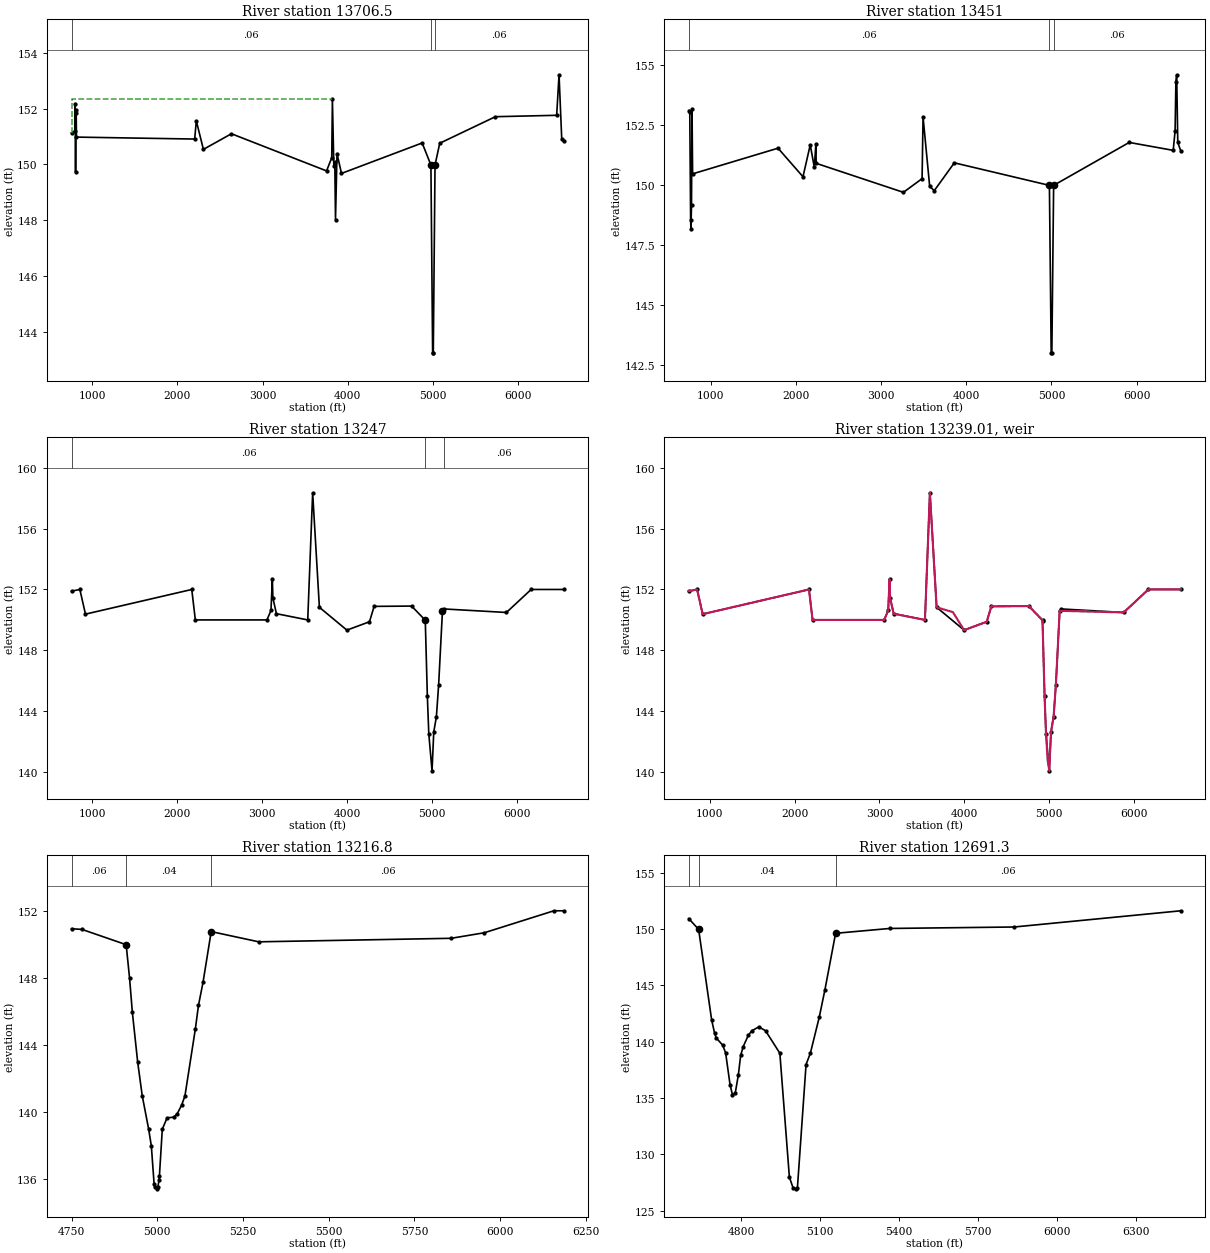
Type RM Length L Ch R = 1 ,13706.5 ,276.41,255.5,296.03
XS GIS Cut Line= 6
  2999087.60994513907032.6798706 2999948.999954713904330.9999065
 2999953.416940613903096.9338051 2999952.519960813902981.5541146
 2999950.731250513902751.4174357 2999939.9999727 13901390.999881
#Sta/Elev= 30
     758  151.13  796.88  151.19  800.52  152.18  804.77  149.73  809.19  151.83
  812.27  151.95  814.85  150.98 2202.97  150.91 2222.47  151.56 2305.39  150.54
 2634.63   151.1  3751.4  149.77 3812.02  150.24 3819.88  152.33 3836.57  149.94
 3847.97  150.09 3856.23  148.03 3873.86  150.39  3926.5  149.68  4873.4  150.77
 4976.31  149.98 4996.41  143.26 5004.18  143.26  5024.5  149.98 5079.79  150.76
 5733.22  151.71 6452.52  151.76 6480.37  153.21  6512.1   150.9 6533.74  150.84
#Mann= 3 ,-1 , 0
     758     .06       0 4976.31     .04       0  5024.5     .06       0
#XS Ineff= 2 , 0
       0 3819.88  152.33               0
Permanent Ineff=
       F       F
Bank Sta=4976.31,5024.5
Exp/Cntr=0.3,0.1

Type RM Length L Ch R = 1 ,13451   ,209.57,204,224.45
XS GIS Cut Line= 6
  2999358.00015213907044.0000579 3000200.000108913904359.9998485
 3000205.000098913904323.9999205 3000209.349499613903088.8078371
 3000205.335728113902742.2107612 3000190.0001289 13901397.999867
#Sta/Elev= 30
  743.84   153.1  755.23  153.03  765.09  148.52  768.91  148.17  775.46  149.17
   781.7  153.18  788.41  150.46 1791.09  151.53 2084.14  150.34  2169.3  151.67
 2217.35  150.73 2235.77  151.72 2238.72   150.9 3262.76  149.69 3482.17  150.26
 3493.51  152.83 3571.26  149.94 3625.09  149.76 3860.47  150.92 4976.71  149.98
 4997.63     143 5005.39     143 5026.36  149.98 5913.63  151.77 6430.09  151.44
  6452.1  152.25  6461.4  154.28 6470.79  154.59 6483.65  151.77 6519.28  151.41
#Mann= 3 ,-1 , 0
  743.84     .06       0 4976.71     .04       0 5026.36     .06       0
Bank Sta=4976.71,5026.36
Exp/Cntr=0.5,0.3

Type RM Length L Ch R = 1 ,13247   ,29.96,30.2,30.3
XS GIS Cut Line= 6
  2999541.86002113907052.3300937  3000399.00003913904355.9998565
  3000409.77560813903181.4103421 3000409.896014613903014.3243902
 3000410.172588813902629.4104619 3000397.699844713901390.1800007
#Sta/Elev= 30
     754  151.89  851.54     152  917.49  150.38 2169.59     152 2211.71     150
 3055.39     150 3102.47  150.62 3118.91  152.68 3125.07  151.44 3166.85  150.41
 3535.63     150 3593.59  158.35 3672.94  150.83 3996.75  149.33 4262.97  149.88
 4317.41  150.89 4759.04  150.91 4920.06  149.98 4920.35  149.92 4944.56  144.98
 4961.65  142.51 4999.71  140.09  5020.1  142.65 5051.02  143.64 5077.64  145.75
 5122.51   150.6 5143.23  150.72 5875.91  150.49 6167.01     152 6549.22     152
#Mann= 3 ,-1 , 0
     754     .06       0 4920.35     .04       0 5143.23     .06       0
Bank Sta=4920.06,5122.51
Exp/Cntr=0.5,0.3

Type RM Length L Ch R = 5 ,13239.01,,,
BEGIN DESCRIPTION:
Drop Structure B12
END DESCRIPTION:
IW Pilot Flow=0
#Inline Weir SE= 30
     754  151.89  851.54     152  917.49  150.38 2169.59     152 2211.71     150
 3055.39     150 3102.47  150.62 3118.91  152.68 3125.07  151.44 3166.85  150.41
 3535.63     150 3593.59  158.35 3672.94  150.83 3865.15  150.51 3996.75  149.33
 4262.97  149.88 4317.41  150.89 4759.04  150.91 4920.06  149.98 4944.56  144.98
 4961.65  142.51 4980.49   140.8 4999.71  140.09  5020.1  142.65 5051.02  143.64
 5077.64  145.75 5122.51   150.6 5875.91  150.49 6167.01     152 6549.22     152
IW Dist,WD,Coef,Skew,MaxSub,Min_El,Is_Ogee,SpillHt,DesHd
4,19,2.6,0,0.95,, 0 ,,,0,0,

Type RM Length L Ch R = 1 ,13216.8 ,293.56,525.5,541.64
XS GIS Cut Line= 6
  3000437.42056513903188.7203669 3000438.998646613903032.0441711
 3000439.935980713902938.9347772 3000441.431056513902790.5111896
 3000443.188598913902615.9872604 3000445.884459613901754.0185119
#Sta/Elev= 30
  4750.2  150.93 4780.41  150.89 4909.36  149.98 4919.32  147.98 4927.28  145.98
 4942.95  142.98  4956.2  140.98 4975.04  138.98 4982.83  137.98 4990.88  135.71
 4992.69  135.54 4998.97  135.43 5001.91  135.56  5005.3  135.95 5006.26  136.17
 5014.73  138.98 5028.63  139.66 5047.81   139.7 5058.26   139.9 5071.51  140.44
 5080.79  140.97 5111.29  144.98  5120.2  146.36 5133.54  147.74 5157.34  150.76
 5295.91  150.15 5857.05  150.36 5953.71  150.69 6156.74     152 6184.94     152
#Mann= 3 , 0 , 0
  4750.2     .06       0 4909.36     .04       0 5157.34     .06       0
Bank Sta=4909.36,5157.34
Exp/Cntr=0.5,0.3

Type RM Length L Ch R = 1 ,12691.3 ,508.98,486.5,475.52
XS GIS Cut Line= 6
  3000697.474179 13903176.437255 3000852.057531813903057.8279122
 3000885.342570213902930.6250826 3000921.437314313902868.7272405
 3000957.193476413902801.3618896 3001168.106440413901423.9259962
#Sta/Elev= 30
 4602.02  150.93 4639.31  149.98  4688.7  141.94 4700.11  140.74 4706.34  140.33
 4730.57   139.7 4741.85  139.01 4758.84  136.14 4767.73  135.31 4778.04  135.41
 4790.02  137.04 4798.81  138.78 4808.56  139.57 4827.61  140.56 4841.34  140.98
  4867.9  141.32 4893.23  140.98 4947.65  138.98 4983.81  127.98  4998.5  126.98
 5007.22  126.94 5014.18  126.98 5047.14  137.98 5063.45  138.98 5097.13  142.17
 5118.78  144.62 5159.27  149.63 5364.54  150.06 5837.23  150.19 6469.78  151.63
#Mann= 3 , 0 , 0
 4602.02     .06       0 4639.31     .04       0 5159.27     .06       0
Bank Sta=4639.31,5159.27
Exp/Cntr=0.3,0.1

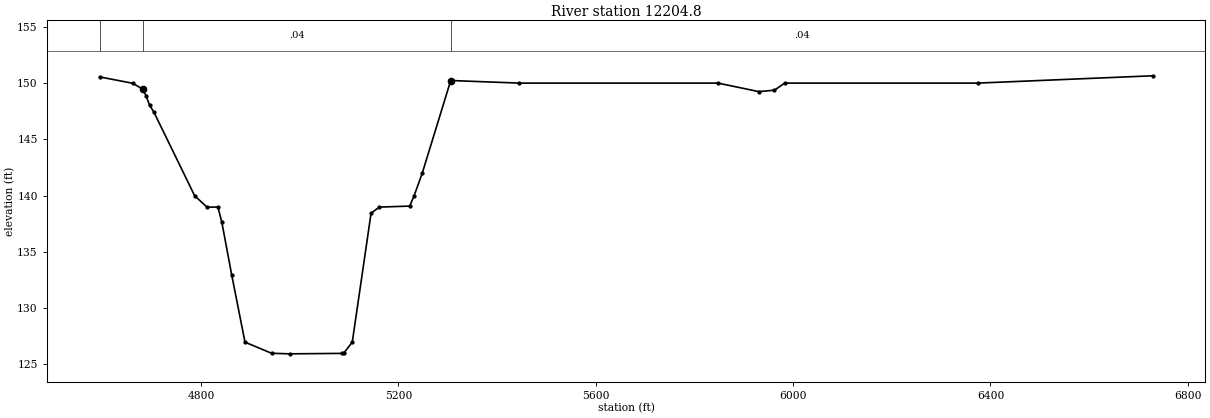
Type RM Length L Ch R = 1 ,12204.8 ,362.34,305.7,492.77
XS GIS Cut Line= 6
  3001150.59892913903410.8121143  3001185.321301 13903367.409314
 3001282.859163613903264.4816983  3001416.54131113902882.5379084
 3001457.890637713902678.1731596 3001671.5788586 13901371.842439
#Sta/Elev= 30
 4594.62  150.55 4662.04  149.98 4681.54  149.47 4688.88  148.87 4695.99  148.01
 4704.27  147.45 4787.15  139.99 4812.24  138.98 4834.31  138.98  4842.2  137.65
 4862.14  132.98 4889.19  126.98 4943.08  125.99 4979.96  125.94  5085.7  125.98
 5090.03  126.04 5106.63  126.98 5144.72  138.44 5161.42  138.98 5223.02  139.07
 5231.87  139.98 5248.32  141.98 5306.15  150.23 5444.21     150 5847.74     150
  5930.8  149.24 5962.19  149.37 5983.02     150 6374.93     150 6728.88  150.65
#Mann= 3 , 0 , 0
 4594.62     .06       0 4681.54     .04       0 5306.15     .04       0
Bank Sta=4681.54,5306.15
Exp/Cntr=0.3,0.1