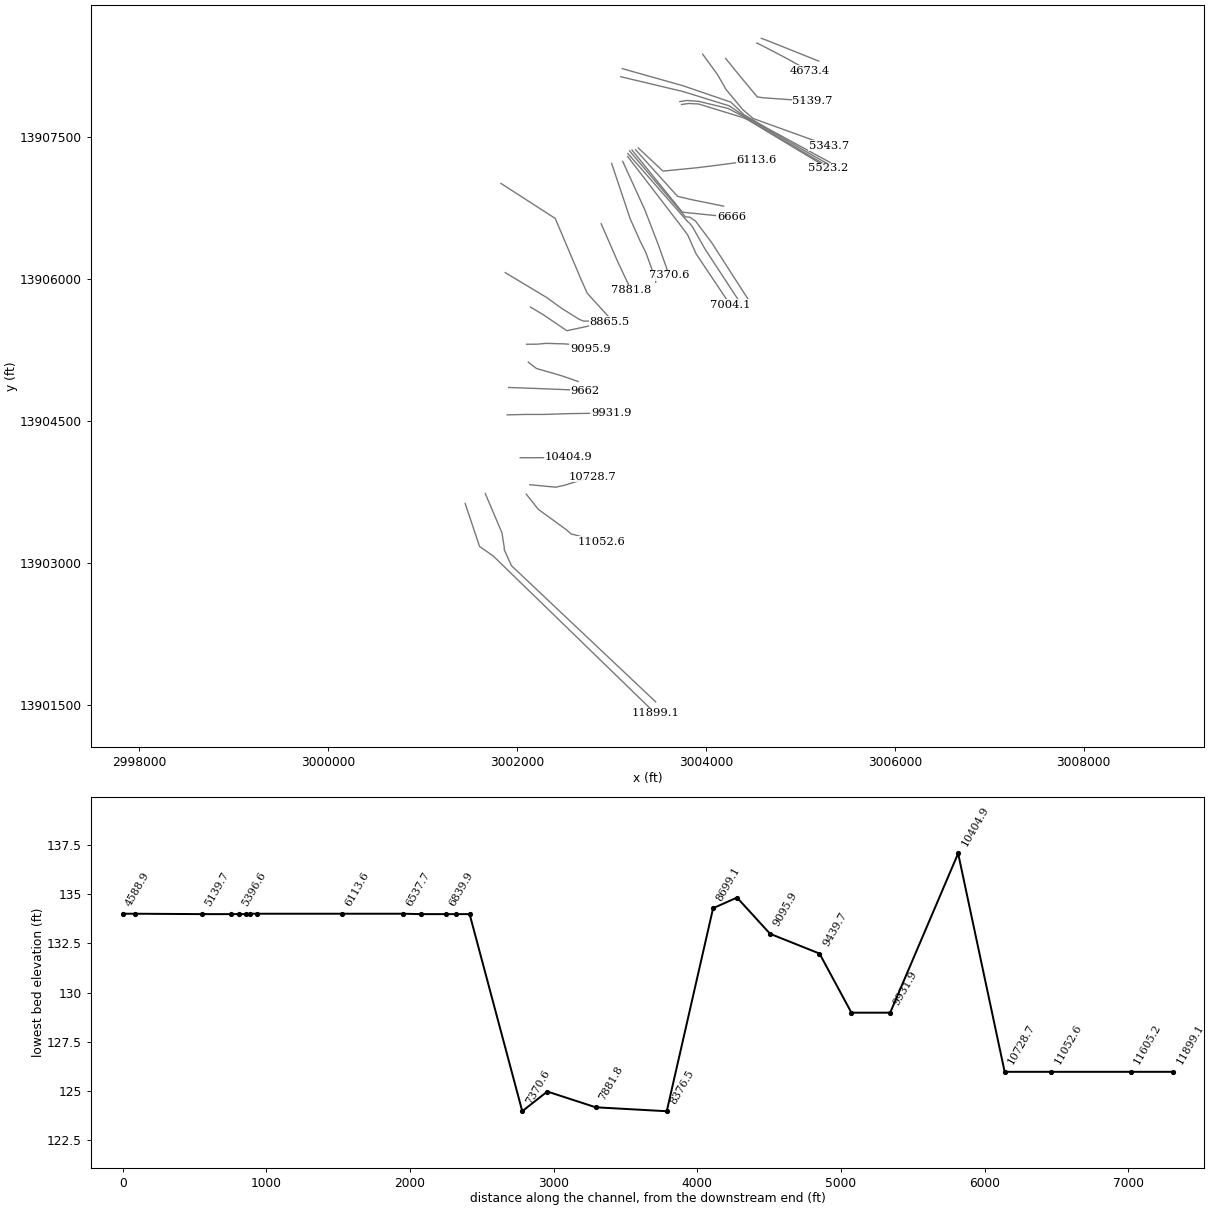
HEC-RAS study K150-00-00.prj: K150-00-00

--- K150-00-00.g01 (geometry) --- (continued)

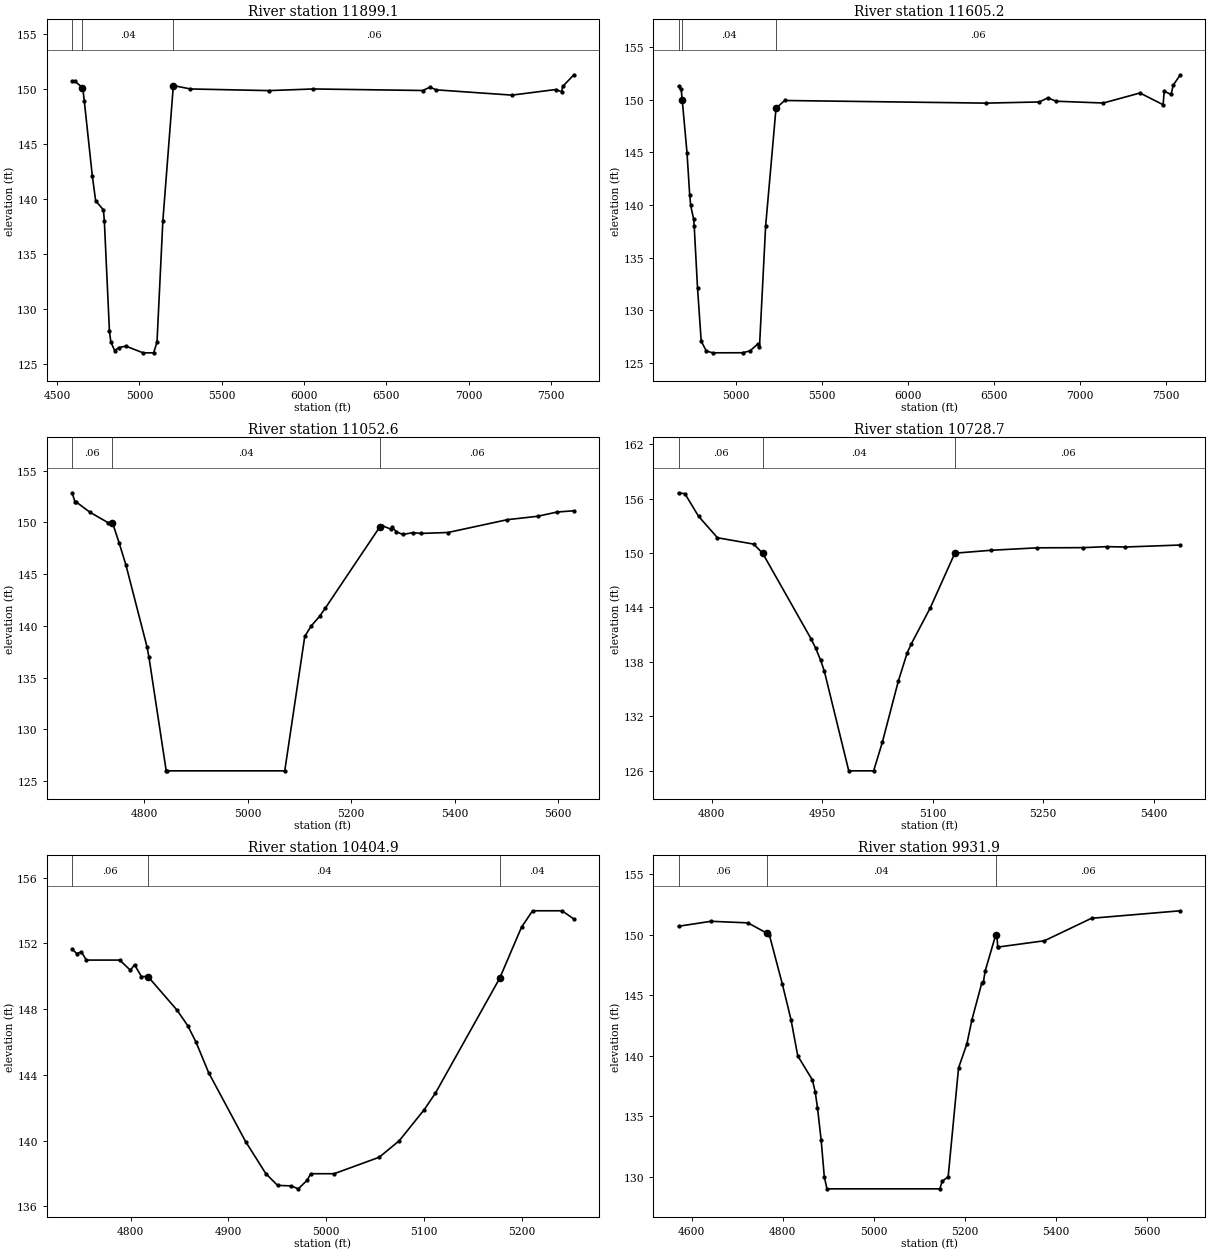
Type RM Length L Ch R = 1 ,11899.1 ,240.11,293.9,158.11
BEGIN DESCRIPTION:
K150-00-00-S5_UNKNOWN RD - DS - XS1
END DESCRIPTION:
XS GIS Cut Line= 6
  3001450.51073113903626.6863545  3001582.31263313903233.5349098
 3001602.905767613903172.1085235 3001706.285810213903100.4272364
 3001747.345439413903071.9578051 3003464.113659413901406.5648105
#Sta/Elev= 30
    4591  150.68 4609.13  150.66 4654.09  150.11 4656.48     150 4665.08  148.91
 4713.69   142.1 4734.17  139.81 4781.54  138.98 4786.94  137.98 4817.85  127.98
 4826.14  126.98 4849.75  126.18 4874.84  126.46 4917.52  126.59  5022.5  125.98
 5086.48  125.98 5106.75  126.96 5142.29  137.98 5205.93  150.29 5309.59  149.98
 5785.15  149.83 6056.51  149.98  6720.3  149.84 6764.34  150.14 6801.91   149.9
 7261.79  149.42 7528.94  149.93 7563.73  149.72 7570.29  150.21 7638.04  151.27
#Mann= 3 , 0 , 0
    4591     .06       0 4654.09     .04       0 5205.93     .06       0
Bank Sta=4654.09,5205.93
Exp/Cntr=0.3,0.1

Type RM Length L Ch R = 1 ,11605.2 ,444.82,552.6,719.33
BEGIN DESCRIPTION:
K150-00-00_Interpolated XS4
END DESCRIPTION:
XS GIS Cut Line= 6
  3001663.18222113903732.2914582 3001840.164151413903316.5245732
 3001863.988250713903163.7191046 3001863.683789413903138.9678417
 3001940.676089513902969.0649663 3003468.453873813901528.0924546
#Sta/Elev= 30
 4667.79  151.26 4683.25  150.98 4689.26  149.98 4716.97  144.98 4732.65  140.98
 4738.39  139.98 4755.85  138.64 4759.02  137.98 4778.07  132.18 4799.67  127.08
 4829.37  126.16 4866.09  125.98 5040.12  125.99  5082.7  126.16  5128.9  126.82
 5138.36   126.5 5174.11  137.98 5234.58  149.18 5284.92  149.93 6455.48  149.68
 6766.14  149.79 6814.55  150.18 6864.14  149.86 7137.82  149.69 7351.02  150.64
  7485.5  149.53 7492.04  150.81 7531.85   150.5  7544.4  151.39 7585.72  152.37
#Mann= 3 , 0 , 0
 4667.79     .06       0 4689.26     .04       0 5234.58     .06       0
Bank Sta=4689.26,5234.58
Exp/Cntr=0.3,0.1

Type RM Length L Ch R = 1 ,11052.6 ,132.64,323.9,503.85
BEGIN DESCRIPTION:
K150-00-00-S4_UNNAMED RD - DS - XS1
END DESCRIPTION:
XS GIS Cut Line= 6
   3002097.2400813903726.2776907 3002224.510495613903565.7799802
 3002333.099189113903486.8588782  3002527.37373513903345.6580451
 3002570.252586213903306.2001188 3002891.196826213903220.8010114
#Sta/Elev= 30
 4660.93  152.86 4666.63  151.98 4668.71  151.98 4695.39  150.98 4730.21  149.98
 4738.94  149.98 4752.09  147.98 4765.05  145.87 4805.66  137.98 4809.45  136.98
 4842.76     126 4844.14  125.98  5071.9  125.98  5110.6  138.98 5122.95  139.98
 5139.28  140.92 5150.02  141.69 5255.01  149.52 5259.73  149.69 5277.34  149.34
 5279.86  149.54 5287.27   149.1 5300.01  148.83 5319.99  149.01  5334.4  148.93
 5387.24  149.02 5502.06  150.26 5560.86  150.59 5598.17     151 5630.56  151.12
#Mann= 3 , 0 , 0
 4660.93     .06       0 4738.94     .04       0 5255.01     .06       0
Bank Sta=4738.94,5255.01
Exp/Cntr=0.3,0.1

Type RM Length L Ch R = 1 ,10728.7 ,308.61,323.8,298.01
BEGIN DESCRIPTION:
K150-00-00_Interpolated XS3
END DESCRIPTION:
XS GIS Cut Line= 6
    3002135.444413903825.8165336  3002195.91376813903819.9805873
 3002410.669572113903799.7421107 3002511.772388213903822.8093218
 3002535.860594613903830.6784006 3002798.889268113903912.1231196
#Sta/Elev= 24
 4755.13  156.64 4763.82  156.53 4782.28  154.05 4807.96  151.68 4857.16  150.98
  4869.2  149.98 4934.92  140.54 4941.26   139.5 4948.01  138.16 4952.92  136.98
  4986.1  125.98 5019.89  125.98 5031.59  129.11 5053.41  135.89 5065.38  138.99
 5070.93  139.97 5096.88  143.98 5130.01  149.98 5179.22   150.3 5241.49  150.57
  5303.9  150.59 5336.28   150.7 5361.34  150.66 5435.99  150.88
#Mann= 3 , 0 , 0
 4755.13     .06       0  4869.2     .04       0 5130.01     .06       0
Bank Sta=4869.2,5130.01
Exp/Cntr=0.3,0.1

Type RM Length L Ch R = 1 ,10404.9 ,469.43,473,473.28
BEGIN DESCRIPTION:
K150-00-00-S3_UNNAMED RD - DS - XS2
Inverted culvert slope per survey
END DESCRIPTION:
XS GIS Cut Line= 6
  3002033.22216413904111.3067763  3002121.15013813904111.5564477
 3002301.226549513904112.0679296 3002458.067115113904118.4311059
  3002465.60220513904118.7368796 3002546.319563213904122.0118074
#Sta/Elev= 30
 4740.22  151.66 4744.85  151.38 4749.82  151.47 4754.83  150.98 4788.89  150.98
 4799.94  150.36 4804.09   150.7 4811.16  149.98 4817.84  149.98 4847.66  147.93
 4858.65  146.98 4867.07  145.98 4879.92  144.13 4917.69  139.94 4938.49  137.98
 4950.44  137.27 4964.26  137.24 4971.61  137.06 4980.99   137.6 4984.23  137.98
 5008.23  137.98 5054.34  138.98  5074.8  139.98 5100.47  141.88 5111.97  142.89
 5177.61  149.87 5199.96  152.98 5211.29  153.98  5241.4  153.98 5253.52  153.48
#Mann= 3 , 0 , 0
 4740.22     .06       0 4817.84     .04       0 5177.61     .04       0
Bank Sta=4817.84,5177.61
Exp/Cntr=0.3,0.1

Type RM Length L Ch R = 1 ,9931.9  ,287.92,269.9,261.11
BEGIN DESCRIPTION:
K150-00-00-S3_UNNAMED RD - DS - XS1
END DESCRIPTION:
XS GIS Cut Line= 6
  3001895.10137713904564.9052786 3002087.092135213904569.5371591
 3002281.759724913904569.5371591 3002550.025592613904577.9009875
 3002755.0579909 13904581.009249 3002997.099501613904580.1759173
#Sta/Elev= 30
 4571.09   150.7  4642.5  151.11  4723.5  150.98 4765.02  150.13 4770.65  149.98
 4799.14  145.91  4818.1  142.98 4832.98  139.98 4865.23  137.98 4871.38  136.98
 4876.26   135.7 4884.46  132.98 4891.26  129.98 4897.13  128.98 5145.04  128.98
 5150.26   129.6 5163.36  129.98 5186.16  138.98 5204.54  140.98 5215.63  142.98
 5237.06  145.98 5240.81   146.1 5244.52  146.98 5267.77  149.98 5270.45  149.98
 5272.16  148.98 5272.96  148.98 5374.75   149.5 5478.25  151.36 5673.31  151.98
#Mann= 3 , 0 , 0
 4571.09     .06       0 4765.02     .04       0 5267.77     .06       0
Bank Sta=4765.02,5267.77
Exp/Cntr=0.3,0.1

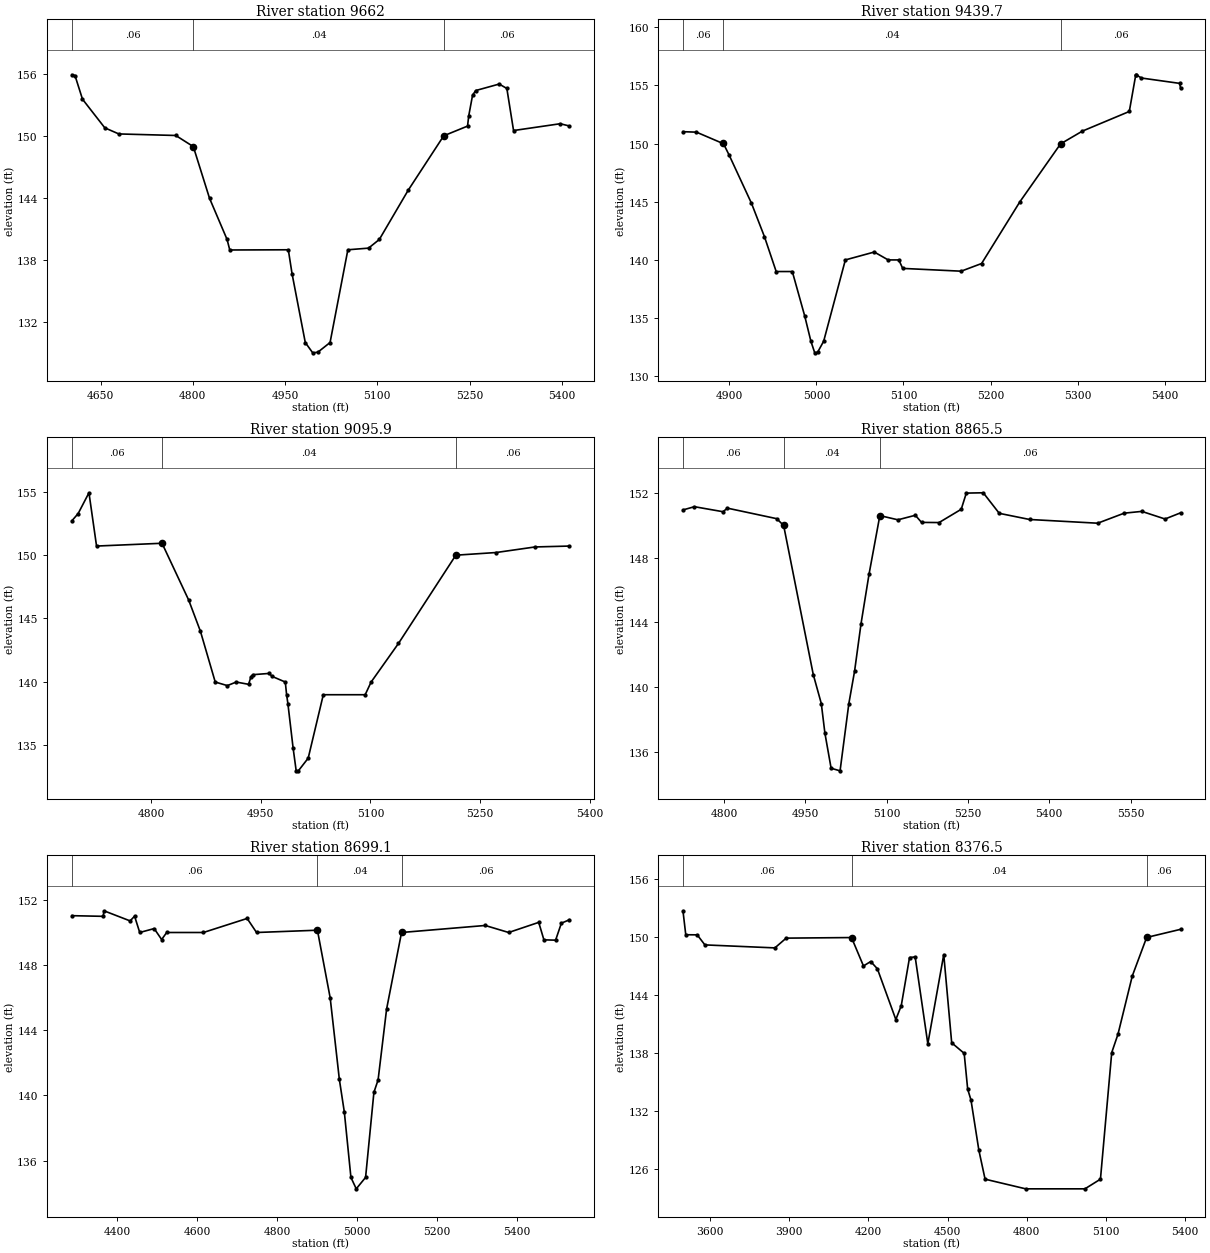
Type RM Length L Ch R = 1 ,9662    ,319.47,222.3,124.16
BEGIN DESCRIPTION:
Cross Section K150-00-00-X6
END DESCRIPTION:
XS GIS Cut Line= 6
  3001911.20534713904854.7780584  3002090.09901913904848.2196726
 3002098.159370313904847.9240695 3002194.714623413904844.3843784
 3002550.025592613904830.3588159 3002719.628927913904819.3493235
#Sta/Elev= 30
 4603.25  155.96 4608.33  155.89 4620.54  153.59 4656.86  150.81 4679.64  150.22
 4772.27  150.07 4800.79  148.99 4827.14  143.98 4855.69  139.98 4860.08  138.96
 4955.29  138.98 4961.39  136.65 4982.89  129.98    4995  128.98 5003.28  129.04
 5023.19  129.98 5052.14  138.98 5085.76  139.14  5103.3  139.98 5150.07  144.74
 5208.05 150.039 5246.78  150.98 5248.72  151.98 5254.96  153.98 5260.03  154.43
 5298.26  155.06 5310.71  154.63  5321.6  150.55 5397.48  151.21  5412.5  150.99
#Mann= 3 , 0 , 0
 4603.25     .06       0 4800.79     .04       0 5208.05     .06       0
Bank Sta=4800.79,5208.05
Exp/Cntr=0.3,0.1

Type RM Length L Ch R = 1 ,9439.7  ,224.9,343.8,355.01
BEGIN DESCRIPTION:
Cross Section K150-00-00-X6.
END DESCRIPTION:
XS GIS Cut Line= 6
   3002118.4211413905122.2899906  3002203.827138 13905056.772077
 3002247.514386613905043.2645581 3002379.630264113905006.2400258
 3002482.9430496 13904974.870666 3002646.547709213904918.3130363
#Sta/Elev= 30
 4846.65  151.02 4862.17  150.98 4892.09  150.02 4893.26  149.98 4899.87  148.98
 4925.36  144.86 4940.28  141.98 4953.76  138.98 4972.28  138.98 4986.55  135.15
 4993.63  132.98 4998.05  131.98 5001.35  132.03 5008.31  132.98 5033.23  139.98
 5066.46  140.66 5082.43  139.98 5094.66  139.98  5099.1  139.25 5166.27  139.01
 5189.75  139.67  5233.7  144.98 5280.46  149.97 5305.54  151.07 5359.44  152.76
 5366.84   155.9 5367.31  155.92 5373.43  155.64 5417.28  155.18 5418.31  154.78
#Mann= 3 , 0 , 0
 4846.65     .06       0 4892.09     .04       0 5280.46     .06       0
Bank Sta=4892.09,5280.46
Exp/Cntr=0.3,0.1

Type RM Length L Ch R = 1 ,9095.9  ,434.82,230.4,227.9
BEGIN DESCRIPTION:
Cross Section K150-00-00-X6
END DESCRIPTION:
XS GIS Cut Line= 6
  3002101.04912813905312.0337056 3002213.3018566  13905312.90936
 3002305.070701913905321.3968758 3002494.610677113905316.3663741
  3002562.06657913905311.3762266 3002775.528422413905265.1584712
#Sta/Elev= 30
 4691.96  152.69 4700.55  153.26 4715.34   154.9 4725.71   150.7 4815.22  150.92
 4851.66  146.44  4867.7  143.98 4887.93  139.98 4904.45   139.7 4916.63  139.98
 4933.52   139.8 4936.85  140.41 4939.21  140.56 4961.77  140.66 4965.49  140.43
 4983.68  139.98 4985.48  138.98 4987.28  138.26 4994.29  134.81 4998.57  132.98
 5001.53  132.98 5014.99  133.98 5035.63  138.98 5092.87  138.98 5100.98  139.98
 5138.34  143.02 5216.77  149.98 5271.82  150.19 5325.12  150.63 5372.05   150.7
#Mann= 3 , 0 , 0
 4691.96     .06       0 4815.22     .04       0 5216.77     .06       0
Bank Sta=4815.22,5216.77
Exp/Cntr=0.3,0.1

Type RM Length L Ch R = 1 ,8865.5  ,181.18,166.4,175.34
XS GIS Cut Line= 6
  3002141.83644813905705.5174986 3002275.714133313905625.8801907
 3002311.793785613905601.4192816 3002437.068797513905516.4873649
 3002527.198866613905455.3821721 3002975.771460213905551.1191854
#Sta/Elev= 30
 4724.03  150.94 4745.17  151.14 4797.89  150.83  4806.1  151.05 4897.07   150.4
 4909.84  149.98 4964.52  140.77 4979.32  138.98 4986.03  137.14 4997.46  134.98
 5013.97  134.82  5030.2  138.98 5040.77  140.98 5052.67  143.91 5067.49  146.98
 5087.39  150.59 5120.76  150.33 5152.89  150.61 5164.33  150.17 5196.65  150.16
 5237.56  150.98 5246.96  151.98 5278.24     152 5307.77  150.73 5363.73  150.35
 5489.39  150.12 5538.31  150.74 5570.84  150.85 5613.74  150.38 5642.31  150.76
#Mann= 3 , 0 , 0
 4724.03     .06       0 4909.84     .04       0 5087.39     .06       0
Bank Sta=4909.84,5087.39
Exp/Cntr=0.3,0.1

Type RM Length L Ch R = 1 ,8699.1  ,827.41,322.6,272.68
XS GIS Cut Line= 6
  3001874.475106 13906070.100759 3002314.432559813905806.0868513
 3002469.512302113905693.5208035 3002658.016846413905575.6588345
 3002706.196540113905556.6142531 3002971.697321413905559.6841289
#Sta/Elev= 30
 4286.23  151.01 4364.67  150.97 4366.42  151.31 4431.89  150.69  4443.1  150.98
 4455.97  149.98 4492.07  150.22 4510.77  149.55 4523.41  149.98  4615.2  149.98
 4724.58  150.84  4748.1  149.98 4900.35  150.12 4932.24  145.98  4955.2  140.98
 4967.66  138.98 4984.12  134.98 4997.43  134.28 5020.79  134.98 5041.61  140.19
 5052.07  140.95 5073.34  145.29 5110.72  149.98    5320  150.41 5378.64  149.98
 5453.79   150.6 5466.75  149.53 5496.01  149.51 5510.43  150.55  5530.6  150.76
#Mann= 3 , 0 , 0
 4286.23     .06       0 4900.35     .04       0 5110.72     .06       0
Bank Sta=4900.35,5110.72
Exp/Cntr=0.3,0.1

Type RM Length L Ch R = 1 ,8376.5  ,488.72,494.7,401.21
XS GIS Cut Line= 6
  3001829.04704713907014.1110101 3002404.314597913906642.9785502
 3002678.294036813905997.0831885 3002742.325732913905852.9394479
 3002864.618795413905718.7264617 3002973.394824613905599.3484197
#Sta/Elev= 30
 3496.68  152.75 3507.34  150.27 3550.74  150.26 3579.83  149.22 3845.32  148.91
 3888.11  149.92 4135.94  149.98 4181.22  147.04 4208.69   147.5 4233.99  146.75
 4303.96   141.5 4324.44  142.92 4355.89  147.91  4377.3  147.98 4425.28  138.99
 4485.68  148.22  4515.8  139.09 4563.13     138 4576.39   134.3 4588.94  133.17
 4618.86  127.97 4642.42  124.98 4796.52  123.98 5021.05  123.98 5079.92  124.98
  5122.7  138.08 5146.31  139.97 5200.72  146.01  5255.1  149.99 5383.63  150.83
#Mann= 3 , 0 , 0
 3496.68     .06       0 4135.94     .04       0  5255.1     .06       0
#XS Ineff= 2 , 0
       0 4485.68  148.22               0
Permanent Ineff=
       F       F
Bank Sta=4135.94,5255.1
Exp/Cntr=0.3,0.1

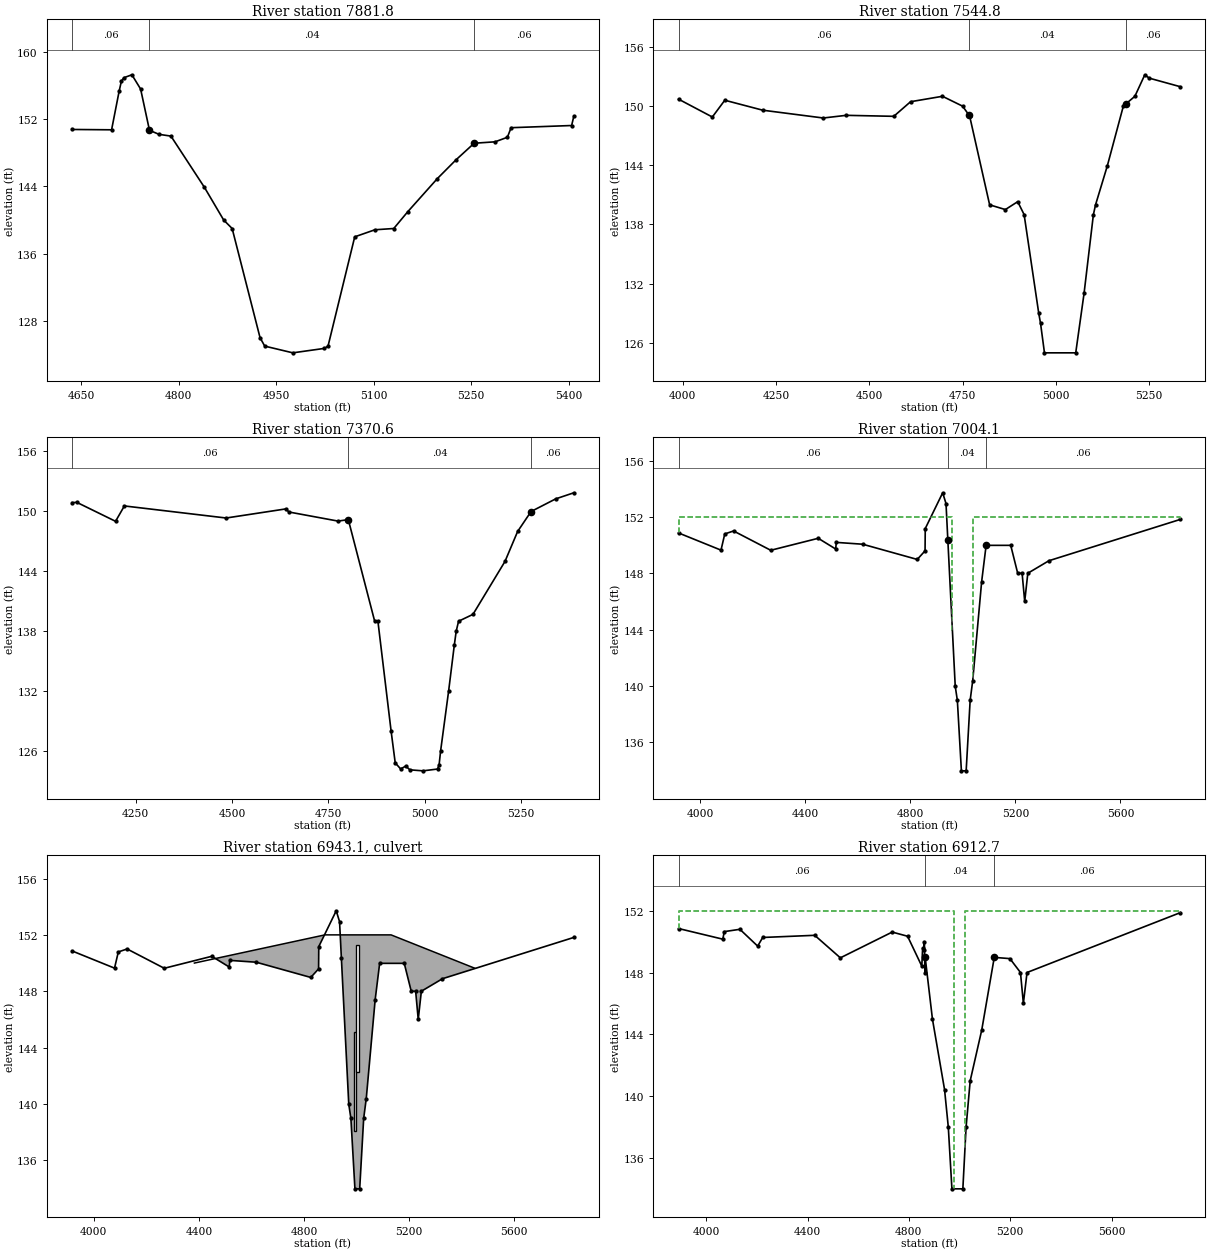
Type RM Length L Ch R = 1 ,7881.8  ,312.24,337,293.22
BEGIN DESCRIPTION:
K150-00-00-S2_UNNAMED RD - US - XS3
END DESCRIPTION:
XS GIS Cut Line= 6
  3002890.78967413906587.0334521 3002952.621244113906445.3388536
 3003065.364128813906186.9738848 3003138.182552713906032.5988655
 3003143.172372113906022.0201465 3003208.562661313905883.3931271
#Sta/Elev= 30
 4635.91  150.77 4696.72  150.73 4708.25  155.29 4711.85  156.54 4715.93  156.94
 4727.96  157.28  4741.4  155.58 4755.02  150.67 4769.72  150.19 4788.05  149.98
 4839.66  143.87 4869.21  139.99 4882.25  138.98 4925.19  125.98 4932.38  124.98
 4975.63  124.18 5024.24  124.71 5029.78  124.98 5070.86  137.99 5101.94  138.83
 5130.92  138.98 5152.48  140.98 5197.85  144.91 5226.64  147.15 5254.63  149.13
 5286.81   149.3 5305.77  149.84 5311.48  150.98 5404.62  151.24 5408.06  152.36
#Mann= 3 , 0 , 0
 4635.91     .06       0 4755.02     .04       0 5254.63     .06       0
Bank Sta=4755.02,5254.63
Exp/Cntr=0.3,0.1

Type RM Length L Ch R = 1 ,7544.8  ,178.13,174.2,151.13
BEGIN DESCRIPTION:
K150-00-00-S2_UNNAMED RD - DS - XS2
END DESCRIPTION:
XS GIS Cut Line= 6
   3003001.5296113907225.6561906 3003199.2510001 13906636.119312
 3003305.528346613906398.9531197 3003363.572521913906282.8614883
 3003466.766213113905999.0831845 3003468.712403513905967.9464357
#Sta/Elev= 30
 3988.52  150.69 4079.06  148.88 4112.49  150.58 4214.16  149.57 4376.33  148.78
 4437.86  149.05 4565.29  148.95 4610.32  150.43  4695.8  150.98  4749.7  149.98
 4766.94  149.07 4768.56  148.98 4822.18  139.98 4864.31   139.5 4897.41   140.3
 4914.59  138.99  4953.8  128.98 4958.55  127.98  4969.1  124.98 5052.88  124.98
 5075.19     131 5100.18  138.98 5105.96  139.98 5137.39  143.91 5180.42  149.98
 5186.35  150.18  5211.4  150.98 5237.93  153.16  5249.7  152.82 5333.16  151.95
#Mann= 3 , 0 , 0
 3988.52     .06       0 4766.94     .04       0 5186.35     .06       0
Bank Sta=4766.94,5186.35
Exp/Cntr=0.3,0.1

Type RM Length L Ch R = 1 ,7370.6  ,384.61,366.5,357.7
BEGIN DESCRIPTION:
K150-00-00-S2_UNNAMED RD - DS - XS1
END DESCRIPTION:
XS GIS Cut Line= 6
   3003118.7170413907247.3575908 3003352.713619713906735.2785625
 3003410.296837913906586.1748581 3003479.471896413906407.0505444
 3003492.564389913906373.1549429 3003610.782001213906043.3901825
#Sta/Elev= 30
 4085.15  150.87 4097.47   150.9 4197.93     149 4220.81  150.54 4484.79  149.33
 4639.12  150.24 4647.93  149.93 4775.17  149.02 4801.65  149.17 4870.04  138.98
 4878.43  138.98 4912.61  127.98 4923.32  124.78 4937.43  124.17 4950.61  124.46
 4961.36  124.08 4995.28  123.98 5033.03  124.16  5037.1  124.57 5041.06  125.98
 5061.83  131.98  5076.7  136.62 5081.49  137.98  5087.6  138.98    5125  139.67
 5208.07  144.98  5240.8  147.98 5275.65  149.98 5339.61  151.25 5386.67  151.86
#Mann= 3 , 0 , 0
 4085.15     .06       0 4801.65     .04       0 5275.65     .06       0
Bank Sta=4801.65,5275.65
Exp/Cntr=0.3,0.1

Type RM Length L Ch R = 1 ,7004.1  ,90.8,91.4,103.04
XS GIS Cut Line= 6
  3003170.800597  13907299.44082 3003743.386394813906554.5207219
  3003807.46172613906467.8388086 3003821.857366513906435.4576398
  3003895.88280913906268.8900596 3004255.869949913905732.6007778
#Sta/Elev= 30
 3917.21  150.86 4078.91  149.64 4093.31  150.79 4126.83     151 4268.37  149.63
 4449.24  150.48  4515.7  149.72 4517.97  150.19 4618.41  150.06 4826.25  148.98
 4856.05  149.59 4856.77  151.17 4923.19  153.71 4935.87  152.94 4942.69  150.39
 4970.96  139.98 4979.05  138.98 4994.43  133.98 5012.56  133.98 5027.76  138.98
 5037.49  140.37 5071.52   147.4  5088.6  149.98 5182.28  149.98 5208.84     148
 5225.64     148 5235.53     146 5247.38     148 5327.92  148.89 5828.18  151.82
#Mann= 3 , 0 , 0
 3917.21     .06       0 4942.69     .04       0  5088.6     .06       0
#XS Ineff= 2 , 0
       0  4960.5     152  5038.5       0     152
Permanent Ineff=
       F       F
Bank Sta=4942.69,5088.6
Exp/Cntr=0.5,0.3

Type RM Length L Ch R = 2 ,6943.1  ,,,
BEGIN DESCRIPTION:
Creekside Crossing Drive
END DESCRIPTION:
Bridge Culvert--1,0,-1,-1, 0
Deck Dist Width WeirC Skew NumUp NumDn MinLoCord MaxHiCord MaxSubmerge Is_Ogee
25,48,2.6,0, 4, 4, , , 0.95, 0, 0,0,,
 4383.08 4880.06 5132.07 5450.02
     150     152     152  149.64
     134
 4358.77 4855.75 5152.01 5434.11
  150.49     152     152  149.02
             134     134
BR Coef=-1 , 0 , 0 ,, 0 ,,,0.8,-1,,0,
WSPro=,,,, 1 ,,,, 0 ,,,, 0 ,,,,-1 ,-1 ,-1 , 0 , 0 , 0 , 0 , 0
Culvert=2,7,9,48,0.013,0.5,1,8,1,138.1,4995,137.6,4995,Culvert #1  , 0 ,25
Culvert Bottom n=0.013
Culvert=2,9,9,48,0.013,0.5,1,8,1,142.3,5004,142,5004,Culvert #2  , 0 ,25
Culvert Bottom n=0.013
Culvert Bottom Depth=0.375
Culvert Depth Blocked=0.375
BC Design=,, 0 ,, 0 ,,,,,,
BC HTab HWMax=152

Type RM Length L Ch R = 1 ,6912.7  ,55.48,72.8,88.98
BEGIN DESCRIPTION:
upstream of inline weir
END DESCRIPTION:
XS GIS Cut Line= 6
  3003174.05551213907329.8229771 3003809.754700413906606.0504745
  3003818.96957713906601.7594726 3003857.704735713906554.2306962
  3003992.32356113906316.7016437 3004361.1217079 13905754.302178
#Sta/Elev= 30
 3891.02  150.85 4065.68  150.16 4071.63  150.65 4133.17   150.8 4203.35  149.71
 4223.22  150.27 4428.53  150.41 4529.65  148.95 4734.28  150.62 4794.96  150.35
 4851.16  148.41 4854.32  149.57 4860.54  149.43  4860.9     150 4863.59     148
 4864.43  148.98 4893.09  144.98 4940.89  140.41 4955.69  137.98 4969.92  133.98
 5013.12  133.98 5025.87  137.98 5042.03  140.98 5087.72  144.28 5137.07  148.98
 5198.82   148.9 5240.48     148 5251.96     146 5266.38     148 5871.38  151.88
#Mann= 3 , 0 , 0
 3891.02     .06       0 4864.43     .04       0 5137.07     .06       0
#XS Ineff= 2 , 0
       0  4977.5     152  5021.5       0     152
Permanent Ineff=
       F       F
Bank Sta=4864.43,5137.07
Exp/Cntr=0.5,0.3

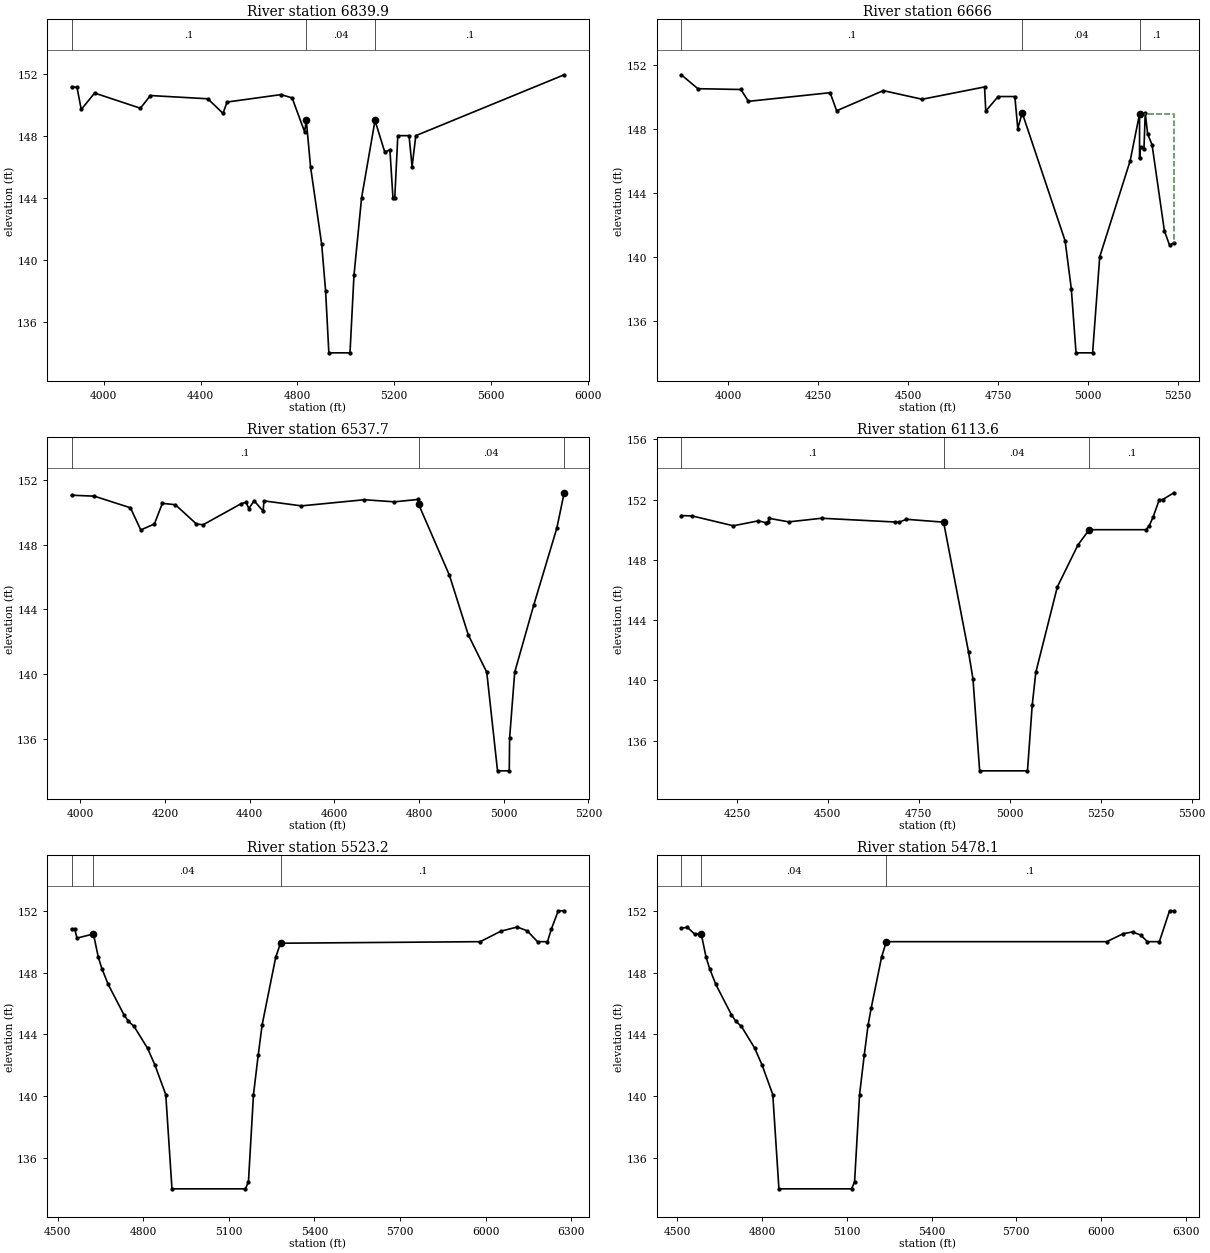
Type RM Length L Ch R = 1 ,6839.9  ,45.33,173.9,292.11
XS GIS Cut Line= 6
  3003191.41669813907358.0348629 3003783.864660313906659.2501712
 3003830.023032613906656.3154658 3003888.655789313906617.0071455
 3004058.0012511 13906391.989879 3004447.927308613905786.8542782
#Sta/Elev= 30
 3867.14  151.16 3889.59  151.11 3906.91  149.69 3962.29  150.75 4151.29  149.77
 4192.49  150.59 4429.63  150.38 4492.43  149.44 4509.34  150.17 4731.77  150.65
 4777.89  150.44 4829.52  148.25 4836.57  148.98 4854.21  145.97 4900.11  140.98
 4916.21  137.98 4929.67  133.98 5017.03  133.98 5033.42  138.98 5064.83  143.98
 5120.43  148.98 5160.56  146.94 5181.88  147.09 5194.39     144    5202     144
  5214.6     148 5260.87     148 5273.54     146 5288.87     148 5901.76  151.93
#Mann= 3 , 0 , 0
 3867.14      .1       0 4836.57     .04       0 5120.43      .1       0
Bank Sta=4836.57,5120.43
Exp/Cntr=0.3,0.1

Type RM Length L Ch R = 1 ,6666    ,140.58,128.3,123.3
XS GIS Cut Line= 6
  3003217.45831213907366.7152917 3003750.498585313906709.5361599
 3003845.159485213906699.8941188 3003863.7037395 13906698.005015
 3004076.0858606   13906676.3712 3004270.617295713906656.5559509
#Sta/Elev= 30
 3869.29  151.36 3915.43  150.49 4034.81  150.44 4055.92   149.7 4282.88  150.24
 4301.04  149.11 4430.57  150.37 4538.67  149.83 4712.13   150.6 4715.47  149.09
 4749.84     150 4796.23     150 4804.47     148 4816.75  148.98 4935.99  140.98
 4953.21  137.98 4966.34  133.98 5012.41  133.98 5032.15  139.98 5116.72  145.98
 5142.84  148.91 5142.87  146.14 5145.71  146.82 5155.12  146.73 5158.67  148.98
 5165.37  147.66 5177.68  146.98 5211.86  141.61 5226.54  140.69 5238.28  140.87
#Mann= 3 , 0 , 0
 3869.29      .1       0 4816.75     .04       0 5142.84      .1       0
#XS Ineff= 2 , 0
       0                 5142.84       0  148.91
Permanent Ineff=
       F       F
Bank Sta=4816.75,5142.84
Exp/Cntr=0.3,0.1

Type RM Length L Ch R = 1 ,6537.7  ,346,424.1,467
XS GIS Cut Line= 6
  3003254.82831613907369.9272276 3003699.706692113906877.3055094
 3003850.691626413906841.6625361 3004067.073411513906797.8660357
 3004141.767487813906782.7479557 3004187.668642713906773.4572919
#Sta/Elev= 30
 3979.94  151.05 4033.64  150.99 4118.83  150.27 4143.21   148.9 4175.39  149.27
 4194.18  150.55 4224.91  150.46 4274.48  149.27 4290.23  149.22 4379.77  150.52
 4392.04  150.61 4398.21  150.22 4410.67  150.71 4432.06  150.06 4433.92   150.7
 4522.33  150.39 4670.92  150.77 4741.83  150.64 4798.69  150.79 4798.84   150.5
 4871.54  146.11  4916.3  142.41 4959.88   140.1  4985.3     134    5013     134
 5013.84  136.03 5025.84   140.1 5070.76  144.25 5125.17     149 5142.67   151.2
#Mann= 3 , 0 , 0
 3979.94      .1       0 4798.84     .04       0 5142.67      .1       0
Bank Sta=4798.84,5142.67
Exp/Cntr=0.3,0.1

Type RM Length L Ch R = 1 ,6113.6  ,720,590.4,490
XS GIS Cut Line= 6
  3003283.03987413907389.4583565 3003545.626947813907144.2327971
 3003905.4717006 13907179.720587 3004085.990040313907201.8501359
 3004302.403321413907230.2116277 3004533.039999213907261.4202267
#Sta/Elev= 28
 4097.41  150.94 4127.76  150.91 4240.38  150.26  4309.5  150.59 4330.33  150.46
 4336.26  150.54 4339.49  150.75  4392.8  150.52 4482.97  150.76 4685.33  150.51
 4696.88  150.51  4716.3  150.69 4818.29   150.5 4886.83  141.88 4899.01   140.1
 4917.36     134 5048.81     134  5061.8  138.35 5071.66  140.53 5130.93  146.21
 5187.83     149 5218.42     150 5374.03     150 5382.75  150.23 5393.92  150.83
 5411.11     152 5420.41     152 5451.16  152.45
#Mann= 3 , 0 , 0
 4097.41      .1       0 4818.29     .04       0 5218.42      .1       0
Bank Sta=4818.29,5218.42
Exp/Cntr=0.3,0.1

Type RM Length L Ch R = 1 ,5523.2  ,57,45.1,57
XS GIS Cut Line= 6
  3003741.99269613907848.7235141 3003817.733030913907859.6595158
 3003924.880782513907853.6116276 3004391.376240613907710.4760871
 3004444.300019213907685.9515299 3005297.880989213907173.6077383
#Sta/Elev= 30
  4549.1  150.82 4559.57  150.84 4567.98  150.23 4625.62   150.5 4642.57     149
 4655.11  148.26 4677.32  147.23 4732.21  145.28 4747.48  144.86  4768.1  144.51
 4815.12   143.1 4841.08  142.01 4878.95   140.1 4900.65     134 5157.92     134
 5168.58  134.45 5186.27   140.1  5202.9  142.67 5216.62  144.62 5264.23     149
 5280.95   149.9 5980.77     150 6053.02  150.68  6110.4  150.95 6145.35   150.7
 6181.27     150 6216.18     150 6230.06  150.83 6253.98     152 6274.77     152
#Mann= 3 , 0 , 0
  4549.1      .1       0 4625.62     .04       0 5280.95      .1       0
Bank Sta=4625.62,5280.95
Exp/Cntr=0.3,0.1

Type RM Length L Ch R = 1 ,5478.1  ,30,34,30
XS GIS Cut Line= 6
  3003723.79096113907879.4367072 3003796.383336113907891.5072211
 3003923.541874413907882.0974631 3004235.110148913907806.9001069
 3004394.2600931  13907723.18013 3005292.4771286 13907192.972529
#Sta/Elev= 30
 4513.54  150.87 4534.81  150.93 4560.53   150.5 4584.22   150.5 4601.17     149
 4613.71  148.26 4635.92  147.23 4690.81  145.28 4706.08  144.86  4726.7  144.51
 4773.72   143.1 4799.68  142.01 4837.55   140.1 4859.25     134 5116.52     134
 5127.18  134.45 5144.87   140.1  5161.5  142.67 5175.22  144.62 5185.93  145.69
 5222.83     149 5239.55     150    6020     150 6078.99  150.52 6112.11  150.63
 6140.08  150.43 6164.42     150 6206.62     150 6242.69     152 6258.04     152
#Mann= 3 , 0 , 0
 4513.54      .1       0 4584.22     .04       0 5239.55      .1       0
Bank Sta=4584.22,5239.55
Exp/Cntr=0.3,0.1

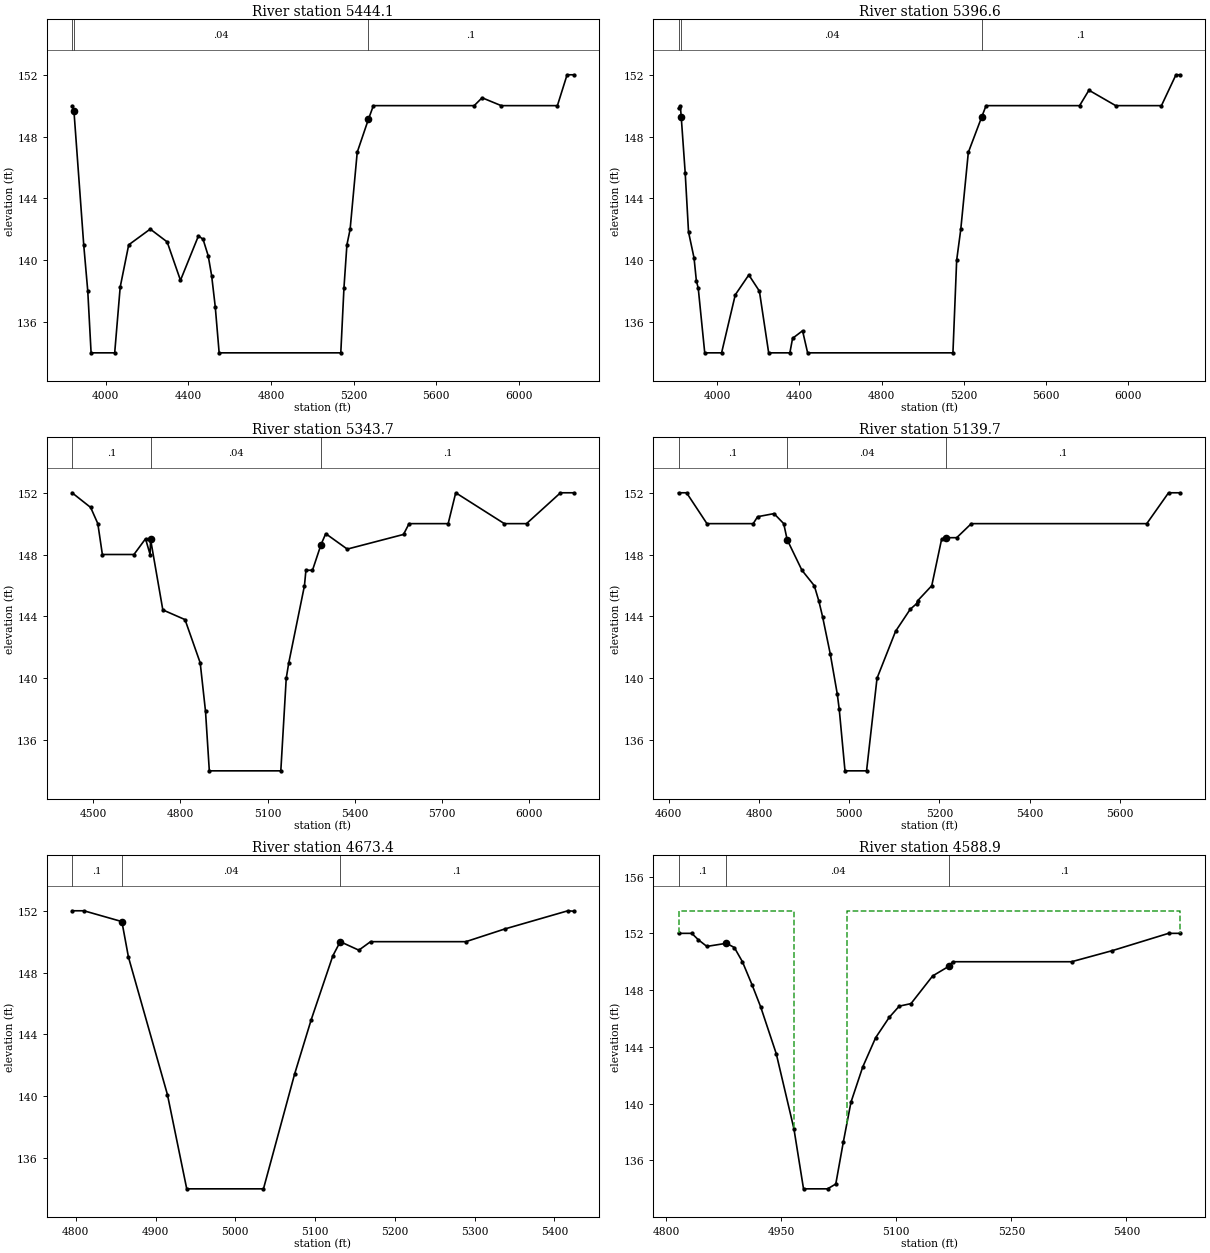
Type RM Length L Ch R = 1 ,5444.1  ,43,47.5,43
XS GIS Cut Line= 6
  3003098.74824813908142.6497635 3003760.282030313907985.3620203
  3004247.26005913907834.3298421 3004399.590134913907731.7998634
 3004644.886232213907589.4691113 3005313.693949713907206.8324094
#Sta/Elev= 30
 3837.76  149.99 3846.94  149.63 3894.14  140.98 3913.74  137.98 3929.78  133.98
 4043.97  133.98 4070.56  138.24 4111.75  140.98 4215.92     142 4297.73  141.17
 4362.21  138.68 4449.19  141.56 4471.48  141.34 4496.36  140.27 4513.01  138.98
 4530.45  136.97 4549.31  133.98 5137.81  133.98 5153.17   138.2 5167.39  140.98
 5182.89  141.98 5217.29  146.98 5271.25  149.11 5295.57     150 5783.17     150
 5821.39  150.51 5914.04     150  6185.7     150 6232.54     152 6265.35     152
#Mann= 3 , 0 , 0
 3837.76      .1       0 3846.94     .04       0 5271.25      .1       0
Bank Sta=3846.94,5271.25
Exp/Cntr=0.3,0.1

Type RM Length L Ch R = 1 ,5396.6  ,50,52.9,50
XS GIS Cut Line= 6
  3003114.93981713908228.2325976 3003755.655727213908047.8143232
 3004264.670129113907873.6499734  3004405.99989913907738.5400074
 3004648.600463613907598.1354326 3005316.985281713907234.6679837
#Sta/Elev= 30
 3812.56  149.82 3821.41  149.98 3825.74  149.26 3844.98  145.64 3861.18  141.81
 3887.98  140.13 3899.18  138.66 3908.47  138.16 3939.97  133.98 4021.93  133.98
 4088.45  137.74 4154.32  139.03 4205.77  137.98  4250.9  133.98 4354.01  133.98
 4367.13  134.92 4415.71  135.41 4440.38  133.98 5147.01  133.98 5165.16  139.98
 5185.12  141.98 5221.86  146.97 5286.83  149.26 5308.07     150 5762.95     150
 5808.43     151 5938.53     150 6161.02     150 6231.63     152 6252.86     152
#Mann= 3 , 0 , 0
 3812.56      .1       0 3825.74     .04       0 5286.83      .1       0
Bank Sta=3825.74,5286.83
Exp/Cntr=0.3,0.1

Type RM Length L Ch R = 1 ,5343.7  ,204,204,204
XS GIS Cut Line= 6
  3003965.63102913908381.3464646 3004122.077566613908166.5069992
 3004213.459273613908007.2415697 3004390.903144413907794.3476386
 3004500.549906713907700.5348341 3005304.172971413907410.8602166
#Sta/Elev= 30
 4427.75     152 4491.64  151.05 4516.32     150 4531.95     148 4640.55     148
 4680.42  149.02 4696.06     148 4697.74  148.98 4739.86  144.41 4816.19  143.78
 4868.39  140.98 4886.67  137.84 4899.78  133.98 5145.64  133.98 5164.29  139.98
    5173  140.98 5226.97  145.98 5231.99  146.98 5254.58  146.98 5283.87  148.64
  5300.1  149.35 5374.18  148.35 5567.59   149.3 5586.71     150  5721.2     150
 5747.18     152 5914.37     150 5990.63     150 6107.47     152 6153.46     152
#Mann= 3 , 0 , 0
 4427.75      .1       0 4697.74     .04       0 5283.87      .1       0
#XS Ineff= 2 , 0
       0 4680.42  149.02               0
Permanent Ineff=
       F       F
Bank Sta=4697.74,5283.87
Exp/Cntr=0.3,0.1

Type RM Length L Ch R = 1 ,5139.7  ,390,466.3,507
XS GIS Cut Line= 6
   3004209.3378913908336.2074472 3004360.8497268 13908149.029672
 3004496.897683113907985.7964026 3004544.486170613907928.6990759
 3004609.577575813907919.9792771 3005127.3065272 13907882.648315
#Sta/Elev= 30
 4621.77     152 4639.57     152 4684.75     150 4787.28     150 4797.07  150.45
 4833.49  150.65 4854.96     150 4862.58  148.96 4895.32  146.98  4922.7  145.98
 4932.87  144.98    4941  143.98 4958.18  141.55 4973.55  138.98 4977.99  137.98
 4990.78  133.98 5038.61  133.98 5061.79  139.98 5102.83  143.02 5135.33  144.45
  5149.4  144.81 5152.11  145.01 5183.16  145.98 5204.87  148.98 5215.08  149.09
 5238.44  149.09 5270.81     150 5659.77     150 5708.05     152 5734.16     152
#Mann= 3 , 0 , 0
 4621.77      .1       0 4862.58     .04       0 5215.08      .1       0
#XS Ineff= 2 , 0
       0 4833.49  150.65               0
Permanent Ineff=
       F       F
Bank Sta=4862.58,5215.08
Exp/Cntr=0.3,0.1

Type RM Length L Ch R = 1 ,4673.4  ,70,84.5,100
XS GIS Cut Line= 6
  3004539.19877913908498.9679485 3004595.611068313908472.1192489
 3004609.795751213908464.7317965 3004660.860609713908438.1376896
 3004838.434073513908345.6582157  3005094.75442713908203.8291031
#Sta/Elev= 17
 4795.27     152 4810.14     152 4857.74   151.3 4865.97     149 4914.85   140.1
 4939.06     134 5035.26     134 5074.32  141.43 5095.07  144.94 5122.21  149.08
 5131.52     150 5154.85  149.45 5169.56     150 5289.02     150 5337.71  150.82
 5416.98     152 5424.47  151.97
#Mann= 3 , 0 , 0
 4795.27      .1       0 4857.74     .04       0 5131.52      .1       0
Bank Sta=4857.74,5131.52
Exp/Cntr=0.3,0.1

Type RM Length L Ch R = 1 ,4588.9  ,131,131.7,131
BEGIN DESCRIPTION:
Upstream XS of bridge
END DESCRIPTION:
XS GIS Cut Line= 6
  3004586.94179413908548.8812345 3004645.569957913908527.4701881
 3004859.293611813908442.1547419 3004871.549164713908437.2659721
 3004915.230179713908419.8296553 3005194.580670913908307.9955614
#Sta/Elev= 28
 4816.46     152 4833.69     152 4842.41  151.54 4853.34  151.08 4878.88   151.3
 4889.17     151 4899.68     150 4912.56  148.33 4923.46  146.82  4943.7  143.53
 4966.75  138.24 4979.28     134 5010.57     134  5021.3  134.34 5031.02  137.27
 5041.07   140.1 5056.37  142.58 5073.24  144.65 5090.92  146.08 5103.93  146.87
 5119.28  147.05 5147.51     149 5169.23   149.7 5173.39     150 5328.46     150
 5381.38  150.78 5454.79     152 5470.13     152
#Mann= 3 , 0 , 0
 4816.46      .1       0 4878.88     .04       0 5169.23      .1       0
#XS Ineff= 2 , 0
       0  4966.6  153.59  5035.6       0  153.59
Permanent Ineff=
       F       F
Bank Sta=4878.88,5169.23
Exp/Cntr=0.5,0.3