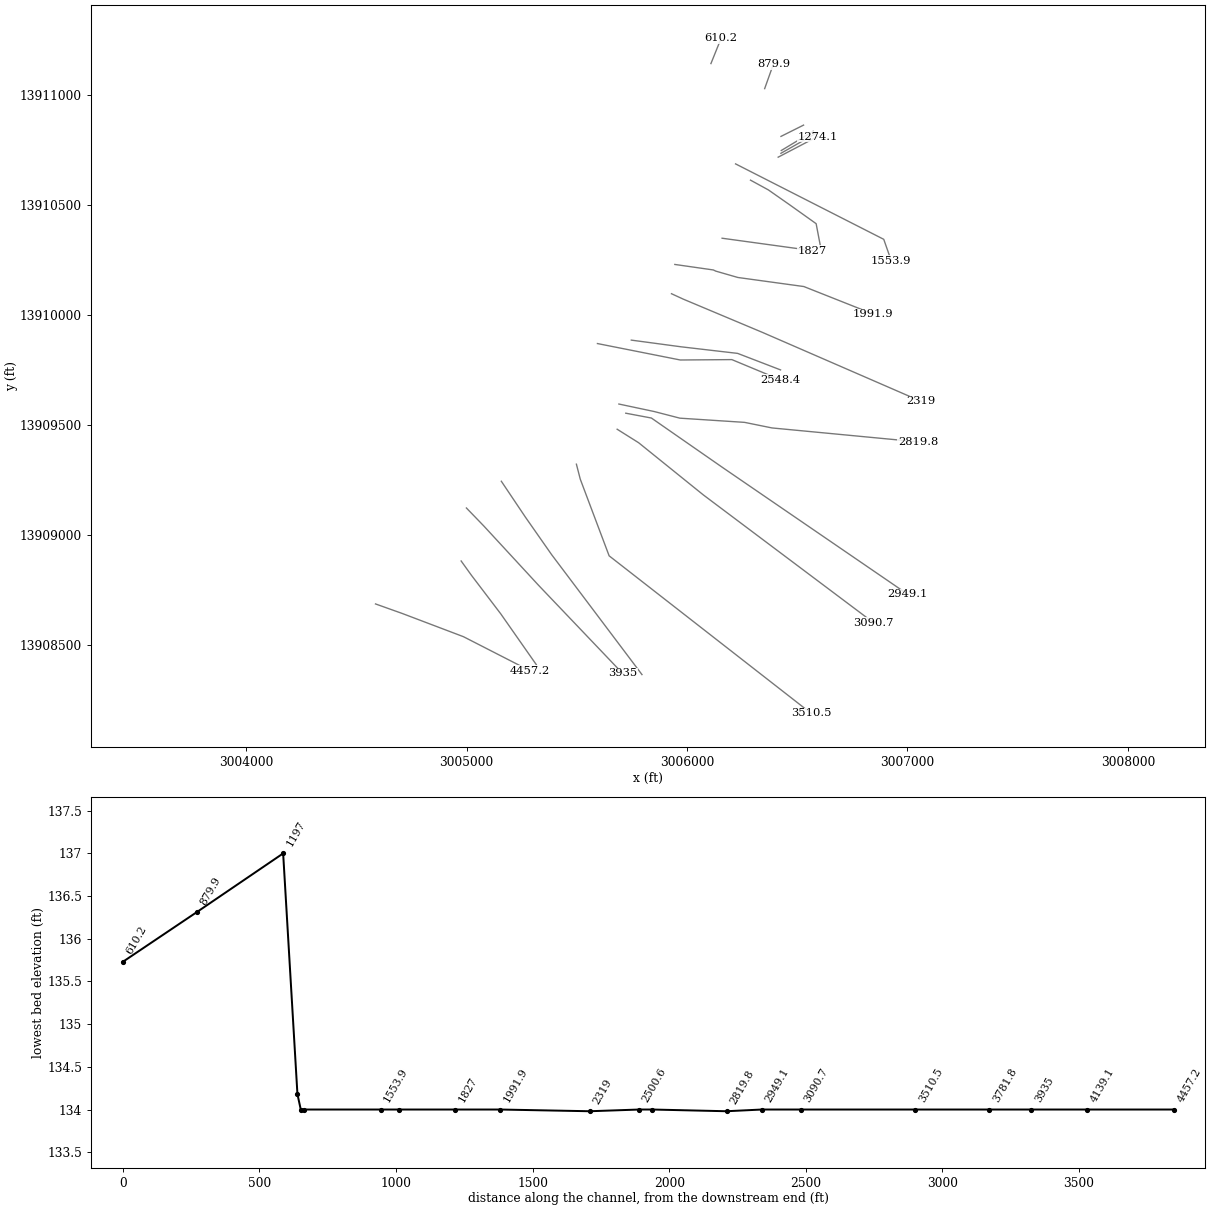
HEC-RAS study K150-00-00.prj: K150-00-00

--- K150-00-00.g01 (geometry) --- (continued)

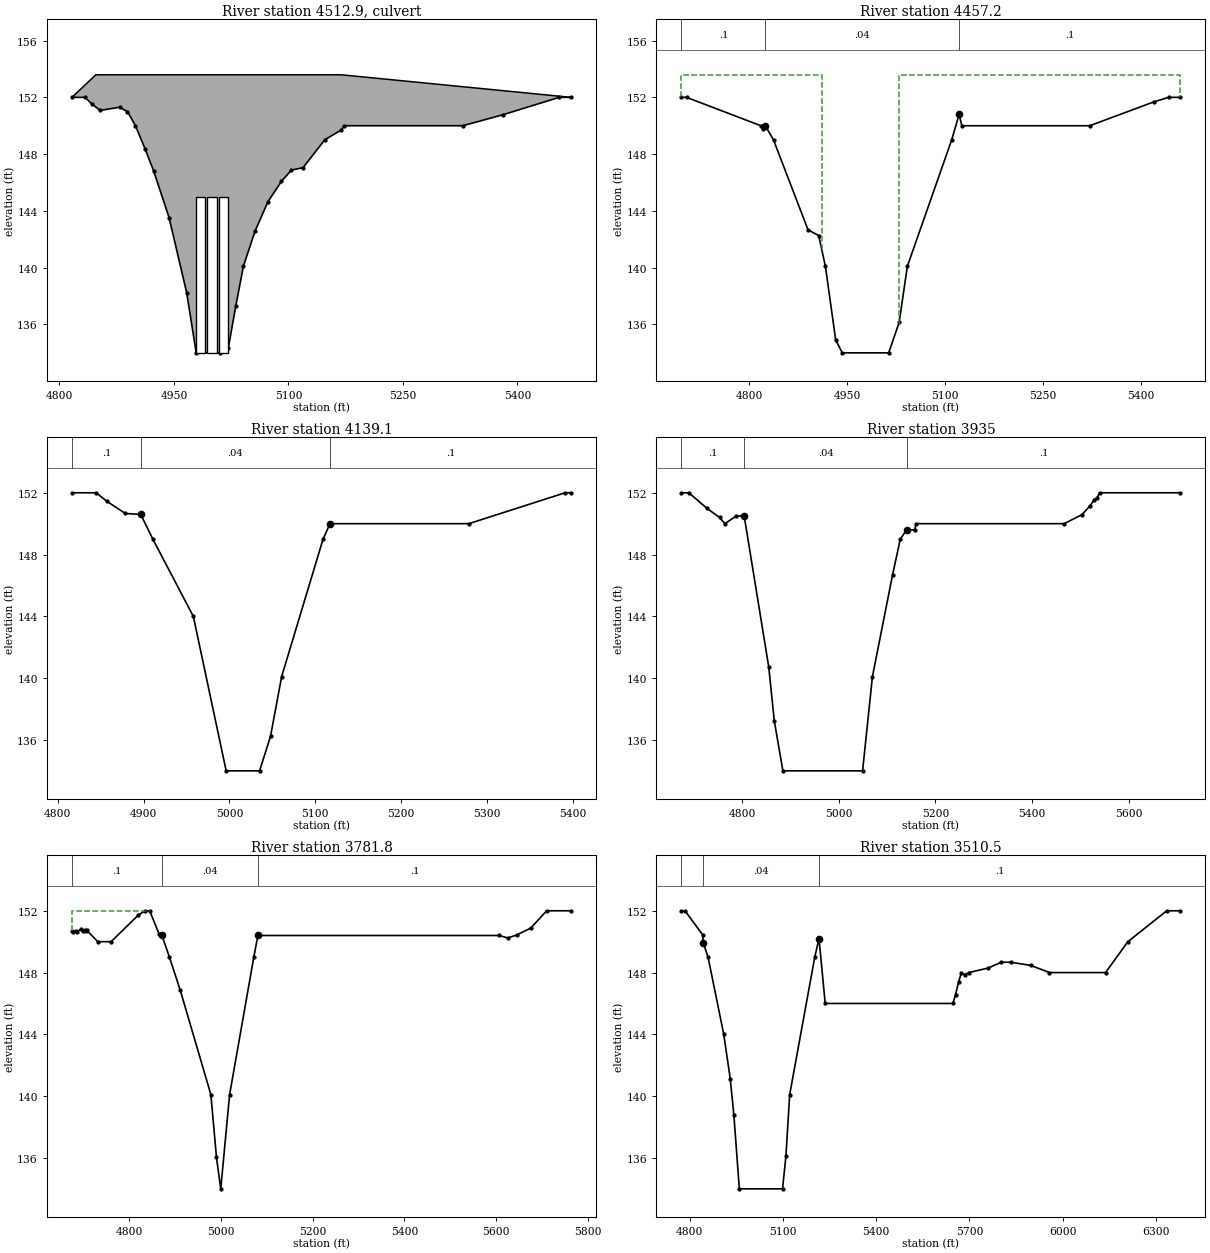
Type RM Length L Ch R = 2 ,4512.9  ,,,
BEGIN DESCRIPTION:
Equalizer "B"
END DESCRIPTION:
Bridge Culvert--1,0,-1,-1, 0
Deck Dist Width WeirC Skew NumUp NumDn MinLoCord MaxHiCord MaxSubmerge Is_Ogee
15,60,2.6,0, 24, 15, , , 0.95, 0, 0,0,,
 4816.52 4847.74 4855.29 4865.31  4875.6 4886.11 4898.99 4909.89 4930.13 4953.18
 4965.71 4995.03    4997 5007.73 5017.45  5027.5  5042.8 5059.67 5077.35 5090.36
 5105.71 5133.94 5169.23 5470.13
     152  153.59  153.59  153.59  153.59  153.59  153.59  153.59  153.59  153.59
  153.59  153.59  153.59  153.59  153.59  153.59  153.59  153.59  153.59  153.59
  153.59  153.59  153.59     152
          133.09  133.09  133.09  133.09  133.09  133.09  133.09  133.09  133.09
  133.09  133.09  133.09  133.09  133.09  133.09  133.09  133.09  133.09  133.09
  133.09  133.09  133.09
 4695.76 4824.42 4845.55 4898.43 4914.85 4925.08  4940.9 4950.99  5008.6 5022.18
 5038.19 5050.81 5118.76 5130.21 5460.64
     152  153.59  153.59  153.59  153.59  153.59  153.59  153.59  153.59  153.59
  153.59  153.59  153.59  153.59     152
          133.09  133.09  133.09  133.09  133.09  133.09  133.09  133.09  133.09
  133.09  133.09  133.09  133.09
BR Coef=-1 , 0 , 0 ,, 0 ,,,0.8,-1,,0,
WSPro=,,,, 1 ,,,, 0 ,,,, 0 ,,,,-1 ,-1 ,-1 , 0 , 0 , 0 , 0 , 0
Multiple Barrel Culv=2,11,12,60,0.013,0.5,1,8,1,134,134, 3,Culvert #1  , 0 ,15
    4985  4954.6    5000  4969.6    5015  4984.6
Culvert Bottom n=0.013
BC Design=,, 0 ,, 0 ,,,,,,
BC HTab Sub Flow Curves= 50
BC HTab Sub Flow Pts= 40
BC HTab HWMax=153
BC HTab TWMax=152.5
BC HTab MaxFlow=2500

Type RM Length L Ch R = 1 ,4457.2  ,400,318.1,229
BEGIN DESCRIPTION:
Downstream XS of bridge
END DESCRIPTION:
XS GIS Cut Line= 6
  3004586.94179413908685.5997931 3004708.104609713908642.3059164
 3004712.822448113908640.5122848 3004809.925928413908603.5920831
 3004985.893424213908536.6873612 3005287.896757213908381.7805188
#Sta/Elev= 21
 4695.76     152 4703.54     152 4817.61     150 4820.18   149.8 4824.42     150
 4836.95     149 4889.83  142.67 4906.25  142.26 4916.48   140.1  4932.3  134.91
 4942.39     134 5013.58     134 5029.59  136.14 5042.21   140.1 5110.16     149
 5121.61   150.8 5125.77     150 5321.85     150 5420.12  151.68  5442.8     152
 5461.03     152
#Mann= 3 , 0 , 0
 4695.76      .1       0 4824.42     .04       0 5121.61      .1       0
#XS Ineff= 2 , 0
       0  4911.2  153.59  5028.8       0  153.59
Permanent Ineff=
       F       F
Bank Sta=4824.42,5121.61
Exp/Cntr=0.5,0.3

Type RM Length L Ch R = 1 ,4139.1  ,94,204.1,302
XS GIS Cut Line= 6
  3004975.39672613908880.9123946  3005022.09315513908815.8072098
 3005032.779485313908801.7278416  3005066.92771113908756.7289159
 3005155.422284613908640.1212095 3005316.108643113908409.9920766
#Sta/Elev= 16
 4816.57     152 4844.87     152 4857.19  151.45  4878.8  150.66 4896.69   150.6
 4910.84     149    4958     144 4996.25     134 5035.19     134 5047.95  136.24
 5060.88   140.1 5109.14     149 5117.24     150 5278.97     150 5391.08     152
 5397.92     152
#Mann= 3 , 0 , 0
 4816.57      .1       0 4896.69     .04       0 5117.24      .1       0
Bank Sta=4896.69,5117.24
Exp/Cntr=0.3,0.1

Type RM Length L Ch R = 1 ,3935    ,300,153.2,117
XS GIS Cut Line= 6
  3004999.26839713909121.7977396 3005077.888975113909040.3402253
 3005221.370643613908884.5836471  3005324.03349613908773.1383319
 3005327.553830113908769.3171453  3005706.73351813908370.9298187
#Sta/Elev= 24
 4675.02     152 4690.33     152 4727.79  150.99 4753.87   150.4  4764.9     150
 4788.23   150.5 4804.73   150.5  4855.5  140.72 4866.96  137.24 4884.74     134
 5049.52     134 5069.87   140.1 5111.44  146.68 5127.46     149 5140.66   149.6
 5157.16   149.6 5160.14     150  5466.2     150 5503.35  150.59 5519.51  151.15
 5528.87  151.56 5534.47  151.68 5539.33     152 5706.71     152
#Mann= 3 , 0 , 0
 4675.02      .1       0 4804.73     .04       0 5140.66      .1       0
Bank Sta=4804.73,5140.66
Exp/Cntr=0.3,0.1

Type RM Length L Ch R = 1 ,3781.8  ,311,271.3,250
BEGIN DESCRIPTION:
narrow neck in diversion channel
END DESCRIPTION:
XS GIS Cut Line= 6
  3005157.68835613909243.3253836 3005266.687482113909080.5839112
 3005307.380970213909022.2395397 3005343.109245213908971.0145766
 3005386.227269213908909.1941621 3005795.709389913908364.4193331
#Sta/Elev= 30
 4676.01  150.71 4679.05  150.65 4684.52  150.71 4686.04  150.62 4694.74  150.79
 4699.31  150.67 4704.88  150.76 4706.07  150.69 4708.35  150.73 4732.27     150
  4761.3     150 4820.87  151.73 4835.83     152 4845.24     152 4865.71   150.5
 4871.89   150.4 4888.32     149 4911.98  146.84 4978.48   140.1 4990.69  136.03
    5000     134 5019.27   140.1 5071.97     149 5080.85   150.4 5606.09   150.4
 5624.83  150.24 5644.12  150.43 5674.95  150.88 5709.46     152 5762.35     152
#Mann= 3 , 0 , 0
 4676.01      .1       0 4871.89     .04       0 5080.85      .1       0
#XS Ineff= 2 , 0
       0 4845.24     152               0
Permanent Ineff=
       F       F
Bank Sta=4871.89,5080.85
Exp/Cntr=0.3,0.1

Type RM Length L Ch R = 1 ,3510.5  ,315,419.8,511
XS GIS Cut Line= 6
  3005498.29167713909320.9079056 3005515.870054613909252.6130947
 3005521.290647413909238.1862863  3005526.62757913909223.9829026
 3005646.749057913908904.2896444 3006563.395846613908188.0955387
#Sta/Elev= 30
 4773.38     152 4786.36  151.96 4841.35  150.45  4843.9   149.9 4858.97     149
 4909.56     144 4930.46  141.12 4942.07  138.78 4959.64     134 5098.64     134
 5109.59  136.11  5121.7   140.1  5202.4     149    5216   150.2    5236     146
 5646.98     146 5655.37  146.56  5665.2   147.4    5674  147.96 5685.26  147.87
 5698.01     148 5759.97  148.29 5802.91  148.67 5832.95  148.67 5897.88  148.46
 5957.67     148 6138.17     148 6210.04     150    6335     152 6379.26     152
#Mann= 3 , 0 , 0
 4773.38      .1       0  4843.9     .04       0    5216      .1       0
#XS Ineff= 2 , 0
       0                    5216       0   150.2
Permanent Ineff=
       F       F
Bank Sta=4843.9,5216
Exp/Cntr=0.3,0.1

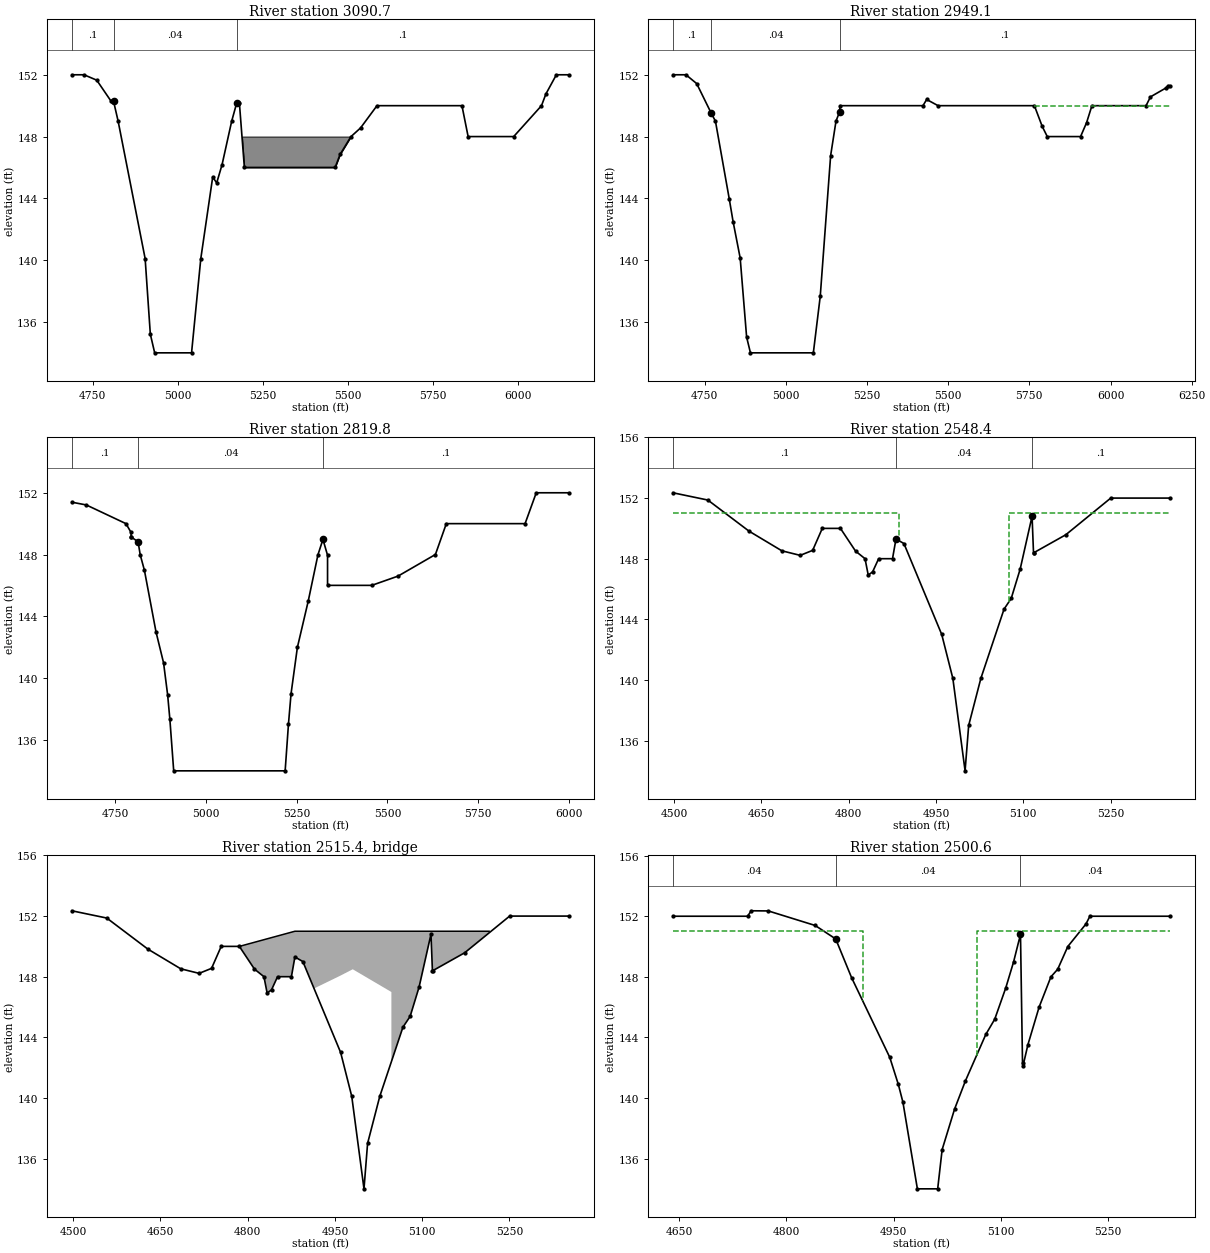
Type RM Length L Ch R = 1 ,3090.7  ,144,141.6,144
XS GIS Cut Line= 6
  3005683.18763313909479.7622467 3005780.503055513909418.5008863
 3005783.683823413909415.9303534 3006014.016696113909229.7745577
 3006073.924712713909181.3570036 3006847.249937713908599.5537053
#Sta/Elev= 30
 4689.03     152 4724.92     152 4762.27  151.65 4804.02   150.3  4811.5   150.3
 4825.06     149 4904.46   140.1 4919.69  135.21 4932.46     134 5040.83     134
 5067.98   140.1 5102.96  145.38 5114.71     145 5130.56  146.19 5158.77     149
 5173.81   150.2 5181.29   150.2    5196     146 5462.64     146 5477.16  146.84
 5508.88  147.99 5537.42  148.56 5585.66     150  5835.3     150 5853.44     148
 5987.34     148 6069.03     150    6082  150.76 6112.66     152 6149.04     152
#Mann= 3 , 0 , 0
 4689.03      .1       0  4811.5     .04       0 5173.81      .1       0
#XS Ineff= 2 , 0
       0                 5181.29       0     150
Permanent Ineff=
       F       F
#Block Obstruct= 1 ,-1
 5188.91    5550     148
Bank Sta=4811.5,5173.81
Exp/Cntr=0.3,0.1

Type RM Length L Ch R = 1 ,2949.1  ,131,129.3,131
BEGIN DESCRIPTION:
center of island XS
END DESCRIPTION:
XS GIS Cut Line= 6
  3005722.25021913909552.6787676 3005838.462257113909530.7362261
 3005925.869562613909469.8665972 3006026.494033313909399.7929185
 3006160.205380113909306.6782753 3007000.895955913908729.7621063
#Sta/Elev= 30
 4652.61     152 4692.81     152 4725.81  151.43 4770.87   149.5 4783.53     149
 4825.87  143.99 4837.94  142.49 4859.69  140.14 4879.55  135.02 4891.31     134
    5085     134 5106.22  137.66 5138.23  146.77 5154.73     149 5165.83   149.6
 5167.28     150 5422.55     150 5433.86   150.4 5469.05     150 5765.57     150
 5789.64  148.66 5805.23     148 5907.77     148 5926.28   148.9 5942.72     150
 6109.36     150 6122.97  150.57 6170.84  151.15 6177.37   151.3 6182.55  151.25
#Mann= 3 , 0 , 0
 4652.61      .1       0 4770.87     .04       0 5165.83      .1       0
#XS Ineff= 2 , 0
       0                 5765.77       0     150
Permanent Ineff=
       F       F
Bank Sta=4770.87,5165.83
Exp/Cntr=0.3,0.1

Type RM Length L Ch R = 1 ,2819.8  ,162,271.4,430
XS GIS Cut Line= 6
  3005690.99995313909594.3453509  3005850.85921413909560.3486997
 3005967.652615613909530.1286158 3006261.018498613909511.0233391
 3006385.654404213909485.6752926 3007047.770862113909422.4703666
#Sta/Elev= 30
 4629.74  151.39 4669.82  151.21 4779.01     150 4793.08  149.43 4793.17  149.14
 4793.36  149.13 4812.41  148.83 4818.38  147.98 4829.91  146.98 4861.94  142.98
 4882.72  140.98 4893.99   138.9 4900.14  137.32 4910.71  133.98 5218.04  133.98
 5227.28  137.04 5234.33  138.98 5251.79  141.98  5281.7  144.98 5308.49  147.98
 5322.28  148.98 5334.98  147.95    5335     146 5456.89     146  5529.4   146.6
 5632.47     148 5662.51     150 5879.71     150 5910.53     152 6000.11     152
#Mann= 3 , 0 , 0
 4629.74      .1       0 4812.41     .04       0 5322.28      .1       0
#XS Ineff= 2 , 0
       0                 5322.28       0  148.98
Permanent Ineff=
       F       F
Bank Sta=4812.41,5322.28
Exp/Cntr=0.3,0.1

Type RM Length L Ch R = 1 ,2548.4  ,59.57,47.8,38.26
XS GIS Cut Line= 6
  3005593.66943913909869.3064151 3005969.573543513909794.5641106
 3006004.038697613909794.8298581 3006201.320127213909796.3498681
 3006203.369991913909796.3698812 3006421.794423813909705.2440792
#Sta/Elev= 30
 4498.03  152.35 4558.07  151.87  4628.7  149.82 4685.22  148.52 4716.73  148.22
 4738.11  148.55 4754.67     150 4785.88     150 4811.82   148.5 4828.11     148
 4833.59  146.92 4841.11  147.13  4851.5     148 4875.32     148 4881.29   149.3
 4894.95     149 4959.88     143 4978.99   140.1    5000     134 5006.19     137
  5027.1   140.1 5066.93  144.67 5079.29  145.38  5094.7  147.32 5115.09   150.8
 5117.58  148.39 5117.88  148.39 5173.07  149.58 5250.28     152 5351.77     152
#Mann= 3 , 0 , 0
 4498.03      .1       0 4881.29     .04       0 5115.09      .1       0
#XS Ineff= 2 , 0
       0 4886.19     151 5075.09       0     151
Permanent Ineff=
       F       F
Bank Sta=4881.29,5115.09
Exp/Cntr=0.5,0.3

Type RM Length L Ch R = 3 ,2515.4  ,,,
BEGIN DESCRIPTION:
Pedestrian Bridge - Added to model August 2010.  Low Pedestrian Bridge #2
END DESCRIPTION:
Bridge Culvert--1,0,-1,-1, 0
Deck Dist Width WeirC Skew NumUp NumDn MinLoCord MaxHiCord MaxSubmerge Is_Ogee
28,10,2.6,0, 7, 7, , , 0.95, 0, 0,0,,
 4785.88 4881.29 4914.19 4980.69 5047.09 5115.09    5215
     150     151     151     151     151     151     151
                  147.17  148.49  146.99
    4700 4868.83 4919.66 4986.16 5052.56 5127.22    5215
     150     151     151     151     151     151     151
                  147.17  148.49  146.99
BR Coef=-1 , 0 , 0 ,, 0 ,,,0.8,0,,0,
WSPro=,,,, 1 ,,,, 0 ,,,, 0 ,,,,-1 ,-1 ,-1 , 0 , 0 , 0 , 0 , 0
BC Design=,, 0 ,, 0 ,,,,,,
BC HTab HWMax=151

Type RM Length L Ch R = 1 ,2500.6  ,214.43,181.6,137.74
XS GIS Cut Line= 6
  3005747.31512913909884.9313839 3005972.911135213909854.5590693
 3005986.262486513909853.0016577 3006130.249731313909836.2083842
 3006229.561540613909824.6250741 3006424.3984212  13909749.51466
#Sta/Elev= 30
  4641.2     152 4745.55     152 4750.72  152.36 4774.59  152.35 4840.09  151.39
 4868.83   150.5 4891.08  147.94 4944.44  142.68 4956.44  140.89 4962.83  139.72
 4983.04     134 5011.43     134 5017.66  136.59    5035  139.26 5050.23  141.13
 5078.77   144.2  5091.2   145.2 5106.71  147.28 5117.54  148.98 5127.22   150.8
 5130.04  142.32 5130.64  142.09 5137.55  143.51 5153.25     146 5169.79     148
 5179.25   148.5 5193.38     150  5218.8  151.49 5224.23     152 5336.03     152
#Mann= 3 , 0 , 0
  4641.2     .04       0 4868.83     .04       0 5127.22     .04       0
#XS Ineff= 2 , 0
       0 4906.46     151 5065.76       0     151
Permanent Ineff=
       F       F
Bank Sta=4868.83,5127.22
Exp/Cntr=0.5,0.3

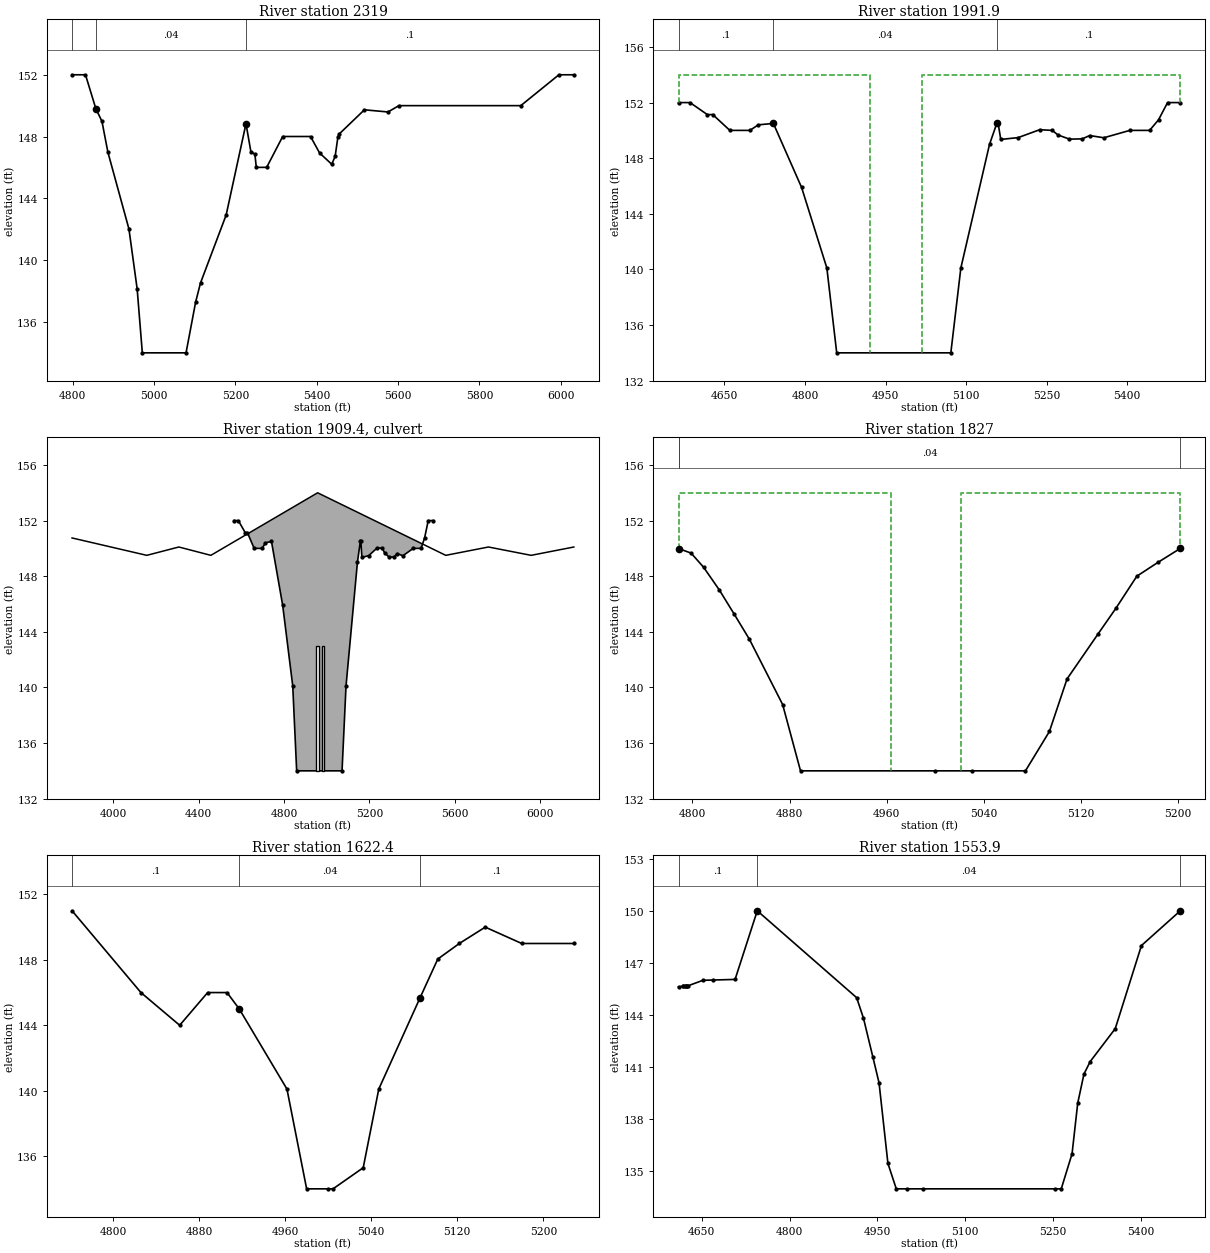
Type RM Length L Ch R = 1 ,2319    ,181,327.1,285
XS GIS Cut Line= 6
  3005929.60675913910095.8689542 3005982.6614438 13910071.399843
 3006253.438461313909957.3885881 3006322.005909513909928.5179109
 3006343.196483913909919.5956846 3007062.419454913909606.2856157
#Sta/Elev= 30
 4798.18     152 4831.19     152 4856.58  149.81  4871.7  148.98 4886.31  146.98
 4938.03  142.01 4958.29  138.12 4970.96  133.98 5078.48  133.98 5102.16  137.28
 5114.07  138.51 5177.11  142.91 5225.93  148.83 5238.07     147 5247.77  146.86
  5251.3     146 5276.76     146 5316.21     148 5384.63     148 5407.02  146.93
 5436.88   146.2 5445.25  146.72 5452.14     148 5455.86  148.18 5517.17  149.73
 5575.22  149.59 5602.02     150 5901.78     150 5995.51     152  6032.3     152
#Mann= 3 , 0 , 0
 4798.18      .1       0 4856.58     .04       0 5225.93      .1       0
#XS Ineff= 2 , 0
       0                 5225.93       0  148.83
Permanent Ineff=
       F       F
Bank Sta=4856.58,5225.93
Exp/Cntr=0.5,0.3

Type RM Length L Ch R = 1 ,1991.9  ,165,164.9,165
BEGIN DESCRIPTION:
Upstream XS Rouse Parkway Bridge
END DESCRIPTION:
XS GIS Cut Line= 6
  3005944.79767413910228.8939506 3006119.6408286 13910203.860208
 3006130.198222213910198.6709139 3006230.843362113910169.6624417
 3006530.105230813910128.4607525 3006845.405453213910003.1995201
#Sta/Elev= 30
 4564.49     152 4585.88     152 4618.36  151.13 4628.14  151.14 4660.06     150
 4697.41     150 4713.04   150.4 4741.11   150.5 4793.63   145.9 4840.72   140.1
 4859.06     134  5071.6     134 5090.23   140.1 5143.67     149 5157.17   150.5
  5159.7   150.5 5164.57  149.35  5196.8  149.48 5237.16  150.05  5260.4     150
 5271.24  149.67 5292.55  149.37 5316.42  149.39 5330.16  149.63 5356.49  149.47
 5404.95     150 5441.78     150 5458.36  150.76 5475.24     152 5498.98     152
#Mann= 3 , 0 , 0
 4564.49      .1       0 4741.11     .04       0 5157.17      .1       0
#XS Ineff= 2 , 0
       0 4921.75     154 5017.75       0     154
Permanent Ineff=
       F       F
Bank Sta=4741.11,5157.17
Exp/Cntr=0.5,0.3

Type RM Length L Ch R = 2 ,1909.4  ,,,
BEGIN DESCRIPTION:
North Bridgelands Parkway
END DESCRIPTION:
Bridge Culvert--1,0,-1,-1, 0
Deck Dist Width WeirC Skew NumUp NumDn MinLoCord MaxHiCord MaxSubmerge Is_Ogee
29.3,120,2.6,0, 9, 9, 149.5, , 0.95, 0, 0,0,,
 3807.25 4157.25 4307.25 4457.25 4957.25 5557.25 5757.25 5957.25 6157.25
  150.75   149.5   150.1   149.5     154   149.5   150.1   149.5   150.1
  132.09  132.09  132.09  132.09  132.09  132.09  132.09  132.09  132.09
    3830    4180    4330    4480    4980    5580    5780    5980    6180
   150.1   149.5   150.1   149.5     154   149.5   150.1   149.5   150.1
  132.09  132.09  132.09  132.09  132.09  132.09  132.09  132.09  132.09
BR Coef=-1 , 0 , 0 ,, 0 ,,,0.8,-1,,0,
WSPro=,,,, 1 ,,,, 0 ,,,, 0 ,,,,-1 ,-1 ,-1 , 0 , 0 , 0 , 0 , 0
Multiple Barrel Culv=2,9,12,120,0.013,0.5,1,8,1,134,134, 2,Culvert #1  , 0 ,29.5
 4957.25    4980 4982.25    5005
Culvert Bottom n=0.013
BC Design=,, 0 ,, 0 ,,,,,,
BC HTab Sub Flow Curves= 60
BC HTab Sub Flow Pts= 40
BC HTab HWMax=153
BC HTab TWMax=152.5
BC HTab MaxFlow=2500

Type RM Length L Ch R = 1 ,1827    ,383,204.6,23
BEGIN DESCRIPTION:
Downstream XS Rouse Parkway Bridge
END DESCRIPTION:
XS GIS Cut Line= 2
  3006159.23162813910348.1348539 3006568.588421713910291.7648879
#Sta/Elev= 18
 4788.56  149.99 4798.92  149.66 4809.23  148.64 4822.07  147.02  4834.2   145.3
 4846.88  143.47 4874.29  138.77 4889.01     134    5000     134    5030     134
 5074.25     134 5093.97  136.83 5108.49  140.61 5134.22  143.87 5148.64  145.68
 5165.96     148 5183.48     149 5201.78     150
#Mann= 3 , 0 , 0
 4788.56      .1       0 4788.56     .04       0 5201.78      .1       0
#XS Ineff= 2 , 0
       0  4963.7     154  5021.3       0     154
Permanent Ineff=
       F       F
Bank Sta=4788.56,5201.78
Exp/Cntr=0.5,0.3

Type RM Length L Ch R = 1 ,1622.4  ,26,68.5,360
XS GIS Cut Line= 5
  3006288.09052713910612.1454956 3006369.315698213910567.6549151
  3006461.11020713910503.3095533 3006585.818135313910414.2965317
 3006606.096187213910307.8255333
#Sta/Elev= 18
 4762.02     151 4826.02     146 4862.02     144 4888.02     146 4906.02     146
 4917.37     145 4961.71   140.1 4980.01     134    5000     134 5004.54     134
 5032.58  135.29 5047.04   140.1 5085.39  145.68 5101.89  148.05 5121.89     149
 5145.98     150 5179.89     149 5228.33     149
#Mann= 3 , 0 , 0
 4762.02      .1       0 4917.37     .04       0 5085.39      .1       0
Bank Sta=4917.37,5085.39
Exp/Cntr=0.3,0.1

Type RM Length L Ch R = 1 ,1553.9  ,188,279.8,670
XS GIS Cut Line= 4
  3006220.31889613910686.0387439 3006761.923979913910409.7755871
 3006892.520003413910343.1608032 3006926.235076113910246.7144222
#Sta/Elev= 29
 4610.35  145.62  4618.3  145.66 4618.72  145.65 4620.72  145.67 4623.02  145.69
 4623.38  145.68 4624.86  145.69 4626.33  145.68 4652.13     146 4668.66146.0151
 4706.88  146.05 4744.79     150 4914.47     145  4926.1  143.82 4942.05   141.6
 4952.71   140.1 4967.87  135.46 4982.14     134    5000     134 5027.81     134
  5253.3     134 5263.81     134 5282.27  136.02 5291.93  138.93 5302.54   140.6
 5313.15  141.32 5356.03  143.22 5400.74     148 5467.12     150
#Mann= 3 , 0 , 0
 4610.35      .1       0 4744.79     .04       0 5467.12      .1       0
Bank Sta=4744.79,5467.12
Exp/Cntr=0.5,0.3

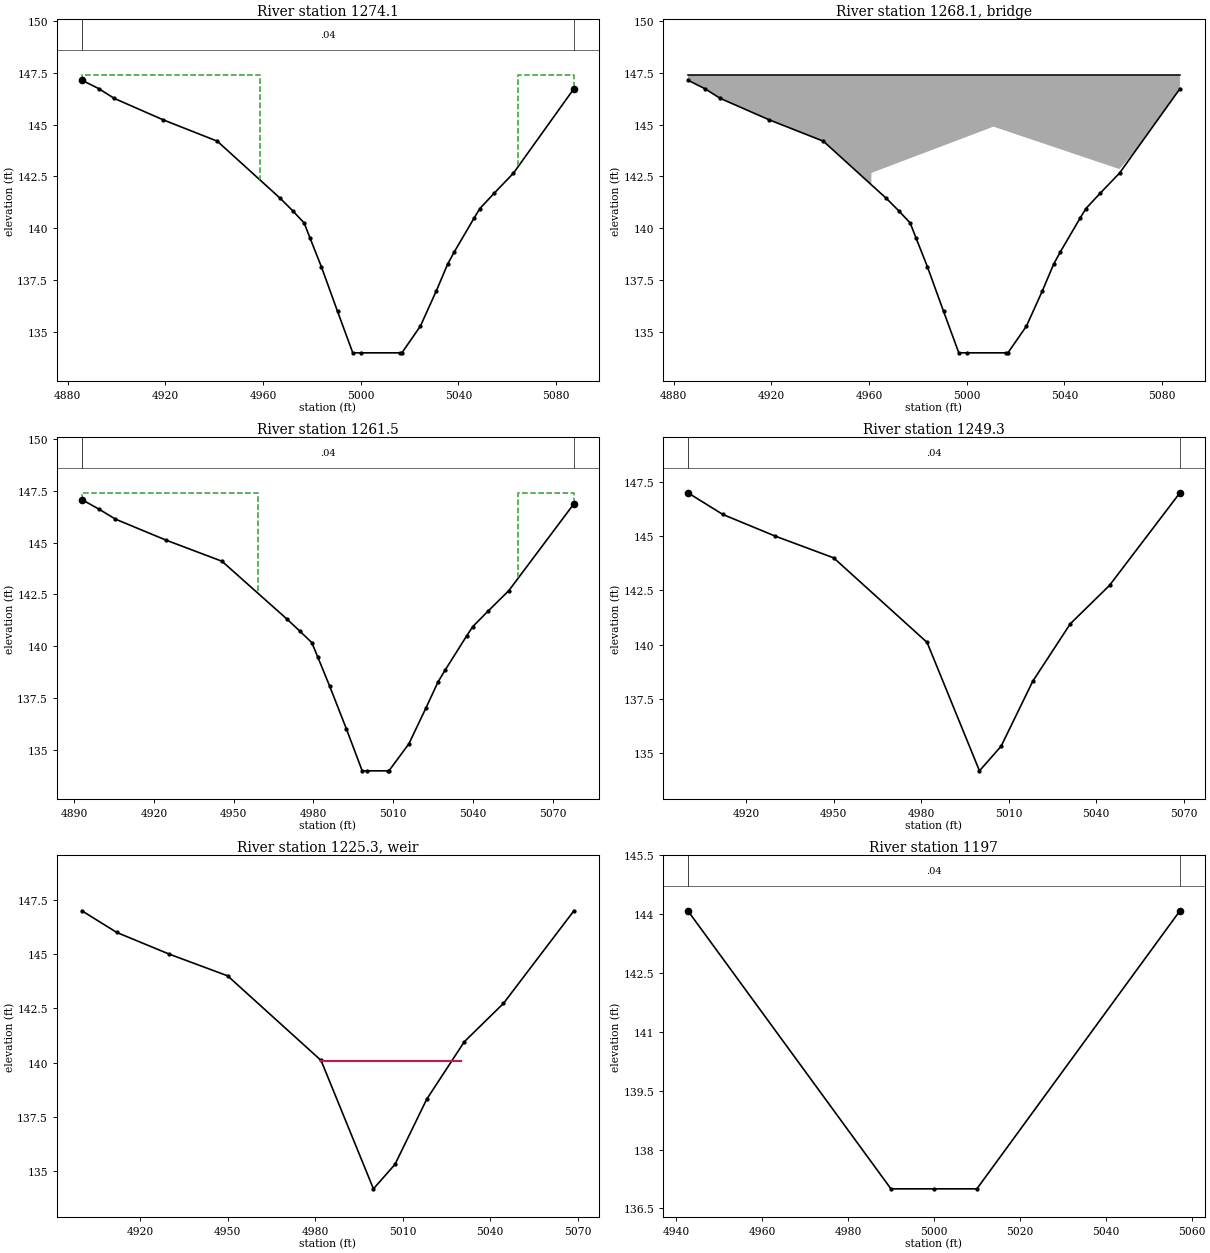
Type RM Length L Ch R = 1 ,1274.1  ,6.71,12.6,23.92
XS GIS Cut Line= 4
  3006413.64861513910716.5833014 3006433.376198413910726.9274132
 3006572.377275413910799.8113449  3006592.10485813910810.1554566
#Sta/Elev= 24
 4885.79  147.14 4892.74  146.73 4899.11  146.26 4919.07  145.23 4941.26   144.2
 4967.09  141.44 4972.18  140.84 4976.81  140.26 4979.17  139.55 4983.84  138.16
 4990.49     136 4996.74     134    5000     134  5016.1     134 5016.85     134
 5024.44  135.29 5030.96  136.99 5035.57  138.27 5038.33  138.87 5046.44   140.5
 5048.76  140.95 5054.54  141.68 5062.54  142.66 5087.29  146.73
#Mann= 3 , 0 , 0
 4885.79     .04       0 4885.79     .04       0 5087.29     .04       0
#XS Ineff= 2 , 0
       0 4958.94   147.4 5064.54       0   147.4
Permanent Ineff=
       F       F
Bank Sta=4885.79,5087.29
Exp/Cntr=0.5,0.3

Type RM Length L Ch R = 3 ,1268.1  ,,,
BEGIN DESCRIPTION:
Pedestrian Bridge #1
END DESCRIPTION:
Bridge Culvert--1,0,-1,-1, 0
Deck Dist Width WeirC Skew NumUp NumDn MinLoCord MaxHiCord MaxSubmerge Is_Ogee
2,8,2.6,0, 7, 7, , , 0.95, 0, 0,0,,
 4885.79    4900 4960.94 5010.94 5069.94    5070 5087.29
   147.4   147.4   147.4   147.4   147.4   147.4   147.4
                  142.67   144.9  142.56
  4892.9    4900 4960.94 5010.94 5069.94    5070 5078.02
   147.4   147.4   147.4   147.4   147.4   147.4   147.4
                  142.67   144.9  142.56
BR Coef=-1 , 0 , 0 ,, 0 ,,,0.8,0,,0,
WSPro=,,,, 1 ,,,, 0 ,,,, 0 ,,,,-1 ,-1 ,-1 , 0 , 0 , 0 , 0 , 0
BC Design=,, 0 ,, 0 ,,,,,,
BC HTab HWMax=150

Type RM Length L Ch R = 1 ,1261.5  ,6.71,12.2,23.93
XS GIS Cut Line= 4
  3006426.02110413910734.1634969 3006444.596434113910744.7456453
 3006568.2947537  13910815.21625 3006586.870083813910825.7983984
#Sta/Elev= 24
  4892.9  147.07  4899.5   146.6 4905.55  146.13 4924.53  145.12 4945.63   144.1
 4970.18   141.3 4975.02  140.72 4979.42  140.18 4981.67  139.48 4986.11  138.09
 4992.43  136.02 4998.37     134    5000     134 5008.05     134 5008.43     134
 5015.92   135.3 5022.36  137.03 5026.92  138.29 5029.65  138.87 5037.66   140.5
 5039.96  140.95 5045.66  141.69 5053.57  142.69 5078.02  146.87
#Mann= 3 , 0 , 0
  4892.9     .04       0  4892.9     .04       0 5078.02     .04       0
#XS Ineff= 2 , 0
       0 4959.21   147.4 5056.96       0   147.4
Permanent Ineff=
       F       F
Bank Sta=4892.9,5078.02
Exp/Cntr=0.5,0.3

Type RM Length L Ch R = 1 ,1249.3  ,51,52.3,51
BEGIN DESCRIPTION:
u/s of control structure
END DESCRIPTION:
XS GIS Cut Line= 4
  3006427.723545 13910746.933925 3006443.920035813910756.7101522
 3006555.999864113910824.3599513  3006572.19635413910834.1358504
#Sta/Elev= 11
    4900     147    4912     146    4930     145    4950     144 4982.04   140.1
    5000  134.18  5007.4  135.31 5018.27  138.31 5031.15  140.96  5044.6  142.73
 5068.75     147
#Mann= 3 , 0 , 0
    4900      .1       0    4900     .04       0 5068.75      .1       0
Bank Sta=4900,5068.75
Exp/Cntr=0.5,0.3

Type RM Length L Ch R = 5 ,1225.3  ,,,
BEGIN DESCRIPTION:
lake amentity control elev. 140.1
END DESCRIPTION:
IW Pilot Flow=5
#Inline Weir SE= 5
 4982.04  140.09    5000  140.09    5010  140.09    5015  140.09    5030  140.09
IW Dist,WD,Coef,Skew,MaxSub,Min_El,Is_Ogee,SpillHt,DesHd
6,5,2.6,0,0.95,, 0 ,,,0,0,

Type RM Length L Ch R = 1 ,1197    ,228,317.1,328
BEGIN DESCRIPTION:
d/s of control structure
END DESCRIPTION:
XS GIS Cut Line= 2
  3006426.34100213910811.0358309 3006528.748934413910862.3841535
#Sta/Elev= 5
 4942.72  144.09    4990     137    5000     137    5010     137 5057.28  144.09
#Mann= 3 , 0 , 0
 4942.72      .1       0 4942.72     .04       0 5057.28      .1       0
Bank Sta=4942.72,5057.28
Exp/Cntr=0.5,0.3

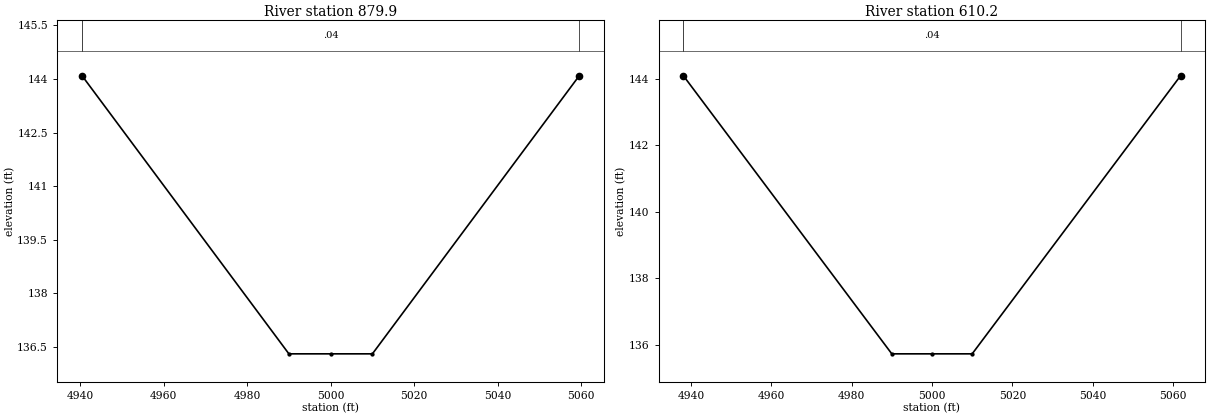
Type RM Length L Ch R = 1 ,879.9   ,274,269.7,274
XS GIS Cut Line= 2
  3006352.29587513911028.1640056 3006392.207868913911140.3137157
#Sta/Elev= 5
 4940.48  144.09    4990  136.31    5000  136.31    5010  136.31 5059.52  144.09
#Mann= 3 , 0 , 0
 4940.48      .1       0 4940.48     .04       0 5059.52      .1       0
Bank Sta=4940.48,5059.52
Exp/Cntr=0.3,0.1

Type RM Length L Ch R = 1 ,610.2   ,204,150.7,200
XS GIS Cut Line= 2
  3006108.58310813911142.0814287 3006154.749682413911256.8220129
#Sta/Elev= 5
 4938.16  144.09    4990  135.73    5000  135.73    5010  135.73 5061.84  144.09
#Mann= 3 , 0 , 0
 4938.16      .1       0 4938.16     .04       0 5061.84      .1       0
Bank Sta=4938.16,5061.84
Exp/Cntr=0.3,0.1