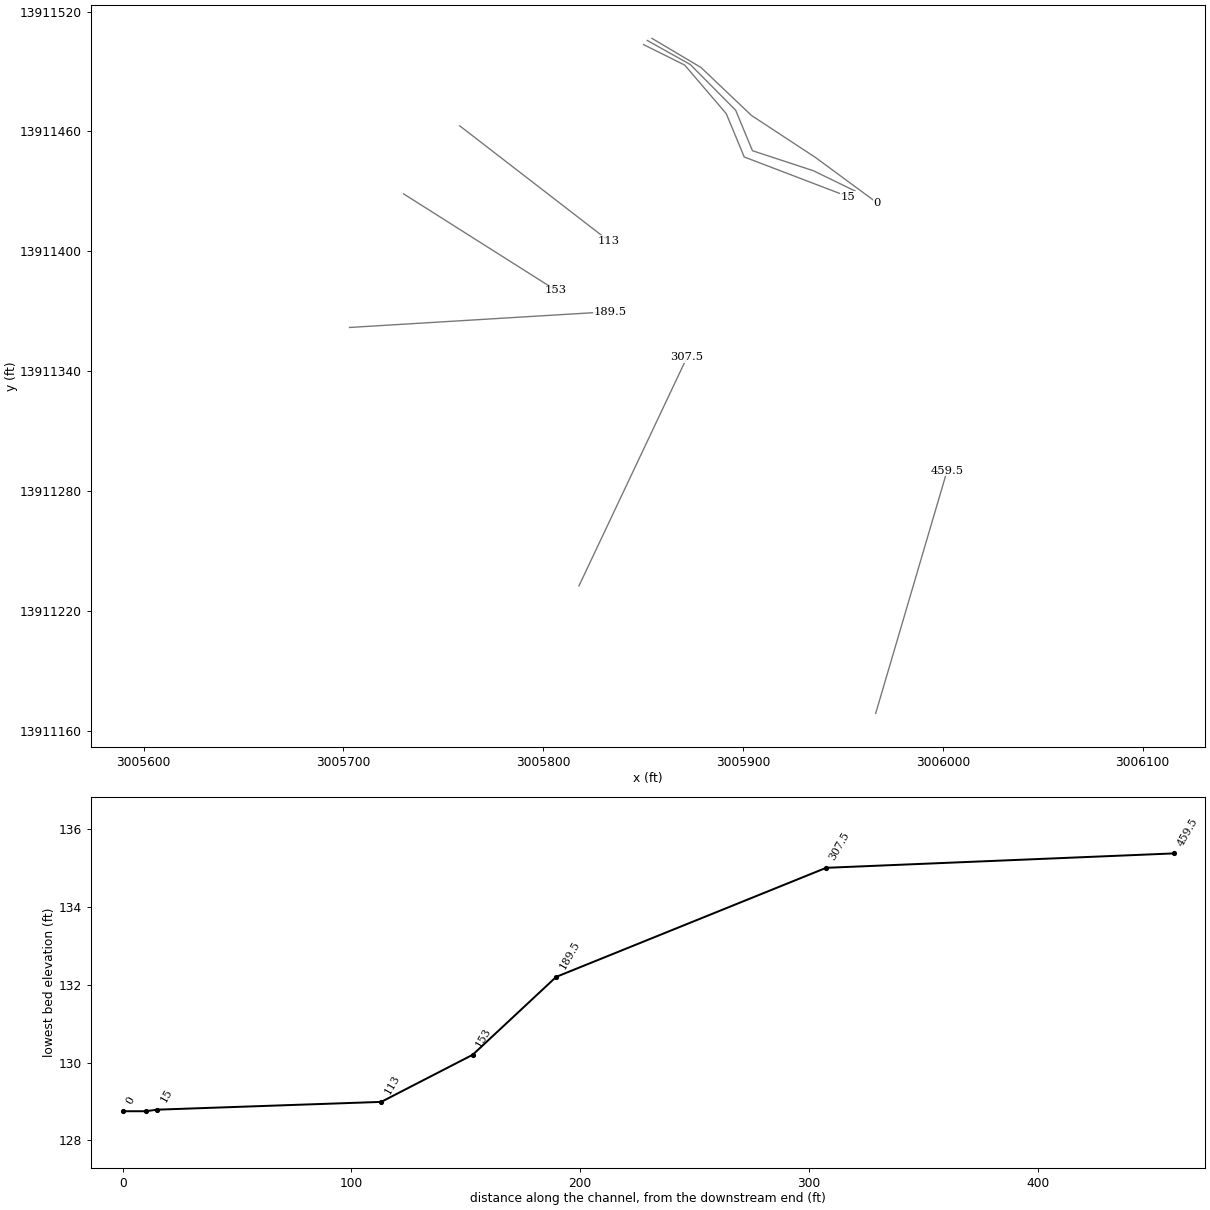
HEC-RAS study K150-00-00.prj: K150-00-00

--- K150-00-00.g01 (geometry) --- (continued)

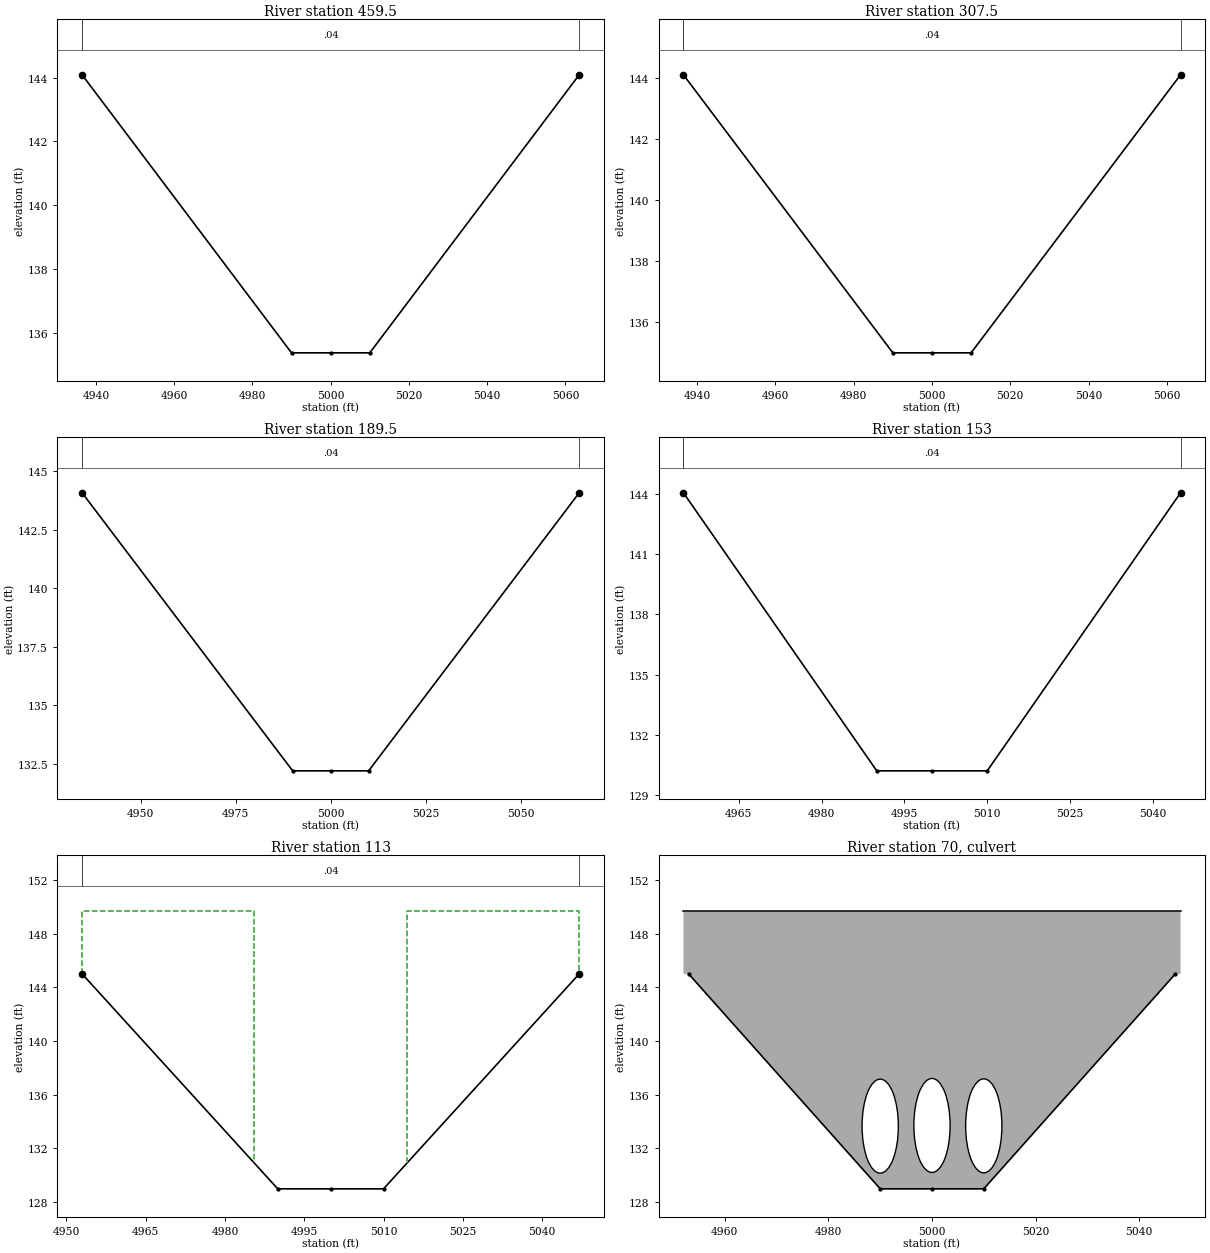
Type RM Length L Ch R = 1 ,459.5   ,152,152,152
XS GIS Cut Line= 2
  3005966.41016413911168.7700236 3006002.1299089 13911290.110004
#Sta/Elev= 5
 4936.48  144.09    4990  135.37    5000  135.37    5010  135.37 5063.52  144.09
#Mann= 3 , 0 , 0
 4936.48      .1       0 4936.48     .04       0 5063.52      .1       0
Bank Sta=4936.48,5063.52
Exp/Cntr=0.3,0.1

Type RM Length L Ch R = 1 ,307.5   ,64,118,64
XS GIS Cut Line= 2
  3005817.91013313911232.5599223 3005871.959893613911346.9199298
#Sta/Elev= 5
 4936.48  144.09    4990     135    5000     135    5010     135 5063.52  144.09
#Mann= 3 , 0 , 0
 4936.48      .1       0 4936.48     .04       0 5063.52      .1       0
Bank Sta=4936.48,5063.52
Exp/Cntr=0.3,0.1

Type RM Length L Ch R = 1 ,189.5   ,36,36.5,36
XS GIS Cut Line= 4
  3005703.090152 13911361.896934 3005725.389976813911363.2499496
  3005811.43015913911368.4700835 3005833.729983213911369.8227711
#Sta/Elev= 5
 4934.56  144.09    4990   132.2    5000   132.2    5010   132.2 5065.44  144.09
#Mann= 3 , 0 , 0
 4934.56      .1       0 4934.56     .04       0 5065.44      .1       0
Bank Sta=4934.56,5065.44
Exp/Cntr=0.3,0.1

Type RM Length L Ch R = 1 ,153     ,40,40,40
XS GIS Cut Line= 4
  3005730.16555713911428.7455535 3005731.769885313911427.7301356
 3005804.609962713911381.6301622 3005806.214290213911380.6144162
#Sta/Elev= 5
    4955  144.06    4990   130.2    5000   130.2    5010   130.2    5045  144.06
#Mann= 3 , 0 , 0
    4955      .1       0    4955     .04       0    5045      .1       0
Bank Sta=4955,5045
Exp/Cntr=0.5,0.3

Type RM Length L Ch R = 1 ,113     ,110,98,98
BEGIN DESCRIPTION:
Convergence w/ K100-00-00
END DESCRIPTION:
XS GIS Cut Line= 4
  3005758.26655113911462.7796062 3005761.349878613911460.4000178
 3005829.600070213911407.7298475 3005832.683397413911405.3502591
#Sta/Elev= 5
    4953     145    4990  128.99    5000  128.99    5010  128.99    5047     145
#Mann= 3 , 0 , 0
    4953      .1       0    4953     .04       0    5047      .1       0
#XS Ineff= 2 , 0
       0  4985.5   149.7  5014.5       0   149.7
Permanent Ineff=
       F       F
Bank Sta=4953,5047
Exp/Cntr=0.5,0.3

Type RM Length L Ch R = 2 ,70      ,,,
BEGIN DESCRIPTION:
Outfall to Cypress Creek
END DESCRIPTION:
Bridge Culvert--1,0,-1,-1, 0
Deck Dist Width WeirC Skew NumUp NumDn MinLoCord MaxHiCord MaxSubmerge Is_Ogee
6,80,2.6,0, 4, 4, , , 0.95, 0, 0,0,,
    4952    4989    5011    5048
   149.7   149.7   149.7   149.7
  128.99  128.99  128.99  128.99
    4932    4989    5011    5068
   149.7   149.7   149.7   149.7
  127.09  127.09  127.09  127.09
BR Coef=-1 , 0 , 0 ,, 0 ,,,0.8,-1,,0,
WSPro=,,,, 1 ,,,, 0 ,,,, 0 ,,,,-1 ,-1 ,-1 , 0 , 0 , 0 , 0 , 0
Culvert=1,7,,97,0.024,0.5,1,2,1,130.16,4990,129.63,4990,Culvert #1  , 0 ,1
Culvert Bottom n=0.024
Culvert=1,7,,97,0.024,0.5,1,1,1,130.21,5000,129.49,5000,Culvert #2  , 0 ,1
Culvert Bottom n=0.024
Culvert=1,7,,97,0.024,0.5,1,1,1,130.18,5010,129.44,5010,Culvert #3  , 0 ,1
Culvert Bottom n=0.024
BC Design=,, 0 ,, 0 ,,,,,,
BC HTab Sub Flow Curves= 50
BC HTab Sub Flow Pts= 40
BC HTab HWMax=153
BC HTab TWMax=152.5
BC HTab MaxFlow=2500

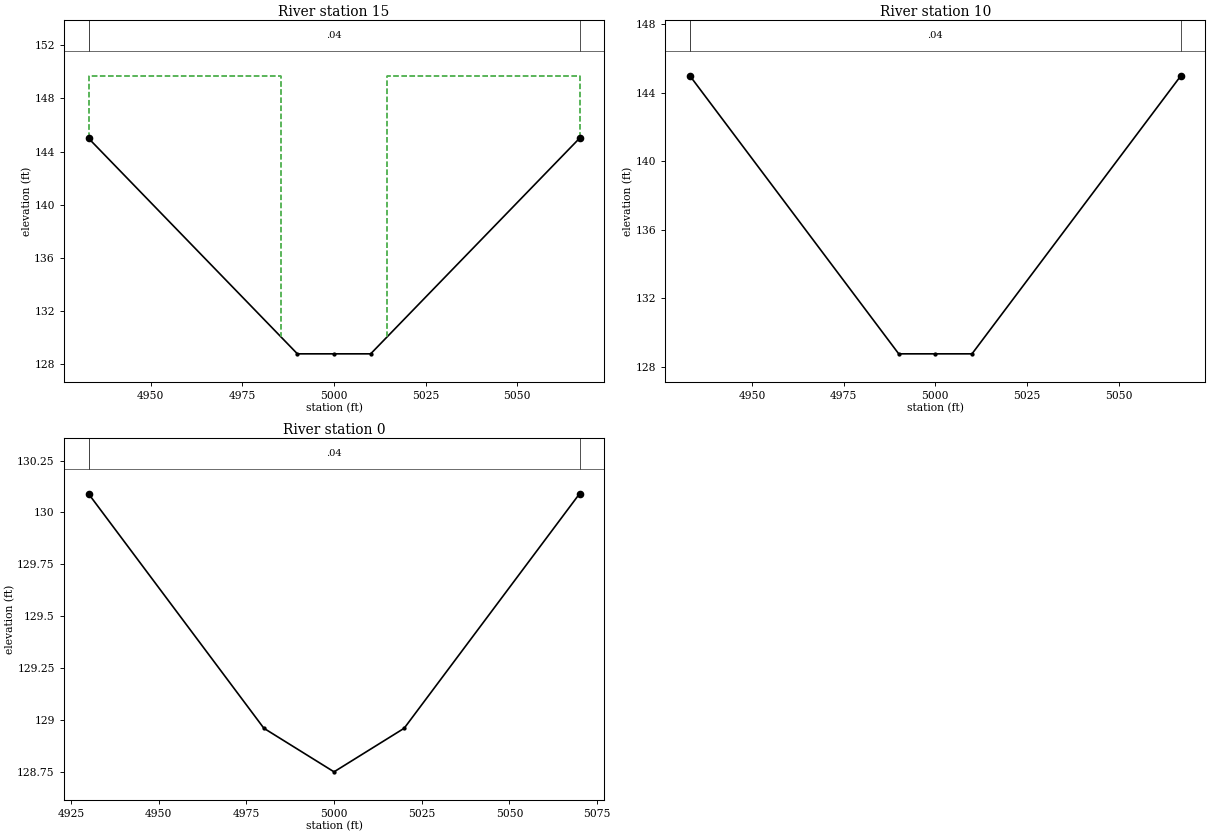
Type RM Length L Ch R = 1 ,15      ,5,5,5
BEGIN DESCRIPTION:
Convergence w/ K100-00-00
END DESCRIPTION:
XS GIS Cut Line= 6
     3005850.215   13911503.4749  3005870.82767813911493.2240991
 3005891.635051113911468.8986884 3005900.620597413911447.2268158
 3005929.332154213911436.2586619    3005952.5898   13911427.3743
#Sta/Elev= 5
    4933     145    4990  128.79    5000  128.79    5010  128.79    5067     145
#Mann= 3 , 0 , 0
    4933      .1       0    4933     .04       0    5067      .1       0
#XS Ineff= 2 , 0
       0  4985.5   149.7  5014.5       0   149.7
Permanent Ineff=
       F       F
Bank Sta=4933,5067
Exp/Cntr=0.5,0.3

Type RM Length L Ch R = 1 ,10      ,10,10,10
BEGIN DESCRIPTION:
Convergence w/ K100-00-00
END DESCRIPTION:
XS GIS Cut Line= 6
    3005852.0944   13911505.5293 3005873.641976913911493.4865658
 3005896.330907913911470.6303123 3005904.735746713911450.3570589
 3005935.204845913911440.3524857    3005956.1578   13911430.1686
#Sta/Elev= 5
    4933     145    4990  128.75    5000  128.75    5010  128.75    5067     145
#Mann= 3 , 0 , 0
    4933      .1       0    4933     .04       0    5067      .1       0
Bank Sta=4933,5067
Exp/Cntr=0.3,0.1

Type RM Length L Ch R = 1 ,0       ,85,0,0
BEGIN DESCRIPTION:
Convergence w/ K100-00-00
END DESCRIPTION:
XS GIS Cut Line= 6
  3005854.41498113911506.5980881 3005878.999905813911492.0000202
 3005904.249855313911468.0000682 3005909.732127813911464.4024704
 3005936.250119313911447.0001102 3005967.089952713911424.2960874
#Sta/Elev= 5
    4930  130.09    4980  128.96    5000  128.75    5020  128.96    5070  130.09
#Mann= 3 , 0 , 0
    4930      .1       0    4930     .04       0    5070      .1       0
Bank Sta=4930,5070
Exp/Cntr=0.3,0.1

Chan Stop Cuts=-1
Use User Specified Reach Order=0
User Specified Reach Order=K150-00-00      ,REVISED ALIGN