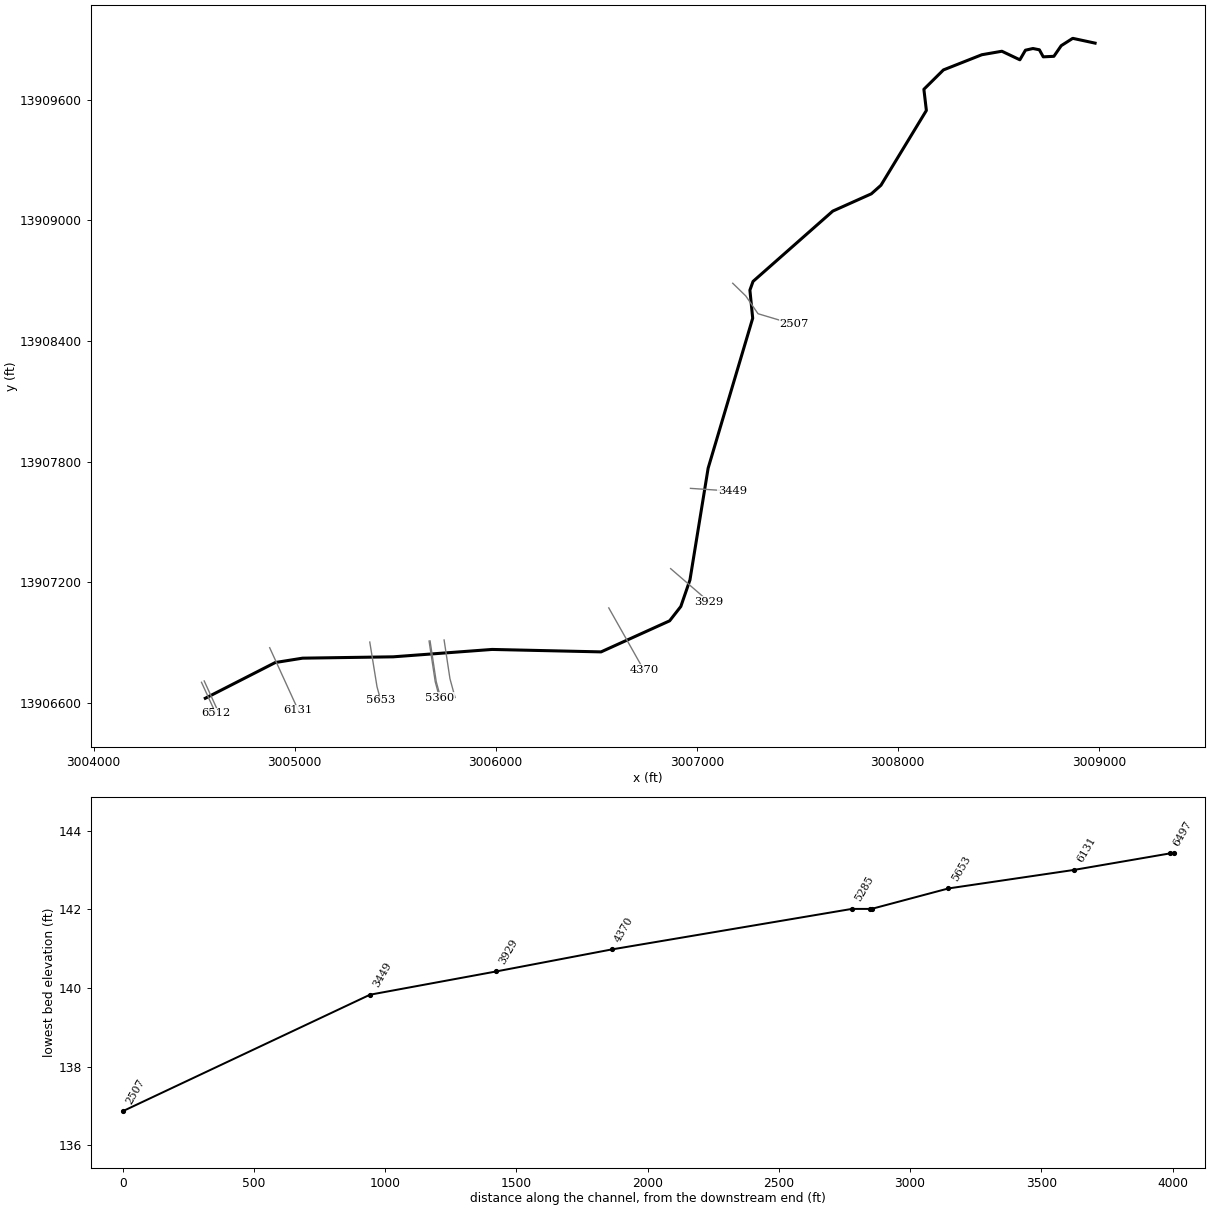
--- K150-01-00.prj (project) ---

Proj Title=K150-01-00
Current Plan=p01
Default Exp/Contr=.3,.1
English Units
Geom File=g01
Flow File=f02
Flow File=f01
Plan File=p02
Plan File=p01
Y Axis Title=Elevation
X Axis Title(PF)=Main Channel Distance
X Axis Title(XS)=Station
BEGIN DESCRIPTION:
HCFCD MODEL SUMMARY METADATA
The purpose of this summary is to document the high points of hydrologic and hydraulic models filed within the HCFCD Model and Map Management (M3) system.  The document includes references to the project that prompted the creation or update of the model.
DESCRIPTION OF PROJECT:
The following model was the hydraulic model which represented the effective condition of Harris County's watersheds.
PURPOSE OF PROJECT:
Development of effective models to support the National Flood Insurance Program.
HCFCD Watershed Unit ID: K
M3 Study Identifier: 2007_Effective_K
Engineer: HCFCD
Project Name: EffectiveFEMA Study for watershed Cypress Creek (K)
Study Completion Date: 6/18/2007
FEMA Case Number: [No Data]
FEMA Approval Date: [No Date in Database]
Vertical Datum: NAVD 1988
Datum Note: 2001 ADJ
HYDRAULICS
HCFCD Unit No.:  K150-00-00 & K150-00-01
Hydraulic Program Name: HEC-RAS
Hydraulic Program Version: 3.0.1
Steady Hydraulic Model: Yes
Unsteady Hydraulic Model: No
Update 1: The effective FEMA hydraulic model for unit number K150-01-00 has been updated by FEMA LOMR 07-06-01885P with an effective date of 11/28/2008.
Update 2: The effective FEMA hydraulic model for unit number K150-01-00 has been updated by FEMA LOMR 16-06-0557P with an effective date of 11/04/2016.
Update 3: The effective FEMA hydraulic model for unit number K150-01-00 has been updated by FEMA LOMR 17-06-0430X with an effective date of 08/14/2017.
END DESCRIPTION:
DSS Export Rating Curves= 0
DSS Export Rating Curve Sorted= 0
DSS Export Volume Flow Curves= 0
DXF Filename=k15001.dxf
DXF OffsetX= 0
DXF OffsetY= 0
DXF ScaleX= 1
DXF ScaleY= 1

--- K150-01-00.p01 (plan) ---

Plan Title=FEMA Effective Multi-Profile 2017
Version=Version 3.0.1  May 2012
Short Identifier=Eff+LOMR MP
Simulation Date=01JAN1983,1200,03JAN1983,2200
Geom File=g01
Flow File=f01
Subcritical Flow
K Sum by GR= 0
Std Step Tol= 0.01
Critical Tol= 0.01
Num of Std Step Trials= 20
Max Error Tol= 0.3
Flow Tol Ratio= 0.001
Split Flow NTrial= 30
Split Flow Tol= 0.02
Split Flow Ratio= 0.02
Log Output Level= 0
Friction Slope Method= 1
Unsteady Friction Slope Method= 2
Secant Critical Depth
Global Vel Dist= 0 , 0 , 0
Global Log Level= 0
CheckData=True
Encroach Param=-1 ,0,0, 2
Encroach River=K150-00-00
Encroach Reach=DS_DIVERSION
Encroach Node=6512
       1    4980 5026.64
Encroach Node=6497
       1    4980 5026.62
Encroach Node=6131
       1    22.2   125.6
Encroach Node=5653
       1    4960 5072.62
Encroach Node=5360
       1 4967.08 5073.67
Encroach Node=5355
       1 4967.08 5073.67
Encroach Node=5285
       1 4967.08 5073.67
Encroach Node=4370
       1  4966.9  5036.9
Encroach Node=3929
       1    4969 5051.13
Encroach Node=3449
       1  4971.2 5029.35
Encroach Node=2507
       1 4967.75 5056.43
Encroach Node=2036
       1    4950 5032.85
Encroach Node=1990
       1    4959 5032.85
Encroach Node=1804
       1 4276.81 4324.01
Encroach Node=1803
       1 4276.81 4324.01
Encroach Node=1759
       1 4279.12 4324.01
Encroach Node=1650
       1  3704.1 3723.41
Encroach Node=1593
       1  3694.1 3733.41
Encroach Node=1389
       1 4980.33 5021.41
Encroach Node=871
       1 4986.12 5030.63
Encroach Node=749
       1  4977.4  5037.4
Encroach Node=714
       1  4977.4  5037.4
Encroach Node=620
       1  4977.4 5038.35
Encroach Node=415
       1  4977.4  5037.4
Encroach Node=391
       1  4977.4  5037.4
Encroach Node=356
       1  4977.4  5037.4
BEGIN DESCRIPTION:
FEMA Effective Multi-Profile June 2007 + LOMR 07-06-1885P +16-06-0557P + 17-06-0430X
END DESCRIPTION:
Computation Interval=30SEC
Output Interval=15MIN
Run HTab= 1
Run UNet= 1
Run PostProcess= 1
UNET Theta= 1
UNET ZTol= 0.005
UNET ZSATol= 0.05
UNET MxIter= 40
UNET MaxInSteps= 200
UNET DtIC= 0
UNET DtMin= 0
UNET MaxCRTS= 40
UNET WFStab= 2
UNET SFStab= 1
UNET WFX= 1
UNET SFX= 1
UNET Convert EG Bridges= 0
UNET Use Existing IB Tables=-1
Instantaneous Interval=4HOUR
DSS File=dss
Write IC File= 0
IC Time=0
Write Velocity= 0
Write Detailed= 0
Stage Flow Hydrograph=K100-00-00      ,US K150 Div     ,274030
Stage Flow Hydrograph=K100-00-00      ,US K150 Div     ,272601
Stage Flow Hydrograph=K100-00-00      ,US K150 Div     ,271395
Stage Flow Hydrograph=K100-00-00      ,US K150 Div     ,270356
Stage Flow Hydrograph=K100-00-00      ,US K150 Div     ,269458
Stage Flow Hydrograph=K100-00-00      ,US K150 Div     ,268288
Stage Flow Hydrograph=K100-00-00      ,US K150 Div     ,266491
Stage Flow Hydrograph=K100-00-00      ,US K150 Div     ,266161.
Stage Flow Hydrograph=K100-00-00      ,US K150 Div     ,266065
Stage Flow Hydrograph=K100-00-00      ,US K150 Div     ,266005
Stage Flow Hydrograph=K100-00-00      ,US K150 Div     ,265916.
Stage Flow Hydrograph=K100-00-00      ,US K150 Div     ,265696
Stage Flow Hydrograph=K100-00-00      ,US K150 Div     ,264165
Stage Flow Hydrograph=K100-00-00      ,US K150 Div     ,262916
Stage Flow Hydrograph=K100-00-00      ,US K150 Div     ,262434
Stage Flow Hydrograph=K100-00-00      ,US K150 Div     ,260447
Stage Flow Hydrograph=K100-00-00      ,US K150 Div     ,259337
Stage Flow Hydrograph=K100-00-00      ,US K150 Div     ,257633
Stage Flow Hydrograph=K100-00-00      ,US K150 Div     ,256348
Stage Flow Hydrograph=K100-00-00      ,US K150 Div     ,255599
Stage Flow Hydrograph=K100-00-00      ,US K150 Div     ,254087
Stage Flow Hydrograph=K100-00-00      ,US K150 Div     ,252373
Stage Flow Hydrograph=K100-00-00      ,US K150 Div     ,251646.
Stage Flow Hydrograph=K100-00-00      ,US K150 Div     ,251527
Stage Flow Hydrograph=K100-00-00      ,US K150 Div     ,251475
Stage Flow Hydrograph=K100-00-00      ,US K150 Div     ,251450
Stage Flow Hydrograph=K100-00-00      ,US K150 Div     ,251429
Stage Flow Hydrograph=K100-00-00      ,US K150 Div     ,251335
Stage Flow Hydrograph=K100-00-00      ,US K150 Div     ,250102
Stage Flow Hydrograph=K100-00-00      ,US K150 Div     ,249192
Stage Flow Hydrograph=K100-00-00      ,US K150 Div     ,248048
Stage Flow Hydrograph=K100-00-00      ,US K150 Div     ,247215
Stage Flow Hydrograph=K100-00-00      ,US K150 Div     ,245509
Stage Flow Hydrograph=K100-00-00      ,US K150 Div     ,245355.
Stage Flow Hydrograph=K100-00-00      ,US K150 Div     ,245276
Stage Flow Hydrograph=K100-00-00      ,US K150 Div     ,245253
Stage Flow Hydrograph=K100-00-00      ,US K150 Div     ,245155.
Stage Flow Hydrograph=K100-00-00      ,US K150 Div     ,244597
Stage Flow Hydrograph=K100-00-00      ,US K150 Div     ,243570
Stage Flow Hydrograph=K100-00-00      ,US K150 Div     ,242425
Stage Flow Hydrograph=K100-00-00      ,US K150 Div     ,240447
Stage Flow Hydrograph=K100-00-00      ,US K150 Div     ,240049.
Stage Flow Hydrograph=K100-00-00      ,US K150 Div     ,239947
Stage Flow Hydrograph=K100-00-00      ,US K150 Div     ,239899
Stage Flow Hydrograph=K100-00-00      ,US K150 Div     ,239803.
Stage Flow Hydrograph=K100-00-00      ,US K150 Div     ,238992
Stage Flow Hydrograph=K100-00-00      ,US K150 Div     ,237222
Stage Flow Hydrograph=K100-00-00      ,US K150 Div     ,236252
Stage Flow Hydrograph=K100-00-00      ,US K150 Div     ,234886
Stage Flow Hydrograph=K100-00-00      ,US K150 Div     ,234132
Stage Flow Hydrograph=K100-00-00      ,US K150 Div     ,233592
Stage Flow Hydrograph=K100-00-00      ,US K150 Div     ,232118
Stage Flow Hydrograph=K100-00-00      ,US K150 Div     ,230913
Stage Flow Hydrograph=K100-00-00      ,US K150 Div     ,229343
Stage Flow Hydrograph=K100-00-00      ,US K150 Div     ,228591
Stage Flow Hydrograph=K100-00-00      ,US K150 Div     ,226696
Stage Flow Hydrograph=K100-00-00      ,US K150 Div     ,225959
Stage Flow Hydrograph=K100-00-00      ,US K150 Div     ,224004
Stage Flow Hydrograph=K100-00-00      ,US K150 Div     ,222338
Stage Flow Hydrograph=K100-00-00      ,US K150 Div     ,222073.
Stage Flow Hydrograph=K100-00-00      ,US K150 Div     ,221973
Stage Flow Hydrograph=K100-00-00      ,US K150 Div     ,221911
Stage Flow Hydrograph=K100-00-00      ,US K150 Div     ,221811.
Stage Flow Hydrograph=K100-00-00      ,US K150 Div     ,221801
Stage Flow Hydrograph=K100-00-00      ,US K150 Div     ,221068
Stage Flow Hydrograph=K100-00-00      ,US K150 Div     ,219947
Stage Flow Hydrograph=K100-00-00      ,US K150 Div     ,219081
Stage Flow Hydrograph=K100-00-00      ,US K150 Div     ,217788
Stage Flow Hydrograph=K100-00-00      ,US K150 Div     ,216172
Stage Flow Hydrograph=K100-00-00      ,US K150 Div     ,214318
Stage Flow Hydrograph=K100-00-00      ,US K150 Div     ,213508
Stage Flow Hydrograph=K100-00-00      ,US K150 Div     ,211854
Stage Flow Hydrograph=K100-00-00      ,US K150 Div     ,210086
Stage Flow Hydrograph=K100-00-00      ,US K150 Div     ,209229
Stage Flow Hydrograph=K100-00-00      ,US K150 Div     ,207906
Stage Flow Hydrograph=K100-00-00      ,US K150 Div     ,206984
Stage Flow Hydrograph=K100-00-00      ,US K150 Div     ,205406
Stage Flow Hydrograph=K100-00-00      ,US K150 Div     ,204585
Stage Flow Hydrograph=K100-00-00      ,US K150 Div     ,203403
Stage Flow Hydrograph=K100-00-00      ,US K150 Div     ,202422
Stage Flow Hydrograph=K100-00-00      ,US K150 Div     ,201289
Stage Flow Hydrograph=K100-00-00      ,US K150 Div     ,200580
Stage Flow Hydrograph=K100-00-00      ,US K150 Div     ,199171
Stage Flow Hydrograph=K100-00-00      ,US K150 Div     ,197996
Stage Flow Hydrograph=K100-00-00      ,US K150 Div     ,196391
Stage Flow Hydrograph=K100-00-00      ,US K150 Div     ,195672
Stage Flow Hydrograph=K100-00-00      ,US K150 Div     ,194416
Stage Flow Hydrograph=K100-00-00      ,US K150 Div     ,194075
Stage Flow Hydrograph=K100-00-00      ,US K150 Div     ,193386
Stage Flow Hydrograph=K100-00-00      ,DS K150 Div     ,191951
Stage Flow Hydrograph=K100-00-00      ,DS K150 Div     ,190807
Stage Flow Hydrograph=K100-00-00      ,DS K150 Div     ,190457.
Stage Flow Hydrograph=K100-00-00      ,DS K150 Div     ,190362
Stage Flow Hydrograph=K100-00-00      ,DS K150 Div     ,190317
Stage Flow Hydrograph=K100-00-00      ,DS K150 Div     ,190211.
Stage Flow Hydrograph=K100-00-00      ,DS K150 Div     ,189564
Stage Flow Hydrograph=K100-00-00      ,DS K150         ,187983
Stage Flow Hydrograph=K100-00-00      ,DS K150         ,186937
Stage Flow Hydrograph=K100-00-00      ,DS K150         ,185713
Stage Flow Hydrograph=K100-00-00      ,DS K150         ,185488.
Stage Flow Hydrograph=K100-00-00      ,DS K150         ,185278
Stage Flow Hydrograph=K100-00-00      ,DS K150         ,185222
Stage Flow Hydrograph=K100-00-00      ,DS K150         ,185028.
Stage Flow Hydrograph=K100-00-00      ,DS K150         ,184753
Stage Flow Hydrograph=K100-00-00      ,DS K150         ,183827
Stage Flow Hydrograph=K100-00-00      ,DS K150         ,182368
Stage Flow Hydrograph=K100-00-00      ,DS K150         ,180551
Stage Flow Hydrograph=K100-00-00      ,DS K150         ,178635
Stage Flow Hydrograph=K100-00-00      ,DS K150         ,176773
Stage Flow Hydrograph=K100-00-00      ,DS K150         ,175264
Stage Flow Hydrograph=K100-00-00      ,DS K150         ,174850.
Stage Flow Hydrograph=K100-00-00      ,DS K150         ,174737
Stage Flow Hydrograph=K100-00-00      ,DS K150         ,174712
Stage Flow Hydrograph=K100-00-00      ,DS K150         ,174645
Stage Flow Hydrograph=K100-00-00      ,DS K150         ,174614
Stage Flow Hydrograph=K100-00-00      ,DS K150         ,174515
Stage Flow Hydrograph=K100-00-00      ,DS K150         ,174446
Stage Flow Hydrograph=K100-00-00      ,DS K150         ,174414
Stage Flow Hydrograph=K100-00-00      ,DS K150         ,174181
Stage Flow Hydrograph=K100-00-00      ,DS K150         ,174160
Stage Flow Hydrograph=K100-00-00      ,DS K150         ,174137
Stage Flow Hydrograph=K100-00-00      ,DS K150         ,173866.
Stage Flow Hydrograph=K100-00-00      ,DS K150         ,173590
Stage Flow Hydrograph=K100-00-00      ,DS K150         ,172338
Stage Flow Hydrograph=K100-00-00      ,DS K150         ,170765
Stage Flow Hydrograph=K100-00-00      ,DS K150         ,170585
Stage Flow Hydrograph=K100-00-00      ,DS K150         ,170526
Stage Flow Hydrograph=K100-00-00      ,DS K150         ,170401.
Stage Flow Hydrograph=K100-00-00      ,DS K150         ,170004
Stage Flow Hydrograph=K100-00-00      ,DS K150         ,168614
Stage Flow Hydrograph=K100-00-00      ,DS K150         ,167592
Stage Flow Hydrograph=K100-00-00      ,DS K150         ,166998
Stage Flow Hydrograph=K100-00-00      ,DS K150         ,166479
Stage Flow Hydrograph=K100-00-00      ,DS K150         ,164989
Stage Flow Hydrograph=K100-00-00      ,DS K150         ,163957
Stage Flow Hydrograph=K100-00-00      ,DS K150         ,162447
Stage Flow Hydrograph=K100-00-00      ,DS K150         ,160778
Stage Flow Hydrograph=K100-00-00      ,DS K150         ,160351.
Stage Flow Hydrograph=K100-00-00      ,DS K150         ,160245
Stage Flow Hydrograph=K100-00-00      ,DS K150         ,160148
Stage Flow Hydrograph=K100-00-00      ,DS K150         ,160042.
Stage Flow Hydrograph=K100-00-00      ,DS K150         ,159764
Stage Flow Hydrograph=K100-00-00      ,DS K150         ,158469
Stage Flow Hydrograph=K100-00-00      ,DS K150         ,156881
Stage Flow Hydrograph=K100-00-00      ,DS K150         ,155825
Stage Flow Hydrograph=K100-00-00      ,DS K150         ,154677
Stage Flow Hydrograph=K100-00-00      ,DS K150         ,153727
Stage Flow Hydrograph=K100-00-00      ,DS K150         ,152335
Stage Flow Hydrograph=K100-00-00      ,DS K150         ,151314.
Stage Flow Hydrograph=K100-00-00      ,DS K150         ,151214
Stage Flow Hydrograph=K100-00-00      ,DS K150         ,151153
Stage Flow Hydrograph=K100-00-00      ,DS K150         ,151057.
Stage Flow Hydrograph=K100-00-00      ,DS K150         ,149704
Stage Flow Hydrograph=K100-00-00      ,DS K150         ,149014
Stage Flow Hydrograph=K100-00-00      ,DS K150         ,148434
Stage Flow Hydrograph=K100-00-00      ,DS K150         ,147865
Stage Flow Hydrograph=K100-00-00      ,DS K150         ,146710
Stage Flow Hydrograph=K100-00-00      ,DS K150         ,145901
Stage Flow Hydrograph=K100-00-00      ,DS K150         ,144516
Stage Flow Hydrograph=K100-00-00      ,DS K150         ,143628
Stage Flow Hydrograph=K100-00-00      ,DS K150         ,142175
Stage Flow Hydrograph=K100-00-00      ,DS K150         ,141381
Stage Flow Hydrograph=K100-00-00      ,DS K150         ,140143
Stage Flow Hydrograph=K100-00-00      ,DS K150         ,139166
Stage Flow Hydrograph=K100-00-00      ,DS K150         ,138523.
Stage Flow Hydrograph=K100-00-00      ,DS K150         ,138420
Stage Flow Hydrograph=K100-00-00      ,DS K150         ,138363
Stage Flow Hydrograph=K100-00-00      ,DS K150         ,138264.
Stage Flow Hydrograph=K100-00-00      ,DS K150         ,137950
Stage Flow Hydrograph=K100-00-00      ,DS K150         ,135966
Stage Flow Hydrograph=K100-00-00      ,DS K150         ,134226
Stage Flow Hydrograph=K100-00-00      ,DS K150         ,134004.
Stage Flow Hydrograph=K100-00-00      ,DS K150         ,133905
Stage Flow Hydrograph=K100-00-00      ,DS K150         ,133844
Stage Flow Hydrograph=K100-00-00      ,DS K150         ,133720.
Stage Flow Hydrograph=K100-00-00      ,DS K150         ,133259
Stage Flow Hydrograph=K100-00-00      ,DS K150         ,131653
Stage Flow Hydrograph=K100-00-00      ,DS K150         ,130112
Stage Flow Hydrograph=K100-00-00      ,DS K150         ,128649
Stage Flow Hydrograph=K100-00-00      ,DS K150         ,127383.
Stage Flow Hydrograph=K100-00-00      ,DS K150         ,127187
Stage Flow Hydrograph=K100-00-00      ,DS K150         ,127079
Stage Flow Hydrograph=K100-00-00      ,DS K150         ,126877.
Stage Flow Hydrograph=K100-00-00      ,DS K150         ,125669
Stage Flow Hydrograph=K100-00-00      ,DS K150         ,124910.
Stage Flow Hydrograph=K100-00-00      ,DS K150         ,124810
Stage Flow Hydrograph=K100-00-00      ,DS K150         ,124694
Stage Flow Hydrograph=K100-00-00      ,DS K150         ,124593.
Stage Flow Hydrograph=K100-00-00      ,DS K150         ,124097
Stage Flow Hydrograph=K100-00-00      ,DS K150         ,123437.
Stage Flow Hydrograph=K100-00-00      ,DS K150         ,123344
Stage Flow Hydrograph=K100-00-00      ,DS K150         ,123316
Stage Flow Hydrograph=K100-00-00      ,DS K150         ,123212.
Stage Flow Hydrograph=K100-00-00      ,DS K150         ,122086
Stage Flow Hydrograph=K100-00-00      ,DS K150         ,120997
Stage Flow Hydrograph=K100-00-00      ,DS K150         ,119576
Stage Flow Hydrograph=K100-00-00      ,DS K150         ,118501.
Stage Flow Hydrograph=K100-00-00      ,DS K150         ,118399
Stage Flow Hydrograph=K100-00-00      ,DS K150         ,118064
Stage Flow Hydrograph=K100-00-00      ,DS K150         ,117950.
Stage Flow Hydrograph=K100-00-00      ,DS K150         ,116864
Stage Flow Hydrograph=K100-00-00      ,DS K150         ,115085
Stage Flow Hydrograph=K100-00-00      ,DS K150         ,113128
Stage Flow Hydrograph=K100-00-00      ,DS K150         ,111804
Stage Flow Hydrograph=K100-00-00      ,DS K150         ,111533.
Stage Flow Hydrograph=K100-00-00      ,DS K150         ,111378
Stage Flow Hydrograph=K100-00-00      ,DS K150         ,111284
Stage Flow Hydrograph=K100-00-00      ,DS K150         ,111078.
Stage Flow Hydrograph=K100-00-00      ,DS K150         ,110864
Stage Flow Hydrograph=K100-00-00      ,DS K150         ,109706
Stage Flow Hydrograph=K100-00-00      ,DS K150         ,109583.
Stage Flow Hydrograph=K100-00-00      ,DS K150         ,109428
Stage Flow Hydrograph=K100-00-00      ,DS K150         ,109400
Stage Flow Hydrograph=K100-00-00      ,DS K150         ,109300.
Stage Flow Hydrograph=K100-00-00      ,DS K150         ,108918
Stage Flow Hydrograph=K100-00-00      ,DS K150         ,108501.
Stage Flow Hydrograph=K100-00-00      ,DS K150         ,108274
Stage Flow Hydrograph=K100-00-00      ,DS K150         ,108188
Stage Flow Hydrograph=K100-00-00      ,DS K150         ,107974.
Stage Flow Hydrograph=K100-00-00      ,DS K150         ,107642
Stage Flow Hydrograph=K100-00-00      ,DS K150         ,106632
Stage Flow Hydrograph=K100-00-00      ,DS K150         ,104790
Stage Flow Hydrograph=K100-00-00      ,DS K150         ,103431
Stage Flow Hydrograph=K100-00-00      ,DS K150         ,103030
Stage Flow Hydrograph=K100-00-00      ,DS K150         ,102901
Stage Flow Hydrograph=K100-00-00      ,DS K150         ,102875
Stage Flow Hydrograph=K100-00-00      ,DS K150         ,102762.
Stage Flow Hydrograph=K100-00-00      ,DS K150         ,102667
Stage Flow Hydrograph=K100-00-00      ,DS K150         ,101787
Stage Flow Hydrograph=K100-00-00      ,DS K150         ,100946
Stage Flow Hydrograph=K100-00-00      ,DS K150         ,99588
Stage Flow Hydrograph=K100-00-00      ,DS K150         ,98945
Stage Flow Hydrograph=K100-00-00      ,DS K150         ,98740
Stage Flow Hydrograph=K100-00-00      ,DS K150         ,98634
Stage Flow Hydrograph=K100-00-00      ,DS K150         ,98373
Stage Flow Hydrograph=K100-00-00      ,DS K150         ,97287
Stage Flow Hydrograph=K100-00-00      ,DS K150         ,96543
Stage Flow Hydrograph=K100-00-00      ,DS K150         ,95525
Stage Flow Hydrograph=K100-00-00      ,DS K150         ,94445
Stage Flow Hydrograph=K100-00-00      ,DS K150         ,93663
Stage Flow Hydrograph=K100-00-00      ,DS K150         ,91723
Stage Flow Hydrograph=K100-00-00      ,DS K150         ,91077
Stage Flow Hydrograph=K100-00-00      ,DS K150         ,90869
Stage Flow Hydrograph=K100-00-00      ,DS K150         ,90765
Stage Flow Hydrograph=K100-00-00      ,DS K150         ,90551
Stage Flow Hydrograph=K100-00-00      ,DS K150         ,89785
Stage Flow Hydrograph=K100-00-00      ,DS K150         ,88708
Stage Flow Hydrograph=K100-00-00      ,DS K150         ,87603
Stage Flow Hydrograph=K100-00-00      ,DS K150         ,86475
Stage Flow Hydrograph=K100-00-00      ,DS K150         ,85145
Stage Flow Hydrograph=K100-00-00      ,DS K150         ,83550
Stage Flow Hydrograph=K100-00-00      ,DS K150         ,82323
Stage Flow Hydrograph=K100-00-00      ,DS K150         ,80450
Stage Flow Hydrograph=K100-00-00      ,DS K150         ,78955
Stage Flow Hydrograph=K100-00-00      ,DS K150         ,78178
Stage Flow Hydrograph=K100-00-00      ,DS K150         ,76574
Stage Flow Hydrograph=K100-00-00      ,DS K150         ,75290
Stage Flow Hydrograph=K100-00-00      ,DS K150         ,73539
Stage Flow Hydrograph=K100-00-00      ,DS K150         ,71757
Stage Flow Hydrograph=K100-00-00      ,DS K150         ,71520
Stage Flow Hydrograph=K100-00-00      ,DS K150         ,71432
Stage Flow Hydrograph=K100-00-00      ,DS K150         ,71179.
Stage Flow Hydrograph=K100-00-00      ,DS K150         ,70967
Stage Flow Hydrograph=K100-00-00      ,DS K150         ,69993
Stage Flow Hydrograph=K100-00-00      ,DS K150         ,69040
Stage Flow Hydrograph=K100-00-00      ,DS K150         ,67953
Stage Flow Hydrograph=K100-00-00      ,DS K150         ,67762.
Stage Flow Hydrograph=K100-00-00      ,DS K150         ,67655
Stage Flow Hydrograph=K100-00-00      ,DS K150         ,67633
Stage Flow Hydrograph=K100-00-00      ,DS K150         ,67533
Stage Flow Hydrograph=K100-00-00      ,DS K150         ,65757
Stage Flow Hydrograph=K100-00-00      ,DS K150         ,63900
Stage Flow Hydrograph=K100-00-00      ,DS K150         ,62702
Stage Flow Hydrograph=K100-00-00      ,DS K150         ,61150
Stage Flow Hydrograph=K100-00-00      ,DS K150         ,60282
Stage Flow Hydrograph=K100-00-00      ,DS K150         ,58980
Stage Flow Hydrograph=K100-00-00      ,DS K150         ,57388
Stage Flow Hydrograph=K100-00-00      ,DS K150         ,55399
Stage Flow Hydrograph=K100-00-00      ,DS K150         ,53569
Stage Flow Hydrograph=K100-00-00      ,DS K150         ,52461
Stage Flow Hydrograph=K100-00-00      ,DS K150         ,51407
Stage Flow Hydrograph=K100-00-00      ,DS K150         ,51161
Stage Flow Hydrograph=K100-00-00      ,DS K150         ,50807
Stage Flow Hydrograph=K100-00-00      ,DS K150         ,50514
Stage Flow Hydrograph=K100-00-00      ,DS K150         ,49972
Stage Flow Hydrograph=K100-00-00      ,DS K150         ,49009
Stage Flow Hydrograph=K100-00-00      ,DS K150         ,47721
Stage Flow Hydrograph=K100-00-00      ,DS K150         ,46141
Stage Flow Hydrograph=K100-00-00      ,DS K150         ,46131
Stage Flow Hydrograph=K100-00-00      ,DS K150         ,46121
Stage Flow Hydrograph=K100-00-00      ,DS K150         ,45596
Stage Flow Hydrograph=K100-00-00      ,DS K150         ,44408
Stage Flow Hydrograph=K100-00-00      ,DS K150         ,42486
Stage Flow Hydrograph=K100-00-00      ,DS K150         ,42017.
Stage Flow Hydrograph=K100-00-00      ,DS K150         ,41696
Stage Flow Hydrograph=K100-00-00      ,DS K150         ,41578
Stage Flow Hydrograph=K100-00-00      ,DS K150         ,41496
Stage Flow Hydrograph=K100-00-00      ,DS K150         ,41366
Stage Flow Hydrograph=K100-00-00      ,DS K150         ,41320
Stage Flow Hydrograph=K100-00-00      ,DS K150         ,41272
Stage Flow Hydrograph=K100-00-00      ,DS K150         ,41055.
Stage Flow Hydrograph=K100-00-00      ,DS K150         ,40546
Stage Flow Hydrograph=K100-00-00      ,DS K150         ,39789
Stage Flow Hydrograph=K100-00-00      ,DS K150         ,38150
Stage Flow Hydrograph=K100-00-00      ,DS K150         ,36814
Stage Flow Hydrograph=K100-00-00      ,DS K150         ,35492
Stage Flow Hydrograph=K100-00-00      ,DS K150         ,34622
Stage Flow Hydrograph=K100-00-00      ,DS K150         ,33472
Stage Flow Hydrograph=K100-00-00      ,DS K150         ,32385.
Stage Flow Hydrograph=K100-00-00      ,DS K150         ,32215
Stage Flow Hydrograph=K100-00-00      ,DS K150         ,32130
Stage Flow Hydrograph=K100-00-00      ,DS K150         ,32081
Stage Flow Hydrograph=K100-00-00      ,DS K150         ,32056
Stage Flow Hydrograph=K100-00-00      ,DS K150         ,31954.
Stage Flow Hydrograph=K100-00-00      ,DS K150         ,30887
Stage Flow Hydrograph=K100-00-00      ,DS K150         ,29226
Stage Flow Hydrograph=K100-00-00      ,DS K150         ,28109
Stage Flow Hydrograph=K100-00-00      ,DS K150         ,26635
Stage Flow Hydrograph=K100-00-00      ,DS K150         ,26405
Stage Flow Hydrograph=K100-00-00      ,DS K150         ,26344
Stage Flow Hydrograph=K100-00-00      ,DS K150         ,26152.
Stage Flow Hydrograph=K100-00-00      ,DS K150         ,25956
Stage Flow Hydrograph=K100-00-00      ,DS K150         ,24423
Stage Flow Hydrograph=K100-00-00      ,DS K150         ,23894
Stage Flow Hydrograph=K100-00-00      ,DS K150         ,23289
Stage Flow Hydrograph=K100-00-00      ,DS K150         ,22568
Stage Flow Hydrograph=K100-00-00      ,DS K150         ,20680
Stage Flow Hydrograph=K100-00-00      ,DS K150         ,19313
Stage Flow Hydrograph=K100-00-00      ,DS K150         ,18611
Stage Flow Hydrograph=K100-00-00      ,DS K150         ,17183
Stage Flow Hydrograph=K100-00-00      ,DS K150         ,16487
Stage Flow Hydrograph=K100-00-00      ,DS K150         ,14603
Stage Flow Hydrograph=K100-00-00      ,DS K150         ,12763
Stage Flow Hydrograph=K100-00-00      ,DS K150         ,11417
Stage Flow Hydrograph=K100-00-00      ,DS K150         ,10889.
Stage Flow Hydrograph=K100-00-00      ,DS K150         ,10629
Stage Flow Hydrograph=K100-00-00      ,DS K150         ,10534
Stage Flow Hydrograph=K100-00-00      ,DS K150         ,10280.
Stage Flow Hydrograph=K100-00-00      ,DS K150         ,9768
Stage Flow Hydrograph=K100-00-00      ,DS K150         ,8114
Stage Flow Hydrograph=K100-00-00      ,DS K150         ,7033
Stage Flow Hydrograph=K100-00-00      ,DS K150         ,5279
Stage Flow Hydrograph=K100-00-00      ,DS K150         ,3988
Stage Flow Hydrograph=K150-00-00      ,REVISED ALIGN   ,13645
Stage Flow Hydrograph=K150-00-00      ,REVISED ALIGN   ,13640
Stage Flow Hydrograph=K150-00-00      ,REVISED ALIGN   ,13569
Stage Flow Hydrograph=K150-00-00      ,REVISED ALIGN   ,13460
Stage Flow Hydrograph=K150-00-00      ,REVISED ALIGN   ,12824
Stage Flow Hydrograph=K150-00-00      ,REVISED ALIGN   ,12283
Stage Flow Hydrograph=K150-00-00      ,REVISED ALIGN   ,12083
Stage Flow Hydrograph=K150-00-00      ,REVISED ALIGN   ,12007
Stage Flow Hydrograph=K150-00-00      ,REVISED ALIGN   ,11907
Stage Flow Hydrograph=K150-00-00      ,REVISED ALIGN   ,11392
Stage Flow Hydrograph=K150-00-00      ,REVISED ALIGN   ,10900
Stage Flow Hydrograph=K150-00-00      ,REVISED ALIGN   ,10800
Stage Flow Hydrograph=K150-00-00      ,REVISED ALIGN   ,10734
Stage Flow Hydrograph=K150-00-00      ,REVISED ALIGN   ,10634
Stage Flow Hydrograph=K150-00-00      ,REVISED ALIGN   ,10269
Stage Flow Hydrograph=K150-00-00      ,REVISED ALIGN   ,10013
Stage Flow Hydrograph=K150-00-00      ,REVISED ALIGN   ,9913
Stage Flow Hydrograph=K150-00-00      ,REVISED ALIGN   ,9852
Stage Flow Hydrograph=K150-00-00      ,REVISED ALIGN   ,9752
Stage Flow Hydrograph=K150-00-00      ,REVISED ALIGN   ,9222
Stage Flow Hydrograph=K150-00-00      ,REVISED ALIGN   ,8481
Stage Flow Hydrograph=K150-00-00      ,REVISED ALIGN   ,7965
Stage Flow Hydrograph=K150-00-00      ,REVISED ALIGN   ,7854
Stage Flow Hydrograph=K150-00-00      ,REVISED ALIGN   ,7818
Stage Flow Hydrograph=K150-00-00      ,REVISED ALIGN   ,7718
Stage Flow Hydrograph=K150-00-00      ,REVISED ALIGN   ,7200
Stage Flow Hydrograph=K150-00-00      ,REVISED ALIGN   ,7171
Stage Flow Hydrograph=K150-00-00      ,REVISED ALIGN   ,7149
Stage Flow Hydrograph=K150-00-00      ,REVISED ALIGN   ,7084
Stage Flow Hydrograph=K150-00-00      ,REVISED ALIGN   ,6640
Stage Flow Hydrograph=K150-00-00      ,REVISED ALIGN   ,6215
Stage Flow Hydrograph=K150-00-00      ,REVISED ALIGN   ,5624
Stage Flow Hydrograph=K150-00-00      ,REVISED ALIGN   ,5567
Stage Flow Hydrograph=K150-00-00      ,REVISED ALIGN   ,5537
Stage Flow Hydrograph=K150-00-00      ,REVISED ALIGN   ,5494
Stage Flow Hydrograph=K150-00-00      ,REVISED ALIGN   ,5444
Stage Flow Hydrograph=K150-00-00      ,REVISED ALIGN   ,5240
Stage Flow Hydrograph=K150-00-00      ,REVISED ALIGN   ,4773
Stage Flow Hydrograph=K150-00-00      ,REVISED ALIGN   ,4689
Stage Flow Hydrograph=K150-00-00      ,REVISED ALIGN   ,4558
Stage Flow Hydrograph=K150-00-00      ,REVISED ALIGN   ,4239
Stage Flow Hydrograph=K150-00-00      ,REVISED ALIGN   ,4037
Stage Flow Hydrograph=K150-00-00      ,REVISED ALIGN   ,3881
Stage Flow Hydrograph=K150-00-00      ,REVISED ALIGN   ,3612
Stage Flow Hydrograph=K150-00-00      ,REVISED ALIGN   ,3190
Stage Flow Hydrograph=K150-00-00      ,REVISED ALIGN   ,3046
Stage Flow Hydrograph=K150-00-00      ,REVISED ALIGN   ,2915
Stage Flow Hydrograph=K150-00-00      ,REVISED ALIGN   ,2648
Stage Flow Hydrograph=K150-00-00      ,REVISED ALIGN   ,2418
Stage Flow Hydrograph=K150-00-00      ,REVISED ALIGN   ,2090
Stage Flow Hydrograph=K150-00-00      ,REVISED ALIGN   ,1925
Stage Flow Hydrograph=K150-00-00      ,REVISED ALIGN   ,1719
Stage Flow Hydrograph=K150-00-00      ,REVISED ALIGN   ,1652
Stage Flow Hydrograph=K150-00-00      ,REVISED ALIGN   ,1344
Stage Flow Hydrograph=K150-00-00      ,REVISED ALIGN   ,1293
Stage Flow Hydrograph=K150-00-00      ,REVISED ALIGN   ,973
Stage Flow Hydrograph=K150-00-00      ,REVISED ALIGN   ,699
Stage Flow Hydrograph=K150-00-00      ,REVISED ALIGN   ,502
Stage Flow Hydrograph=K150-00-00      ,REVISED ALIGN   ,350
Stage Flow Hydrograph=K150-00-00      ,REVISED ALIGN   ,286
Stage Flow Hydrograph=K150-00-00      ,REVISED ALIGN   ,250
Stage Flow Hydrograph=K150-00-00      ,REVISED ALIGN   ,210
Stage Flow Hydrograph=K150-00-00      ,REVISED ALIGN   ,100
Stage Flow Hydrograph=K150-00-00      ,REVISED ALIGN   ,95
Stage Flow Hydrograph=K150-00-00      ,REVISED ALIGN   ,85
Stage Flow Hydrograph=K150-00-00      ,DS_DIVERSION    ,6515
Stage Flow Hydrograph=K150-00-00      ,DS_DIVERSION    ,6500
Stage Flow Hydrograph=K150-00-00      ,DS_DIVERSION    ,5654
Stage Flow Hydrograph=K150-00-00      ,DS_DIVERSION    ,5554
Stage Flow Hydrograph=K150-00-00      ,DS_DIVERSION    ,5462
Stage Flow Hydrograph=K150-00-00      ,DS_DIVERSION    ,5352
Stage Flow Hydrograph=K150-00-00      ,DS_DIVERSION    ,4365
Stage Flow Hydrograph=K150-00-00      ,DS_DIVERSION    ,3442
Stage Flow Hydrograph=K150-00-00      ,DS_DIVERSION    ,2605
Stage Flow Hydrograph=K150-00-00      ,DS_DIVERSION    ,2145
Stage Flow Hydrograph=K150-00-00      ,DS_DIVERSION    ,2095
Stage Flow Hydrograph=K150-00-00      ,DS_DIVERSION    ,1797
Stage Flow Hydrograph=K150-00-00      ,DS_DIVERSION    ,1795
Stage Flow Hydrograph=K150-00-00      ,DS_DIVERSION    ,1751
Stage Flow Hydrograph=K150-00-00      ,DS_DIVERSION    ,1642
Stage Flow Hydrograph=K150-00-00      ,DS_DIVERSION    ,1585
Stage Flow Hydrograph=K150-00-00      ,DS_DIVERSION    ,1385
Stage Flow Hydrograph=K150-00-00      ,DS_DIVERSION    ,862
Stage Flow Hydrograph=K150-00-00      ,DS_DIVERSION    ,740
Stage Flow Hydrograph=K150-00-00      ,DS_DIVERSION    ,705
Stage Flow Hydrograph=K150-00-00      ,DS_DIVERSION    ,605
Stage Flow Hydrograph=K150-00-00      ,DS_DIVERSION    ,409
Stage Flow Hydrograph=K150-00-00      ,DS_DIVERSION    ,400
Stage Flow Hydrograph=K150-00-00      ,DS_DIVERSION    ,380

--- K150-01-00.p02 (plan) ---

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Plan Title=FEMA Effective Floodway 2017
Short Identifier=K150-01_FW
Geom File=g01
Flow File=f02
Encroach River=K150-01-00
       1  4942.3  5045.7
       1 4924.63 5022.25
       1  4966.4 5072.99
       1  4966.4 5072.99
       1  4966.4 5072.99
       1  4966.4  5036.4
       1 4968.45 5050.58
       1  4970.6 5028.75
       1 4983.32    5072
       1 4965.57 5048.42
       1 4974.57 5048.42
       1 4991.83 5039.03
       1 4991.83 5039.03
       1 4994.14 5039.03
       1    4988 5007.31
       1    4978 5017.31
       1 4980.09 5021.17
       1 4985.55 5030.06
       1  4976.3  5036.3
       1  4976.3  5036.3
       1  4976.3 5037.25
       1  4976.3  5036.3
       1  4976.1  5036.1
       1  4976.1  5036.1
FEMA Effective Floodway June 2007 + LOMR 07-06-1885P +16-06-0557P + 17-06-0430X

--- K150-01-00.f01 (steady flow) ---

Flow Title=Effective Multi-Profile 2017
Program Version=3.13
Number of Profiles= 4
Profile Names=10-YR,50-YR,100-YR,500-YR
River Rch & RM=K150-01-00,DS_DIVERSION    ,6512
   51.46  157.84     216  362.87
River Rch & RM=K150-01-00,DS_DIVERSION    ,5355
     231     239     247     256
River Rch & RM=K150-01-00,DS_DIVERSION    ,1593
     385     470     494     530
Boundary for River Rch & Prof#=K150-01-00,DS_DIVERSION    , 1
Up Type= 0
Dn Type= 3
Dn Slope=0.0026
Boundary for River Rch & Prof#=K150-01-00,DS_DIVERSION    , 2
Up Type= 0
Dn Type= 3
Dn Slope=0.0026
Boundary for River Rch & Prof#=K150-01-00,DS_DIVERSION    , 3
Up Type= 0
Dn Type= 3
Dn Slope=0.0026
Boundary for River Rch & Prof#=K150-01-00,DS_DIVERSION    , 4
Up Type= 0
Dn Type= 3
Dn Slope=0.0026
DSS Import GetInterval= 0
DSS Import GetPeak= 0
DSS Import FillOption= 0

--- K150-01-00.f02 (steady flow) ---

Flow Title=Effective Floodway 2017
Program Version=3.13
Number of Profiles= 2
Profile Names=100-YR,FW
River Rch & RM=K150-01-00,DS_DIVERSION    ,6512
     216     216
River Rch & RM=K150-01-00,DS_DIVERSION    ,5355
     247     247
River Rch & RM=K150-01-00,DS_DIVERSION    ,1593
     494     494
Boundary for River Rch & Prof#=K150-01-00,DS_DIVERSION    , 1
Up Type= 0
Dn Type= 3
Dn Slope=0.0026
Boundary for River Rch & Prof#=K150-01-00,DS_DIVERSION    , 2
Up Type= 0
Dn Type= 3
Dn Slope=0.0026
DSS Import GetInterval= 0
DSS Import GetPeak= 0
DSS Import FillOption= 0

--- K150-01-00.g01 (geometry) ---

Geom Title=K150-01-00 2017
Program Version=3.13

River Reach=K150-01-00      ,DS_DIVERSION
Reach XY= 30
 3004555.346007313906623.0615082      3004903.49     13906800.84
      3005039.13     13906822.54      3005490.04     13906829.23
      3005981.78     13906865.94      3006523.96     13906853.76
      3006865.11     13907008.27      3006920.71     13907079.53
      3006966.17      13907211.5      3007056.65     13907767.63
       3007278.3     13908513.48      3007264.41     13908653.24
      3007280.04     13908696.64      3007676.74     13909046.47
      3007868.58     13909132.41      3007916.32     13909174.94
      3008142.25       13909547.      3008129.87     13909652.37
      3008227.09     13909748.73      3008418.06     13909824.25
      3008517.89     13909841.61       3008607.3     13909799.07
      3008635.07     13909846.82 3008672.407022713909855.2384078
 3008704.397646113909848.8402832      3008723.62     13909813.83
      3008776.57     13909816.43      3008813.03     13909869.38
      3008870.32     13909905.84   3008981.49993       13909882.

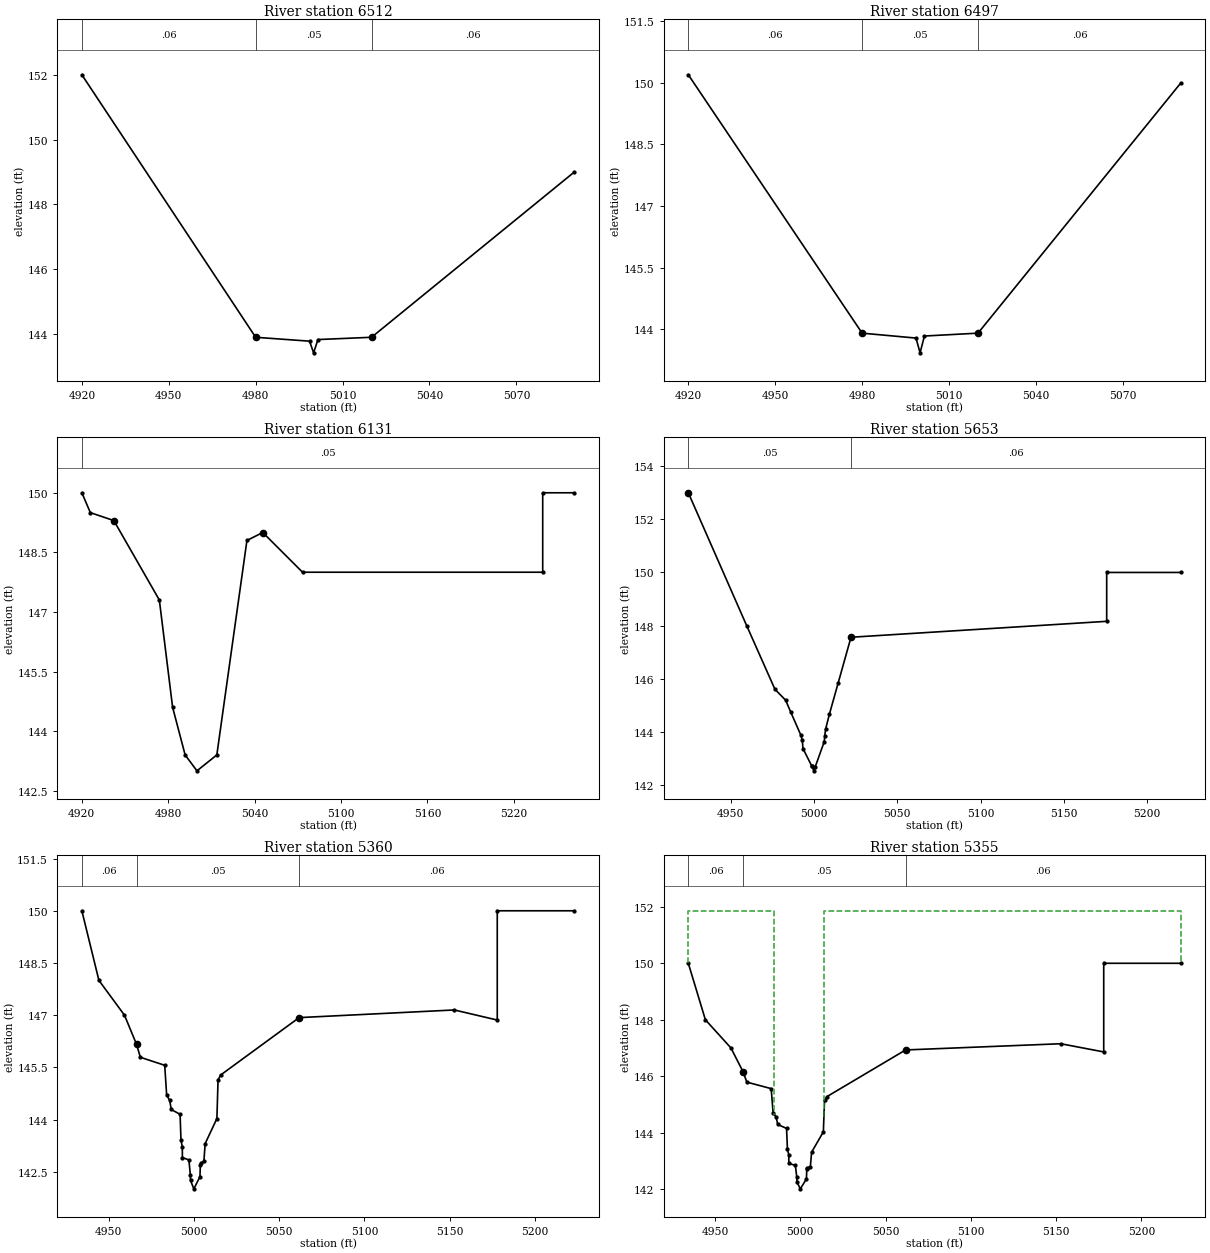
Type RM Length L Ch R = 1 ,6512    ,15,15,15
XS GIS Cut Line= 2
     3004536.409    13906702.474      3004607.12    13906547.894
#Sta/Elev= 7
    4920     152    4980   143.9  4998.6  143.78    5000  143.42  5001.5  143.83
    5020   143.9    5090     149
#Mann= 3 ,-1 , 0
    4920     .06       0    4980     .05       0    5020     .06       0
Bank Sta=4980,5020
Exp/Cntr=0.3,0.1

Type RM Length L Ch R = 1 ,6497    ,365,366,365
XS GIS Cut Line= 2
     3004549.858    13906709.223     3004620.529    13906554.633
#Sta/Elev= 7
    4920   150.2    4980   143.9  4998.6  143.78    5000  143.42  5001.5  143.83
    5020   143.9    5090     150
#Mann= 3 ,-1 , 0
    4920     .06       0    4980     .05       0    5020     .06       0
Bank Sta=4980,5020
Exp/Cntr=0.3,0.1

Type RM Length L Ch R = 1 ,6131    ,533,478,419
XS GIS Cut Line= 2
     3004875.625     13906874.44     3005017.777     13906563.56
#Sta/Elev= 14
  4920.1     150    4926   149.5  4942.3   149.3  4973.9   147.3  4983.1   144.6
  4991.8   143.4    5000     143  5013.8   143.4  5034.7   148.8  5045.7     149
  5073.3     148 5240.03     148 5240.03     150 5261.98     150
#Mann= 1 ,-1 , 0
  4920.1     .05       0
Bank Sta=4942.3,5045.7
Exp/Cntr=0.3,0.1

Type RM Length L Ch R = 1 ,5653    ,289,293,293.43
XS GIS Cut Line= 4
     3005373.491     13906902.66     3005409.506      13906680.3
     3005420.455     13906640.04     3005427.944     13906612.51
#Sta/Elev= 21
 4924.63     153 4959.63     148 4976.62   145.6 4983.04  145.19 4985.97  144.76
 4992.13  143.88 4993.03  143.68 4993.44  143.37 4998.72  142.71 4998.78   142.7
    5000  142.53 5000.79  142.68 5006.21  143.63 5006.54  143.86 5006.98  144.09
 5009.29  144.66 5014.61  145.85 5022.25  147.56 5175.71  148.16 5175.71     150
 5220.18     150
#Mann= 2 ,-1 , 0
 4924.63     .05       0 5022.25     .06       0
Bank Sta=4924.63,5022.25
Exp/Cntr=0.3,0.1

Type RM Length L Ch R = 1 ,5360    ,5,5,5
XS GIS Cut Line= 4
     3005668.472     13906907.58     3005678.301     13906842.65
     3005699.138     13906704.95     3005721.185      13906624.1
#Sta/Elev= 30
 4934.32     150 4944.32     148 4959.32     147  4966.4  146.16 4968.63  145.79
 4982.91  145.56 4984.04  144.71 4985.82  144.55 4986.75  144.29 4991.92  144.15
 4992.45  143.41 4993.22  143.22 4993.28  142.91 4997.08  142.84 4997.93  142.42
 4998.03  142.25    5000  142.01 5003.58  142.36 5003.79   142.7 5004.05  142.75
 5005.88   142.8 5006.63  143.31 5013.51  144.03 5014.18  145.14 5015.69  145.28
 5061.72  146.93 5152.72  147.15 5177.91  146.86 5177.91     150  5223.1     150
#Mann= 3 ,-1 , 0
 4934.32     .06       0  4966.4     .05       0 5061.72     .06       0
Bank Sta=4966.4,5061.72
Exp/Cntr=0.5,0.3

Type RM Length L Ch R = 1 ,5355    ,70,70,70
XS GIS Cut Line= 4
     3005673.412    13906908.327      3005683.24    13906843.395
     3005704.088    13906705.703     3005726.125    13906624.844
#Sta/Elev= 30
 4934.32     150 4944.32     148 4959.32     147  4966.4  146.16 4968.63  145.79
 4982.91  145.56 4984.04  144.71 4985.82  144.55 4986.75  144.29 4991.92  144.15
 4992.45  143.41 4993.22  143.22 4993.28  142.91 4997.08  142.84 4997.93  142.42
 4998.03  142.25    5000  142.01 5003.58  142.36 5003.79   142.7 5004.05  142.75
 5005.88   142.8 5006.63  143.31 5013.51  144.03 5014.18  145.14 5015.69  145.28
 5061.72  146.93 5152.72  147.15 5177.91  146.86 5177.91     150  5223.1     150
#Mann= 3 ,-1 , 0
 4934.32     .06       0  4966.4     .05       0 5061.72     .06       0
#XS Ineff= 2 , 0
    -.68 4984.82  151.86 5013.82    -.68  151.86
Permanent Ineff=
       F       F
Bank Sta=4966.4,5061.72
Exp/Cntr=0.5,0.3

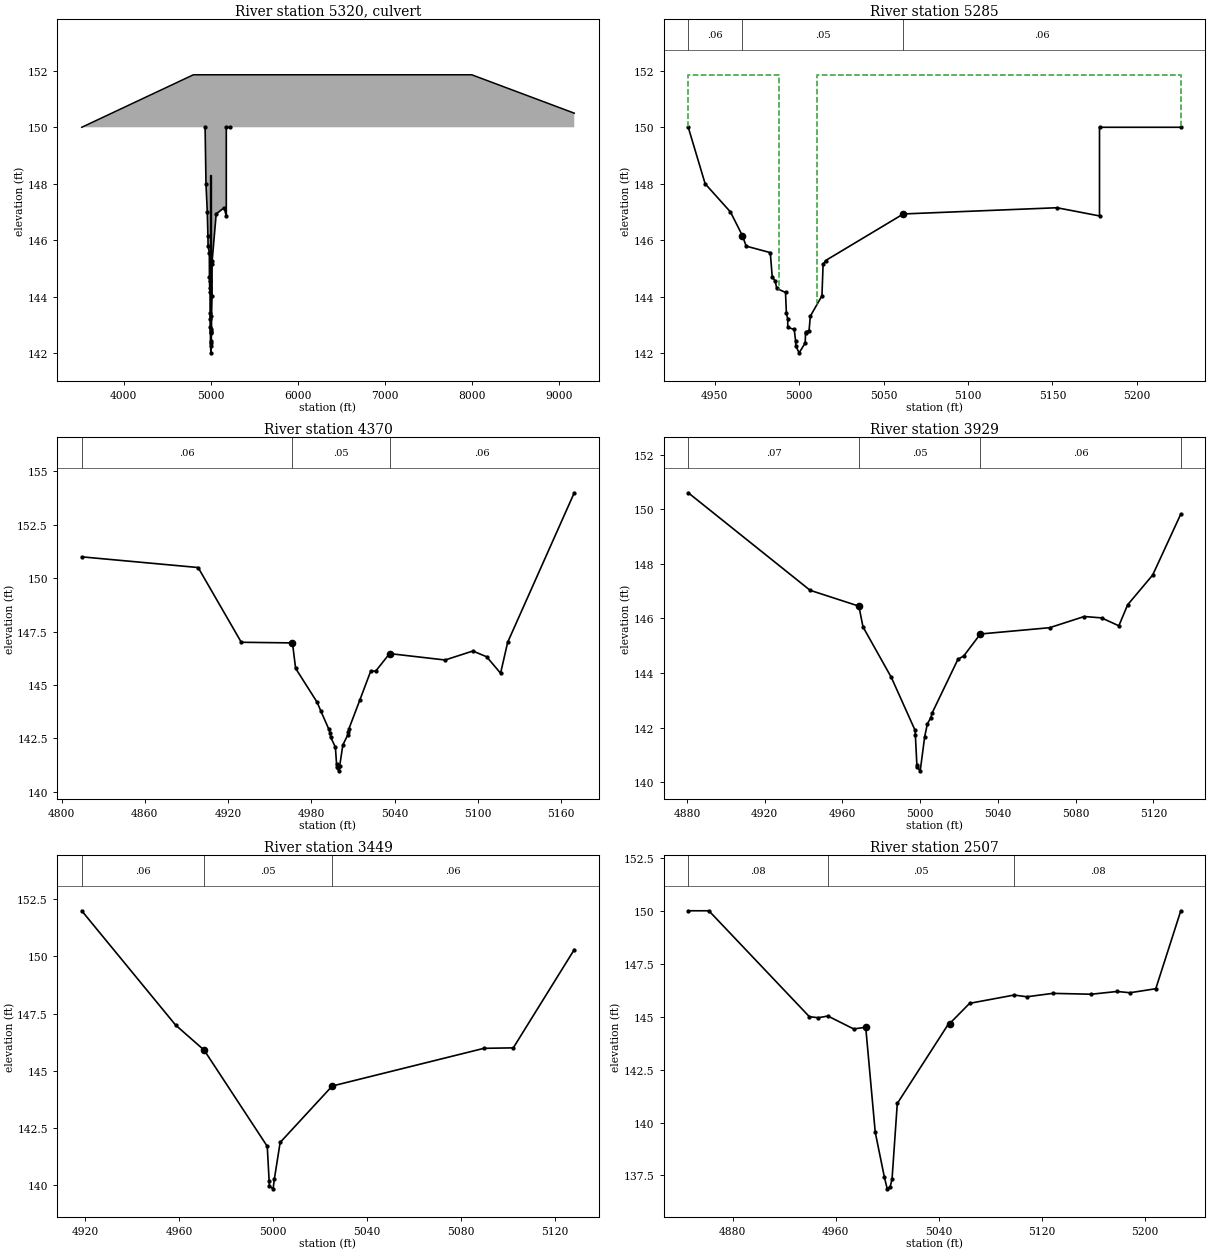
Type RM Length L Ch R = 2 ,5320    ,,,
BEGIN DESCRIPTION:
Williams Reach Drive
END DESCRIPTION:
Bridge Culvert--1,0,-1,-1, 0
Deck Dist Width WeirC Skew NumUp NumDn MinLoCord MaxHiCord MaxSubmerge Is_Ogee
10,39,2.6,0, 4, 4, , , 0.95, 0, 0,0,,
 3516.29 4799.32 7999.32 9177.32
     150  151.86  151.86   150.5
                                
 3508.33 4799.32 7999.32 9178.02
     150  151.86  151.86     150
                                
BR Coef=-1 , 0 , 0 ,, 0 ,,,0.8,-1,,0,
WSPro=,,,, 1 ,,,, 0 ,,,, 0 ,,,,-1 ,-1 ,-1 , 0 , 0 , 0 , 0 , 0
Culvert=2,6,9,39,0.013,0.5,1,8,1,142.3,4999.32,142.3,4999.32,Culvert #1  , 0 ,10
Culvert Bottom n=0.013
BC Design=,, 0 ,, 0 ,,,,,,
BC HTab HWMax=150
BC HTab TWMax=150
BC HTab MaxFlow=1000

Type RM Length L Ch R = 1 ,5285    ,734,915,946.22
XS GIS Cut Line= 5
     3005743.203    13906912.936     3005753.031    13906848.005
     3005772.339    13906720.411     3005788.547    13906660.979
     3005797.845    13906626.843
#Sta/Elev= 30
 4934.32     150 4944.32     148 4959.32     147  4966.4  146.16 4968.63  145.79
 4982.91  145.56 4984.04  144.71 4985.82  144.55 4986.75  144.29 4991.92  144.15
 4992.45  143.41 4993.22  143.22 4993.28  142.91 4997.08  142.84 4997.93  142.42
 4998.03  142.25    5000  142.01 5003.58  142.36 5003.79   142.7 5004.05  142.75
 5005.88   142.8 5006.63  143.31 5013.51  144.03 5014.18  145.14 5015.69  145.28
 5061.72  146.93 5152.72  147.15 5177.91  146.86 5177.91     150 5226.06     150
#Mann= 3 , 0 , 0
 4934.32     .06       0  4966.4     .05       0 5061.72     .06       0
#XS Ineff= 2 , 0
    -.68 4988.12  151.86 5010.52    -.68  151.86
Permanent Ineff=
       F       F
Bank Sta=4966.4,5061.72
Exp/Cntr=0.5,0.3

Type RM Length L Ch R = 1 ,4370    ,266.88,441,540.98
BEGIN DESCRIPTION:
K150-00-00_Interpolated XS2 Revised
END DESCRIPTION:
XS GIS Cut Line= 2
  3006562.39257113907072.5355552  3006736.81059813906763.3351029
#Sta/Elev= 30
  4814.5     151  4898.4   150.5  4929.5     147  4966.4  146.97 4968.65  145.78
 4984.18  144.19 4986.91  143.77 4992.66  142.92  4993.5  142.76 4993.88  142.56
 4997.33  142.09 4998.19  141.28 4998.29  141.15 4998.87  141.09    5000  140.98
 5000.45  141.22 5002.71  142.19 5006.37  142.68 5006.71  142.82 5007.15  142.96
 5014.98   144.3  5022.8  145.65  5026.4  145.65  5036.4  146.47  5076.4  146.17
  5096.4  146.59  5106.4  146.32  5116.4  145.55  5121.5     147  5169.5     154
#Mann= 3 , 0 , 0
  4814.5     .06       0  4966.4     .05       0  5036.4     .06       0
Bank Sta=4966.4,5036.4
Exp/Cntr=0.3,0.1

Type RM Length L Ch R = 1 ,3929    ,280.52,480,568.62
XS GIS Cut Line= 2
     3006870.106     13907267.88     3007061.911    13907102.362
#Sta/Elev= 24
 4880.67   150.6 4943.35  147.03 4968.45  146.45 4970.56  145.69 4985.14  143.84
 4997.32  141.91 4997.49  141.75 4998.28  140.64 4998.39  140.56    5000  140.42
  5002.3  141.67 5003.68  142.14 5005.41  142.36 5006.08  142.53 5019.38   144.5
 5022.44  144.63 5030.94  145.43 5066.56  145.66 5084.37  146.07 5093.27  146.02
 5102.18  145.73 5106.72   146.5  5119.6  147.59 5134.05  149.82
#Mann= 4 ,-1 , 0
 4880.67     .07       0 4968.45     .05       0 5030.94     .06       0
 5134.05     .06       0
Bank Sta=4968.45,5030.94
Exp/Cntr=0.3,0.1

Type RM Length L Ch R = 1 ,3449    ,1029,942,887
XS GIS Cut Line= 2
  3006968.73392313907667.2123452 3007178.312518713907653.1582467
#Sta/Elev= 13
  4918.4     152  4958.4     147  4970.6   145.9  4997.5  141.69  4998.3  140.19
  4998.4  139.95    5000  139.83  5000.5  140.24    5003  141.86  5025.2  144.33
  5089.9  145.98  5102.4     146  5128.4   150.3
#Mann= 3 ,-1 , 0
  4918.4     .06       0  4970.6     .05       0  5025.2     .06       0
Bank Sta=4970.6,5025.2
Exp/Cntr=0.3,0.1

Type RM Length L Ch R = 1 ,2507    ,500,471,330
XS GIS Cut Line= 4
    3007178.9859   13908687.5055    3007243.7675   13908624.5137
    3007304.8995   13908535.9352    3007482.7364   13908482.8321
#Sta/Elev= 24
 4845.57     150 4861.57     150 4939.57     145 4946.57  144.95 4953.97  145.03
 4973.97  144.42 4983.32   144.5 4990.71  139.54 4997.74  137.44    5000  136.87
 5002.25  136.96 5003.74  137.32 5007.82   140.9 5047.58  144.66 5048.42  144.67
 5063.97  145.63 5098.47  146.02 5108.47  145.94 5128.47   146.1 5158.47  146.06
 5178.47  146.19 5188.47  146.13 5208.47  146.32 5227.88     150
#Mann= 3 ,-1 , 0
 4845.57     .08       0 4953.97     .05       0 5098.47     .08       0
Bank Sta=4983.32,5048.42
Exp/Cntr=0.3,0.1