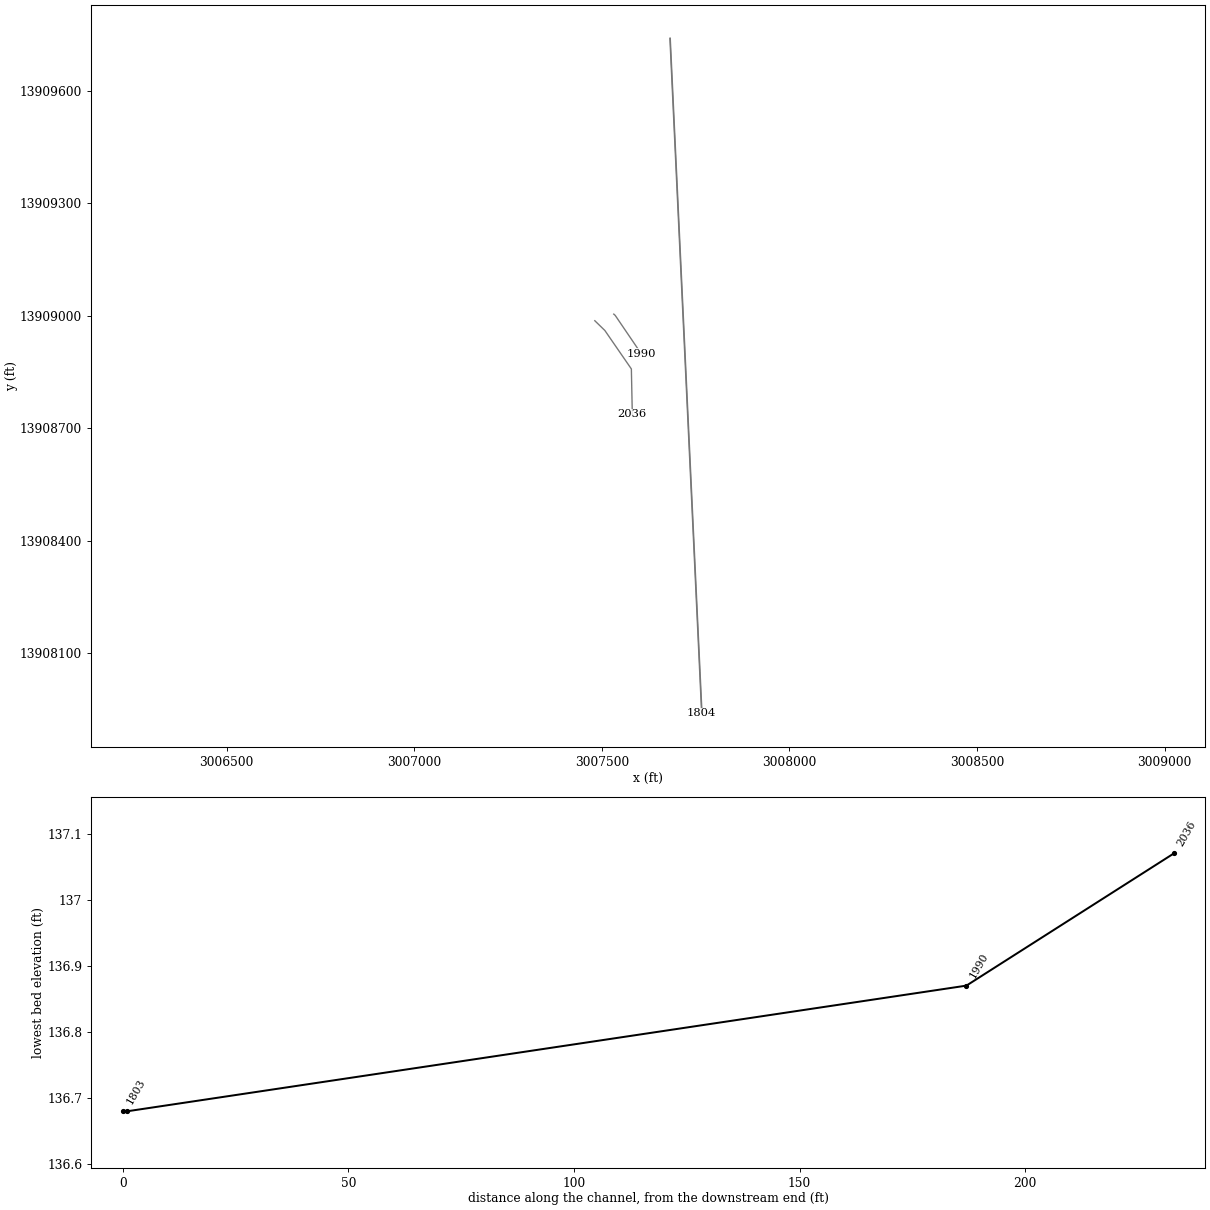
HEC-RAS study K150-01-00.prj: K150-01-00

--- K150-01-00.g01 (geometry) --- (continued)

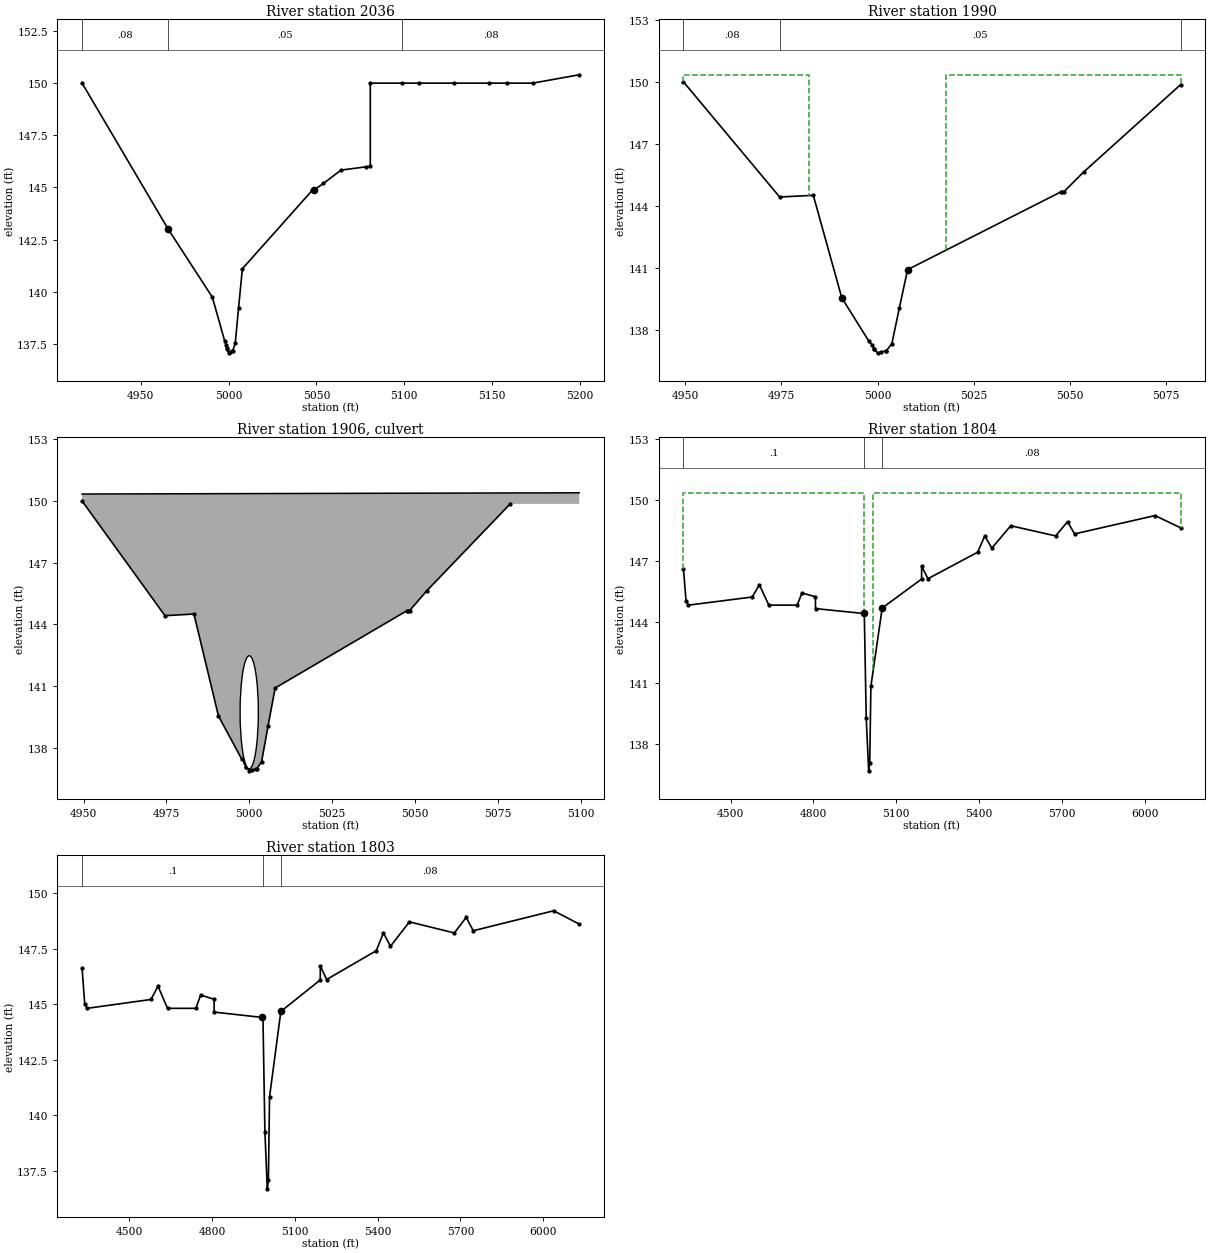
Type RM Length L Ch R = 1 ,2036    ,50,46,50
BEGIN DESCRIPTION:
Revised for fill and proposed road
END DESCRIPTION:
XS GIS Cut Line= 6
    3007481.1566   13908986.6966    3007507.9431     13908960.67
    3007534.0497   13908922.7949    3007571.5949    13908868.322
    3007578.6039   13908858.1434    3007581.1136   13908736.9991
#Sta/Elev= 29
 4916.57     150 4965.57     143 4990.71  139.74 4997.74  137.64 4998.58  137.46
 4999.03  137.28 4999.09  137.26    5000  137.07 5000.94  137.11 5002.08  137.16
 5002.25  137.16 5003.74  137.52 5005.66  139.23 5007.82   141.1 5047.58  144.86
    5048  144.87 5048.42  144.87 5053.97  145.19 5063.97  145.83 5078.47  145.99
 5080.63  146.01 5080.63     150 5098.47     150 5108.47     150 5128.47     150
 5148.47     150 5158.47     150 5173.17     150 5199.57   150.4
#Mann= 3 ,-1 , 0
 4916.57     .08       0 4965.57     .05       0 5098.47     .08       0
Bank Sta=4965.57,5048.42
Exp/Cntr=0.3,0.1

Type RM Length L Ch R = 1 ,1990    ,218,186,195
BEGIN DESCRIPTION:
upstream of North Bridgelands Lake Parkway
END DESCRIPTION:
XS GIS Cut Line= 4
      3007531.71     13909004.34     3007535.491     13909000.98
     3007601.449     13908903.93      3007604.81     13908898.05
#Sta/Elev= 20
 4949.57     150 4974.57  144.42 4983.32   144.5 4990.71  139.54 4997.74  137.44
 4998.58  137.26 4999.03  137.08 4999.09  137.06    5000  136.87 5000.94  136.91
 5002.08  136.96 5002.25  136.96 5003.74  137.32 5005.66  139.03 5007.82   140.9
 5047.58  144.66    5048  144.67 5048.42  144.67 5053.57  145.63 5078.75  149.86
#Mann= 3 ,-1 , 0
 4949.57     .08       0 4974.57     .05       0 5078.75     .08       0
#XS Ineff= 2 , 0
   15.57 4982.25  150.34 5017.75   15.57  150.34
Permanent Ineff=
       F       F
Bank Sta=4990.71,5007.82
Exp/Cntr=0.5,0.3

Type RM Length L Ch R = 2 ,1906    ,,,
BEGIN DESCRIPTION:
North Bridgeland Lake Parkway
END DESCRIPTION:
Bridge Culvert--1,0,-1,-1, 0
Deck Dist Width WeirC Skew NumUp NumDn MinLoCord MaxHiCord MaxSubmerge Is_Ogee
15,150,2.6,0, 2, 2, , , 0.95, 0, 0,0,,
 4949.57 5099.57
  150.34   150.4
                
 4328.61 6130.43
  150.34   150.4
                
BR Coef=-1 , 0 , 0 ,, 0 ,,,0.8,-1,,0,
WSPro=,,,, 1 ,,,, 0 ,,,, 0 ,,,,-1 ,-1 ,-1 , 0 , 0 , 0 , 0 , 0
Culvert=1,5.5,,150,0.013,0.5,1,1,1,136.97,5000,136.8,5000,Culvert #1  , 0 ,15
Culvert Bottom n=0.013
BC Design=,, 0 ,, 0 ,,,,,,
BC HTab HWMax=153
BC HTab MaxFlow=1000

Type RM Length L Ch R = 1 ,1804    ,1,1,1
BEGIN DESCRIPTION:
K150-00-00-S1_UNKNOWN RD - US - XS3
END DESCRIPTION:
XS GIS Cut Line= 3
     3007681.311    13909739.509     3007712.846    13909068.946
      3007765.95    13907939.913
#Sta/Elev= 30
 4328.61  146.62 4338.18  145.02 4346.75  144.82 4578.19  145.22  4603.9  145.82
 4638.19  144.82 4741.05  144.82 4758.19  145.42 4806.96  145.23 4807.39  144.65
 4981.83  144.41 4984.14  144.41 4991.17  139.26    5000  136.68 5003.86  137.07
 5008.06  140.83 5049.03  144.68 5049.89  144.69 5191.83   146.1 5192.09  146.73
 5214.98  146.12 5394.98  147.42  5420.7  148.22 5446.41  147.62 5514.98  148.72
 5677.85  148.22 5720.71  148.92 5746.42  148.32 6037.86  149.22 6130.43  148.62
#Mann= 3 ,-1 , 0
 4328.61      .1       0 4984.14     .06       0 5049.89     .08       0
#XS Ineff= 2 , 0
  715.02 4983.25  150.34 5016.75  715.02  150.34
Permanent Ineff=
       F       F
Bank Sta=4981.83,5049.03
Skew Angle= 31
Exp/Cntr=0.5,0.3

Type RM Length L Ch R = 1 ,1803    ,43,44,46.3
BEGIN DESCRIPTION:
K150-00-00-S1_UNKNOWN RD - US - XS3
END DESCRIPTION:
XS GIS Cut Line= 3
      3007682.31    13909739.559     3007713.846    13909068.996
     3007766.949    13907939.963
#Sta/Elev= 30
 4328.61  146.62 4338.18  145.02 4346.75  144.82 4578.19  145.22  4603.9  145.82
 4638.19  144.82 4741.05  144.82 4758.19  145.42 4806.96  145.23 4807.39  144.65
 4981.83  144.41 4984.14  144.41 4991.17  139.26    5000  136.68 5003.86  137.07
 5008.06  140.83 5049.03  144.68 5049.89  144.69 5191.83   146.1 5192.09  146.73
 5214.98  146.12 5394.98  147.42  5420.7  148.22 5446.41  147.62 5514.98  148.72
 5677.85  148.22 5720.71  148.92 5746.42  148.32 6037.86  149.22 6130.43  148.62
#Mann= 3 ,-1 , 0
 4328.61      .1       0 4984.14     .06       0 5049.89     .08       0
Bank Sta=4981.83,5049.03
Skew Angle= 31
Exp/Cntr=0.5,0.3