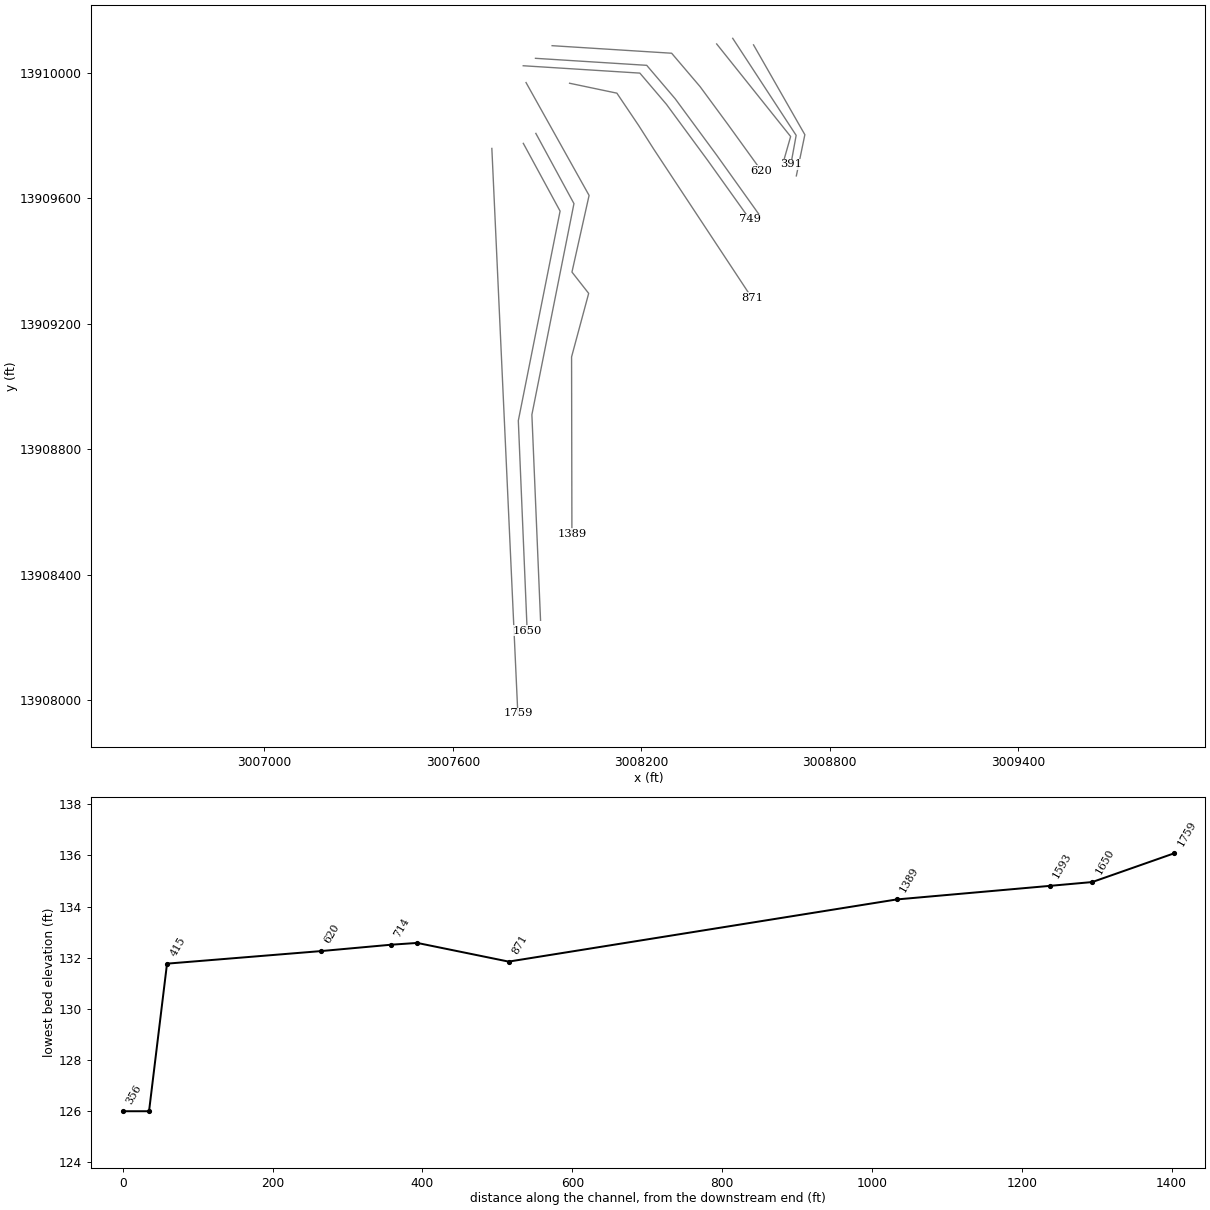
HEC-RAS study K150-01-00.prj: K150-01-00

--- K150-01-00.g01 (geometry) --- (continued)

Type RM Length L Ch R = 2 ,1781    ,,,
BEGIN DESCRIPTION:
UNNAMED ROAD
Structure ID: K150-00-00-S1
END DESCRIPTION:
Bridge Culvert--1,0,-1,-1, 0
Deck Dist Width WeirC Skew NumUp NumDn MinLoCord MaxHiCord MaxSubmerge Is_Ogee
10,24,2.6,31, 53, 53, , , 0.95, 0, ,,,
4329.609 4338.184346.7514466.7564475.3264483.8994578.1874603.9014638.1894689.619
4741.0494749.6214758.1924806.9654807.3944851.2814894.9974943.0824984.1424991.171
4997.8564999.9995002.3145003.8565008.0575049.0295098.7455137.1465191.8325192.091
5206.1485214.977 5386.415394.9825403.5545420.6965446.4125472.1275497.8415514.984
5583.5595669.2745677.8475720.7065746.4195926.4265934.9975960.7116029.2866037.856
    60556080.7166130.432
     146     145   144.8   145.9  145.88  145.87  145.68  145.81  145.57  145.47
  145.36  145.35  145.41  145.24  145.24  145.15  145.21  145.45  146.19  146.23
  146.28   146.3  146.31  146.31  146.29  146.19   146.4  146.54  146.67  146.72
   146.7  146.72  147.51  147.41  148.01  148.21  147.61  148.31  148.21  148.71
  148.21  148.51  148.21  148.91  148.31  148.71  148.51   149.2   148.9   149.2
   148.7   149.1   148.6
     146     145   144.8  145.17   145.2   144.9   145.2   145.8   144.8   145.1
   144.8   145.3   145.4  145.21  144.63  144.67  144.59  144.32  144.39  139.24
  137.13  136.66   136.7  137.05  140.81  144.66  145.43  145.79  146.08  146.71
   146.4   146.1   147.5   147.4     148   148.2   147.6   148.3   148.2   148.7
   148.2   148.5   148.2   148.9   148.3   148.7   148.5   149.2   148.9   149.2
   148.7   149.1   148.6
4329.609 4338.184346.7514466.7564475.3264483.8994578.1874603.9014638.1894689.619
4741.0494749.6214758.1924806.9654807.3944851.2814894.9974943.0824981.8274984.142
4991.1714997.8564999.9995003.8565008.0575049.0295098.7455137.1465191.8325192.091
5206.1485214.977 5386.415394.9825403.5545420.6965446.4125472.1275497.8415514.984
5583.5595669.2745677.8475720.7065746.4195926.4265934.9975960.7116029.2866037.856
    60556080.7166130.432
     146     145   144.8   145.9  145.88  145.87  145.68  145.81  145.57  145.47
  145.36  145.35  145.41  145.24  145.24  145.15  145.21  145.45  146.17  146.19
  146.23  146.28   146.3  146.31  146.29  146.19   146.4  146.54  146.67  146.72
   146.7  146.72  147.51  147.41  148.01  148.21  147.61  148.31  148.21  148.71
  148.21  148.51  148.21  148.91  148.31  148.71  148.51   149.2   148.9   149.2
   148.7   149.1   148.6
  145.53  144.53  144.33   144.7  144.73  144.43  144.73  145.33  144.33  144.63
  144.33  144.83  144.93  144.74  144.16   144.2  144.12  143.85  143.92     143
   138.4   136.4     136     136     140     144  144.96  145.32  145.61  146.24
  145.93  145.63  147.03  146.93  147.53  147.73  147.13  147.83  147.73  148.23
  147.73  148.03  147.73  148.43  147.83  148.23  148.03  148.73  148.43  148.73
  148.23  148.63  148.13
BR Coef= 1 , 0 , 0 ,1.25, 0 ,,,0.8,0,2,1,
WSPro=,,,, 1 ,,,, 0 ,,,, 0 ,,,,-1 ,-1 ,-1 , 0 , 0 , 0 , 0 , 0
Culvert=1,7,,24,0.024,0.5,1,2,1,136.74,5000.857,136.14,5000.857,Culvert #1  , 0 ,10
Culvert Bottom n=0.024
BC Design=,, 0 ,, 0 ,,,,,,
BC HTab Sub Flow Curves= 50
BC HTab Sub Flow Pts= 30
BC HTab HWMax=150
BC HTab MaxFlow=2700

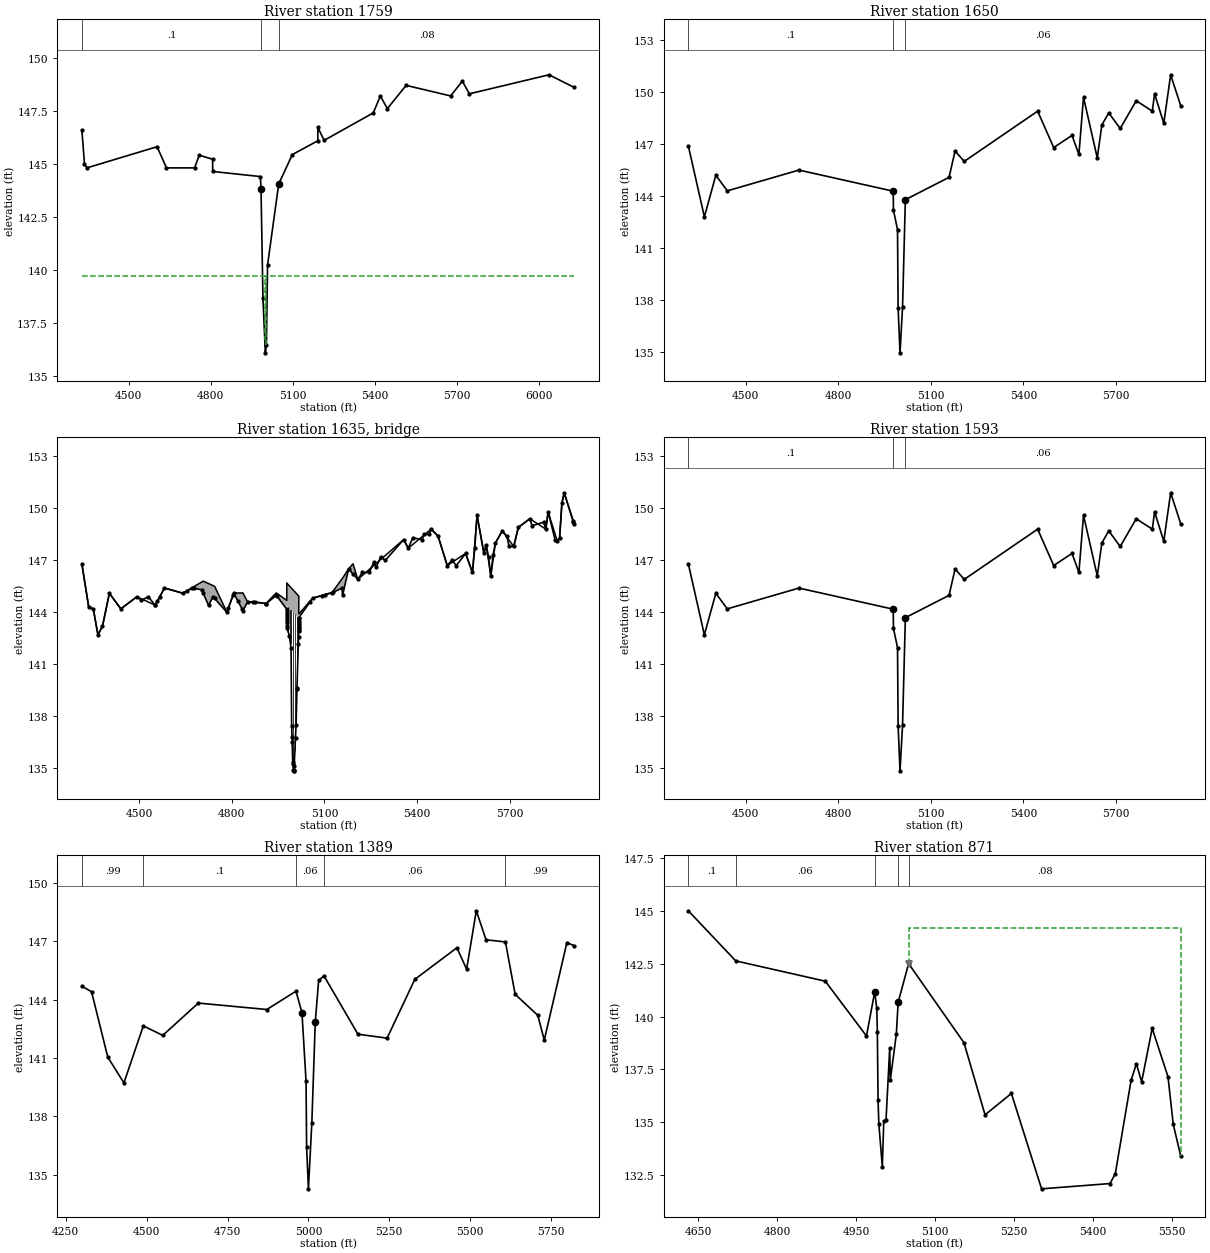
Type RM Length L Ch R = 1 ,1759    ,298.6,109,98
BEGIN DESCRIPTION:
K150-00-00-S1_UNKNOWN RD - US - XS2
END DESCRIPTION:
XS GIS Cut Line= 2
     3007724.355    13909758.136     3007807.064     13907958.45
#Sta/Elev= 30
 4328.61  146.62 4338.18  145.02 4346.75  144.82  4603.9  145.82 4638.19  144.82
 4741.05  144.82 4758.19  145.42 4806.96  145.23 4807.39  144.65 4981.83  144.41
 4984.14  143.81 4991.17  138.66    5000  136.08 5003.86  136.47 5008.06  140.23
 5049.03  144.08 5049.89  144.09 5098.75  145.45 5191.83   146.1 5192.09  146.73
 5214.98  146.12 5394.98  147.42  5420.7  148.22 5446.41  147.62 5514.98  148.72
 5677.85  148.22 5720.71  148.92 5746.42  148.32 6037.86  149.22 6130.43  148.62
#Mann= 3 ,-1 , 0
 4328.61      .1       0 4984.14     .06       0 5049.89     .08       0
#XS Ineff= 2 , 0
  715.02 4997.86   139.7 5003.86  715.02   139.7
Permanent Ineff=
       F       F
Bank Sta=4984.14,5049.03
Skew Angle= 31
Exp/Cntr=0.5,0.3

Type RM Length L Ch R = 1 ,1650    ,58.1,57,45.3
BEGIN DESCRIPTION:
K150-00-00-S0b_2nd WOOD BRIDGE-US - XS3
Golf course on right
END DESCRIPTION:
XS GIS Cut Line= 5
     3007824.602    13909774.254     3007941.727    13909558.502
     3007855.648    13909126.588     3007808.664    13908890.869
      3007836.81    13908222.106
#Sta/Elev= 30
    4314  146.91 4366.02  142.81 4403.17  145.21 4440.33  144.31 4672.49  145.51
    4978  144.29 4978.74  143.19  4991.9  142.07 4993.83  137.57    5000  134.96
 5008.24  137.62 5017.31   143.8 5158.88  145.09 5178.42  146.61 5208.15  146.01
 5445.96  148.91 5497.98  146.81 5557.43  147.51 5579.72  146.41 5594.59  149.71
 5639.17  146.21 5654.04  148.11 5676.33  148.81 5713.49  147.91 5765.51  149.51
 5817.53  148.91 5824.96  149.91 5854.69  148.21 5876.98  151.01 5909.83  149.21
#Mann= 3 ,-1 , 0
    4314      .1       0    4978     .06       0 5017.31     .06       0
Bank Sta=4978,5017.31
Skew Angle= 42
Exp/Cntr=0.5,0.3

Type RM Length L Ch R = 3 ,1635    ,,,
BEGIN DESCRIPTION:
WOOD BRIDGE #2
Structure ID: K150-00-00-S0b
END DESCRIPTION:
Bridge Culvert--1,0,-1,-1, 0
Deck Dist Width WeirC Skew NumUp NumDn MinLoCord MaxHiCord MaxSubmerge Is_Ogee
10,10,2.6,42, 60, 60, , , 0.95, 0, ,,,
    4314 4336.29 4351.16 4366.02 4380.88 4403.18 4440.33 4492.35 4551.81 4581.53
 4640.98  4707.2 4724.51 4744.35 4783.96 4806.26 4835.98 4850.85  4910.6 4944.04
 4978.07 4978.15 4978.38 4978.44 4978.52 5016.78 5016.87 5017.01 5017.09 5017.68
 5061.68 5125.07 5156.87 5158.88 5178.43 5192.77 5208.15 5356.78 5371.64 5445.96
 5468.25 5497.98 5557.43 5579.72 5594.59 5616.88 5624.31 5639.17 5654.04 5676.33
 5713.49 5728.35 5765.51 5817.53 5824.96 5854.69 5862.12 5869.55 5876.98 5909.83
   146.8   144.3   144.2   142.7   143.2   145.1   144.2   144.9  144.41  145.41
  145.11   145.8  145.66   145.5  144.01  145.11  145.12  144.61  144.51  145.12
  144.69  145.69  145.69  145.68  145.68  144.94  144.94  144.94  143.94  143.91
  144.82  145.15  145.93  145.97  146.51   146.8   145.9   148.2   147.7   148.8
   148.4   146.7   147.4   146.3   149.6   147.4   147.9   146.1     148   148.7
   147.8   148.9   149.4   148.8   149.8   148.1   148.3   150.3   150.9   149.1
   146.8   144.3   144.2   142.7   143.2   145.1   144.2   144.9   144.4   145.4
   145.1   145.1   144.4   144.8     144   145.1   144.1   144.6   144.5  144.98
  144.08  143.96  143.62  144.38  144.38  143.64   143.1  143.29  143.39   143.7
  144.81  145.13   145.4  144.98   146.5  146.21   145.9   148.2   147.7   148.8
   148.4   146.7   147.4   146.3   149.6   147.4   147.9   146.1     148   148.7
   147.8   148.9   149.4   148.8   149.8   148.1   148.3   150.3   150.9   149.1
    4314 4336.29 4351.16 4366.02 4380.88 4403.18 4440.33 4492.35 4551.81 4581.53
 4640.98  4707.2 4724.51 4744.35 4783.96 4806.26 4835.98 4850.85  4910.6 4944.04
 4978.07 4978.15 4978.38 4978.44 4978.52 5016.78 5016.87 5017.01 5017.09 5017.68
 5061.68 5125.07 5156.87 5158.88 5178.43 5192.77 5208.15 5356.78 5371.64 5445.96
 5468.25 5497.98 5557.43 5579.72 5594.59 5616.88 5624.31 5639.17 5654.04 5676.33
 5713.49 5728.35 5765.51 5817.53 5824.96 5854.69 5862.12 5869.55 5876.98 5909.83
   146.8   144.3   144.2   142.7   143.2   145.1   144.2   144.9  144.41  145.41
  145.11   145.8  145.66   145.5  144.01  145.11  145.12  144.61  144.51  145.12
  144.69  145.69  145.69  145.68  145.68  144.94  144.94  144.94  143.94  143.91
  144.82  145.15  145.93  145.97  146.51   146.8   145.9   148.2   147.7   148.8
   148.4   146.7   147.4   146.3   149.6   147.4   147.9   146.1     148   148.7
   147.8   148.9   149.4   148.8   149.8   148.1   148.3   150.3   150.9   149.1
  146.79  144.29  144.19  142.69  143.19  145.09  144.19  144.89  144.39  145.39
  145.09  145.09  144.39  144.79  143.99  145.09  144.09  144.59  144.49  144.97
  144.07  143.95  143.61  144.37  144.37  143.63  143.09  143.28  143.38  143.69
   144.8  145.12  145.39  144.97  146.49   146.2  145.89  148.19  147.69  148.79
  148.39  146.69  147.39  146.29  149.59  147.39  147.89  146.09  147.99  148.69
  147.79  148.89  149.39  148.79  149.79  148.09  148.29  150.29  150.89  149.09
Pier Skew, UpSta & Num, DnSta & Num=  ,4982.457, 2 ,4982.457, 2 , 0 , 0 , 0 ,,
      .8      .8
  141.86  145.28
      .8      .8
  141.85  145.27
Pier Skew, UpSta & Num, DnSta & Num=  ,4989.963, 2 ,4989.963, 2 , 0 , 0 , 0 ,,
      .8      .8
  141.17  145.09
      .8      .8
  141.16  145.08
Pier Skew, UpSta & Num, DnSta & Num=  ,4997.766, 2 ,4997.766, 2 , 0 , 0 , 0 ,,
      .8      .8
  134.21  144.88
      .8      .8
   134.2  144.87
Pier Skew, UpSta & Num, DnSta & Num=  ,5004.454, 2 ,5004.454, 2 , 0 , 0 , 0 ,,
      .8      .8
  134.94  144.79
      .8      .8
  134.93  144.78
Pier Skew, UpSta & Num, DnSta & Num=  ,5011.736, 2 ,5011.736, 2 , 0 , 0 , 0 ,,
      .8      .8
  138.87  144.71
      .8      .8
  138.86   144.7
BR Coef= 1 , 0 , 1 ,1.25, 0 ,,,0.8,-1,2,1,
WSPro=,,,, 1 ,,,, 0 ,,,, 0 ,,,,-1 ,-1 ,-1 , 0 , 0 , 0 , 0 , 0
BR U #Sta/Elev= 131
    4314   146.8 4336.29   144.3 4351.16   144.2 4366.02   142.7 4380.88   143.2
 4403.17   145.1 4440.33   144.2 4492.35   144.9 4507.21   144.7 4529.51   144.9
 4551.14  144.41 4551.81   144.4 4558.57  144.63    4566  144.88 4581.53   145.4
 4640.98   145.1 4655.18  145.24 4672.49   145.4 4677.47  145.38 4702.22   145.3
  4707.2   145.1 4724.51   144.4 4739.38   144.9 4744.35   144.8 4783.96     144
 4788.94  144.25 4803.81  144.98 4806.26   145.1 4818.67  144.68 4833.53  144.18
 4835.98   144.1 4850.85   144.6 4868.98  144.61 4873.59  144.61  4910.6   144.5
 4911.34   144.5 4944.04  144.98  4945.3  144.95    4978  144.18 4978.07  144.08
 4978.15  143.96 4978.23  143.84  4978.3  143.74 4978.38  143.62 4978.44  143.52
 4978.52  143.41 4978.67  143.19 4978.74  143.08 4986.32  142.66  4991.9  141.96
 4993.83  137.46 4995.02  136.83 4995.54  136.54 4997.32  135.36 4997.92  135.24
 4999.77  134.87    5000  134.85 5000.22  134.85 5001.56  134.89 5001.93  135.12
 5006.31  136.73 5008.24  137.51 5010.85  139.58 5011.07  139.66 5015.53  142.15
 5016.49   142.6 5016.72   142.9 5016.78  142.99 5016.87   143.1 5016.93  143.18
 5017.01  143.29 5017.09  143.39 5017.17   143.5 5017.31  143.69 5017.68   143.7
 5054.32  144.62 5061.68  144.81 5091.77  144.96 5101.06     145 5125.07  145.13
 5128.26  145.15 5156.87   145.4 5158.88  144.98 5178.42   146.5 5192.77  146.21
 5208.15   145.9 5223.01   146.3 5245.31   146.3 5260.17   146.9  5267.6   146.6
 5282.46   147.2 5297.33     147 5356.78   148.2 5371.64   147.7  5386.5   148.3
 5416.23   148.2 5423.66   148.5 5438.52   148.5 5445.96   148.8 5468.25   148.4
 5497.98   146.7 5512.84     147  5527.7   146.7 5557.43   147.4 5579.72   146.3
 5587.15   147.7 5594.59   149.6 5616.88   147.4 5624.31   147.9 5631.74   147.2
 5639.17   146.1 5646.61   147.3 5654.04     148 5676.33   148.7 5691.19   148.4
 5698.63   147.8 5713.49   147.8 5728.35   148.9 5765.51   149.4 5772.94     149
  5810.1   149.2 5817.53   148.8 5824.96   149.8 5847.25   148.2 5854.69   148.1
 5862.12   148.3 5869.55   150.3 5876.98   150.9 5905.52  149.27 5906.71   149.2
 5909.83   149.1
BR U #Mann= 3
    4314      .1    4978     .06 5017.31     .06
BR U Banks=4978,5017.31
BR D #Sta/Elev= 131
    4314  146.79 4336.29  144.29 4351.16  144.19 4366.02  142.69 4380.88  143.19
 4403.17  145.09 4440.33  144.19 4492.35  144.89 4507.21  144.69 4529.51  144.89
 4551.14   144.4 4551.81  144.39 4558.57  144.62    4566  144.87 4581.53  145.39
 4640.98  145.09 4655.18  145.23 4672.49  145.39 4677.47  145.37 4702.22  145.29
  4707.2  145.09 4724.51  144.39 4739.38  144.89 4744.35  144.79 4783.96  143.99
 4788.94  144.24 4803.81  144.97 4806.26  145.09 4818.67  144.67 4833.53  144.17
 4835.98  144.09 4850.85  144.59 4868.98   144.6 4873.59   144.6  4910.6  144.49
 4911.34  144.49 4944.04  144.97  4945.3  144.94    4978  144.17 4978.07  144.07
 4978.15  143.95 4978.23  143.83  4978.3  143.73 4978.38  143.61 4978.44  143.51
 4978.52   143.4 4978.67  143.18 4978.74  143.07 4986.32  142.65  4991.9  141.95
 4993.83  137.45 4995.02  136.82 4995.54  136.53 4997.32  135.35 4997.92  135.23
 4999.77  134.86    5000  134.84 5000.22  134.84 5001.56  134.88 5001.93  135.11
 5006.31  136.72 5008.24   137.5 5010.85  139.57 5011.07  139.65 5015.53  142.14
 5016.49  142.59 5016.72  142.89 5016.78  142.98 5016.87  143.09 5016.93  143.17
 5017.01  143.28 5017.09  143.38 5017.17  143.49 5017.31  143.68 5017.68  143.69
 5054.32  144.61 5061.68   144.8 5091.77  144.95 5101.06  144.99 5125.07  145.12
 5128.26  145.14 5156.87  145.39 5158.88  144.97 5178.42  146.49 5192.77   146.2
 5208.15  145.89 5223.01  146.29 5245.31  146.29 5260.17  146.89  5267.6  146.59
 5282.46  147.19 5297.33  146.99 5356.78  148.19 5371.64  147.69  5386.5  148.29
 5416.23  148.19 5423.66  148.49 5438.52  148.49 5445.96  148.79 5468.25  148.39
 5497.98  146.69 5512.84  146.99  5527.7  146.69 5557.43  147.39 5579.72  146.29
 5587.15  147.69 5594.59  149.59 5616.88  147.39 5624.31  147.89 5631.74  147.19
 5639.17  146.09 5646.61  147.29 5654.04  147.99 5676.33  148.69 5691.19  148.39
 5698.63  147.79 5713.49  147.79 5728.35  148.89 5765.51  149.39 5772.94  148.99
  5810.1  149.19 5817.53  148.79 5824.96  149.79 5847.25  148.19 5854.69  148.09
 5862.12  148.29 5869.55  150.29 5876.98  150.89 5905.52  149.26 5906.71  149.19
 5909.83  149.09
BR D #Mann= 3
    4314      .1    4978     .06 5017.31     .06
BR D Banks=4978,5017.31
BC Design=,, 0 ,, 0 ,,,,,,
BC HTab Sub Flow Curves= 50
BC HTab Sub Flow Pts= 30
BC HTab HWMax=151
BC HTab MaxFlow=2800

Type RM Length L Ch R = 1 ,1593    ,100,204,207.98
BEGIN DESCRIPTION:
K150-00-00-S0b_2nd WOOD BRIDGE-DS - XS2
END DESCRIPTION:
XS GIS Cut Line= 5
     3007864.517     13909805.97     3007985.901    13909582.369
     3007901.562    13909159.204     3007851.888    13908909.997
     3007879.465    13908254.972
#Sta/Elev= 30
    4314  146.76 4366.02  142.66 4403.17  145.06 4440.33  144.16 4672.49  145.36
    4978  144.14 4978.74  143.04  4991.9  141.92 4993.83  137.42    5000  134.81
 5008.24  137.47 5017.31  143.65 5158.88  144.94 5178.42  146.46 5208.15  145.86
 5445.96  148.76 5497.98  146.66 5557.43  147.36 5579.72  146.26 5594.59  149.56
 5639.17  146.06 5654.04  147.96 5676.33  148.66 5713.49  147.76 5765.51  149.36
 5817.53  148.76 5824.96  149.76 5854.69  148.06 5876.98  150.86 5909.83  149.06
#Mann= 3 ,-1 , 0
    4314      .1       0    4978     .06       0 5017.31     .06       0
Bank Sta=4978,5017.31
Skew Angle= 42
Exp/Cntr=0.5,0.3

Type RM Length L Ch R = 1 ,1389    ,261.5,518,543.85
BEGIN DESCRIPTION:
K150-00-00-S0b_2nd WOOD BRIDGE-DS - XS1
END DESCRIPTION:
XS GIS Cut Line= 6
      3007833.29      13909967.9       3008034.1     13909608.45
      3007979.56     13909364.26       3008032.8     13909296.35
      3007978.32     13909094.05      3007979.39     13908531.24
#Sta/Elev= 30
 4299.76  144.69 4329.76   144.4 4379.76  141.05 4429.76  139.72 4489.76  142.65
 4549.76  142.16 4659.76  143.82 4871.46  143.49 4961.66  144.43 4980.09  143.32
 4992.67  139.81 4994.42  136.44    5000  134.28  5010.6  137.68 5021.17  142.84
 5031.66  144.98 5047.96  145.22 5153.16  142.22 5243.16  142.02 5328.96  145.04
 5458.96  146.66 5488.96  145.56 5518.96  148.56 5548.96  147.07 5608.96  146.96
 5638.96  144.27 5708.96  143.19 5728.96  141.92 5798.96  146.93 5821.86  146.76
#Mann= 5 ,-1 , 0
 4299.76     .99       0 4489.76      .1       0 4961.66     .06       0
 5047.96     .06       0 5608.96     .99       0
Bank Sta=4980.09,5021.17
Exp/Cntr=0.3,0.1

Type RM Length L Ch R = 1 ,871     ,61,122,126.87
BEGIN DESCRIPTION:
K150-00-00-S0a_1st WOOD BRIDGE-US - XS4
***Note:  K150-00-00 is a perched stream DS of Unknown RD.  Flow spills from the right overbank to the golf course / unstudied area south of K150-00-00 at this section.
END DESCRIPTION:
XS GIS Cut Line= 5
     3007971.973    13909965.799     3008122.633    13909934.213
     3008192.514    13909830.457     3008240.448    13909755.237
     3008552.527    13909282.388
#Sta/Elev= 30
 4631.73     145 4721.73  142.63 4891.73  141.67 4969.93  139.08 4985.55  141.16
 4989.51  140.39  4990.6  139.25 4991.89  136.07 4993.43  134.91    5000   132.9
 5002.81  135.06 5007.05   135.1 5014.07  138.51 5015.18  136.99 5026.63  139.17
 5030.06  140.67 5049.93   142.5 5155.03  138.76 5195.03  135.35 5245.03  136.36
 5302.33  131.85 5432.33   132.1 5442.33  132.57 5472.33  136.99 5482.33  137.76
 5492.33  136.91 5512.33  139.44 5542.33  137.15 5552.33   134.9 5566.63  133.39
#Mann= 5 ,-1 , 0
 4631.73      .1       0 4721.73     .06       0 4985.55     .06       0
 5030.06     .06       0 5049.93     .08       0
Levee=0,,,-1,5049.93,142.5,,Levee 6
#XS Ineff= 2 , 0
    -.57                 5049.99    -.57  144.18
Permanent Ineff=
       F       F
Bank Sta=4985.55,5030.06
Exp/Cntr=0.5,0.3

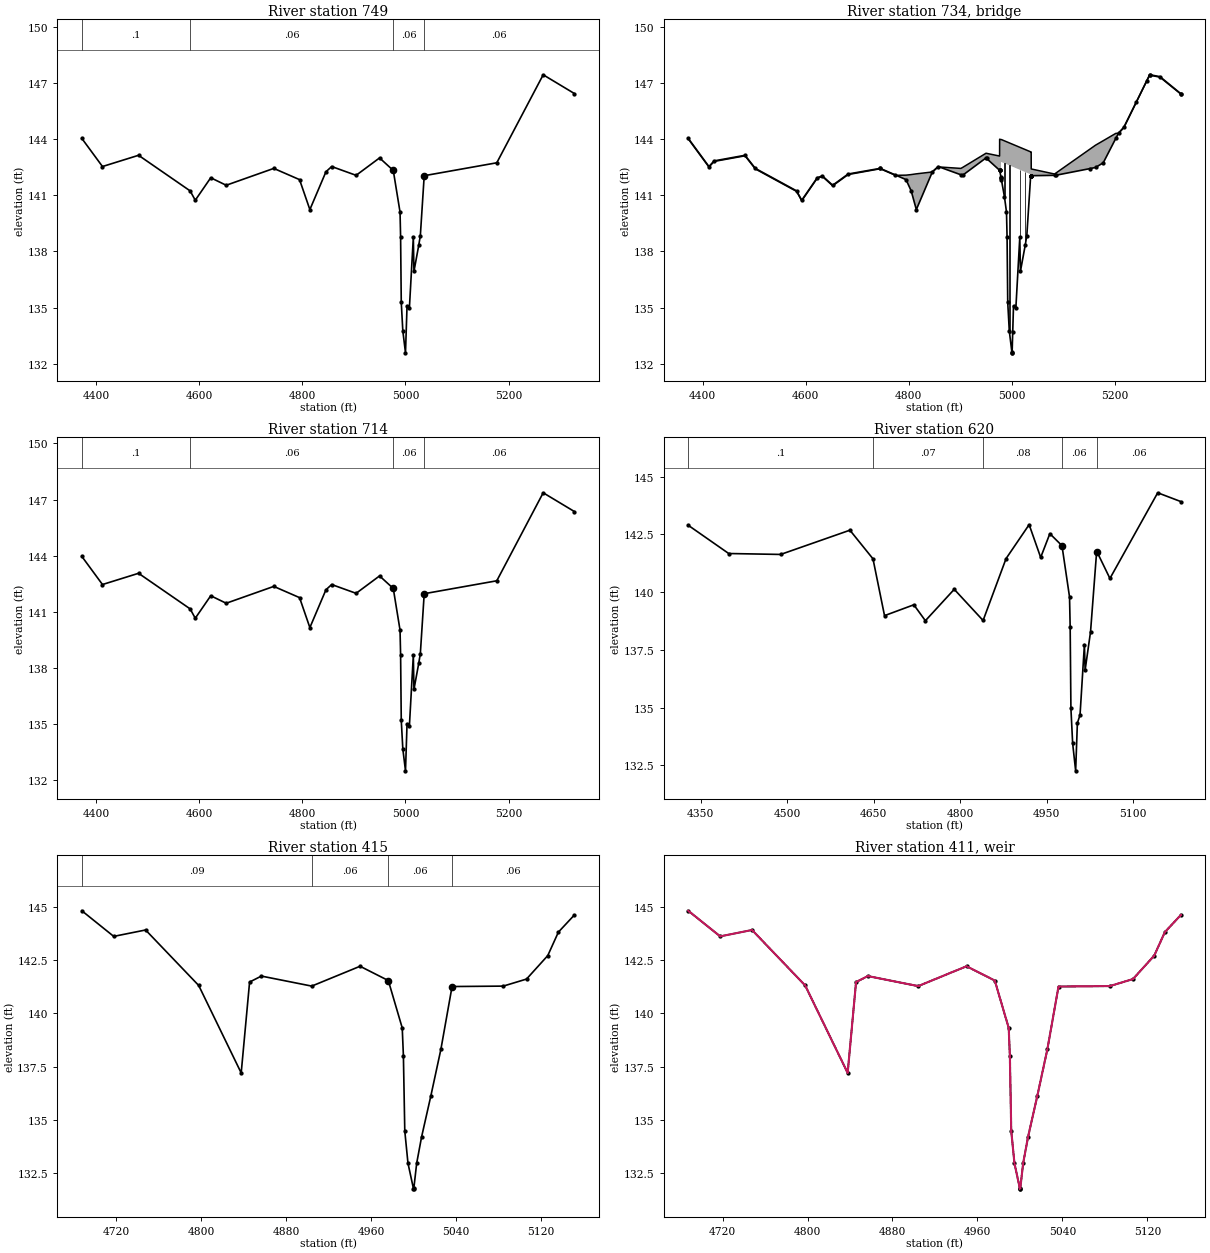
Type RM Length L Ch R = 1 ,749     ,35.6,35,34.5
BEGIN DESCRIPTION:
K150-00-00-S0a_1st WOOD BRIDGE-US - XS3
Golf course on right
END DESCRIPTION:
XS GIS Cut Line= 5
      3007824.29     13910021.53      3008195.87     13909998.08
      3008280.56     13909898.62       3008412.1     13909719.88
      3008546.04     13909532.33
#Sta/Elev= 30
  4372.2  144.03  4412.2  142.53  4482.2  143.13  4582.2  141.23  4592.2  140.73
  4622.2  141.93  4652.2  141.53  4744.5  142.43  4794.5  141.83  4814.5  140.23
  4845.7  142.25  4856.8  142.53  4904.2  142.06  4949.7  142.99  4976.3  142.32
  4989.4   140.1  4990.5  138.79  4991.8  135.27  4994.8  133.76    5000  132.58
    5003  135.09  5007.6  134.99  5015.2  138.75  5016.4  136.93  5025.8  138.34
  5028.8  138.84  5036.3  142.04  5177.1  142.73  5267.1  147.43  5327.5  146.43
#Mann= 4 ,-1 , 0
  4372.2      .1       0  4582.2     .06       0  4976.3     .06       0
  5036.3     .06       0
Bank Sta=4976.3,5036.3
Exp/Cntr=0.5,0.3

Type RM Length L Ch R = 3 ,734     ,,,
BEGIN DESCRIPTION:
WOOD BRIDGE #1
Structure ID: K150-00-00-S0a
END DESCRIPTION:
Bridge Culvert--1,0,-1,-1, 0
Deck Dist Width WeirC Skew NumUp NumDn MinLoCord MaxHiCord MaxSubmerge Is_Ogee
10,10,2.6,0, 39, 39, , , 0.95, 0, ,,,
  4372.2  4412.2  4422.2  4482.2  4502.2  4582.2  4592.2  4622.2  4632.2  4652.2
  4682.2  4744.5  4773.9  4794.5  4804.5  4814.5  4845.7  4856.8  4900.9  4904.2
  4949.7 4975.99  4976.1 4978.71  4978.8  4979.5 5036.69  5036.8  5037.3 5037.41
  5082.6  5162.1  5177.1  5201.4  5207.1  5217.1  5267.1  5287.1  5327.5
     144   142.5   142.8   143.1   142.4   141.2   140.7   141.9     142   141.5
   142.1  142.41  142.06  142.07   142.1  142.14  142.24  142.51  142.43  142.48
  143.24  143.09  143.99  143.97  143.97  143.97  143.31   143.3   143.3   142.4
  142.13  143.67  143.91   144.3  144.31  144.61  147.41   147.3   146.4
     144   142.5   142.8   143.1   142.4   141.2   140.7   141.9     142   141.5
   142.1   142.4  142.05   141.8   141.2   140.2  142.22   142.5  142.06  142.03
  142.96   142.3   142.3  141.92  142.77  142.77  142.11  142.01  142.01  142.01
  142.03  142.45   142.7     144   144.3   144.6   147.4   147.3   146.4
  4372.2  4412.2  4422.2  4482.2  4502.2  4582.2  4592.2  4622.2  4632.2  4652.2
  4682.2  4744.5  4773.9  4794.5  4804.5  4814.5  4845.7  4856.8  4900.9  4904.2
  4949.7 4975.99  4976.1 4978.71  4978.8  4979.5 5036.69  5036.8  5037.3 5037.41
  5082.6  5162.1  5177.1  5201.4  5207.1  5217.1  5267.1  5287.1  5327.5
     144   142.5   142.8   143.1   142.4   141.2   140.7   141.9     142   141.5
   142.1  142.41  142.06  142.07   142.1  142.14  142.24  142.51  142.43  142.48
  143.24  143.09  143.99  143.97  143.97  143.97  143.31   143.3   143.3   142.4
  142.13  143.67  143.91   144.3  144.31  144.61  147.41   147.3   146.4
  143.99  142.49  142.79  143.09  142.39  141.19  140.69  141.89  141.99  141.49
  142.09  142.39  142.04  141.79  141.19  140.19  142.21  142.49  142.05  142.02
  142.95  142.29  142.29  141.91  142.76  142.76   142.1     142     142     142
  142.02  142.44  142.69  143.99  144.29  144.59  147.39  147.29  146.39
Pier Skew, UpSta & Num, DnSta & Num=  ,4985.4, 2 ,4985.4, 2 , 0 , 0 , 0 ,,
      .8      .8
  139.81   143.7
      .8      .8
   139.8  143.69
Pier Skew, UpSta & Num, DnSta & Num=  ,4995.3, 2 ,4995.3, 2 , 0 , 0 , 0 ,,
      .8      .8
  132.53  143.58
      .8      .8
  132.52  143.57
Pier Skew, UpSta & Num, DnSta & Num=  ,5015.2, 2 ,5015.2, 2 , 0 , 0 , 0 ,,
      .8      .8
  137.11  143.35
      .8      .8
   137.1  143.34
Pier Skew, UpSta & Num, DnSta & Num=  ,5025.8, 2 ,5025.8, 2 , 0 , 0 , 0 ,,
      .8      .8
  137.25  143.23
      .8      .8
  137.24  143.22
BR Coef= 1 , 0 , 0 ,1.25, 0 ,,,0.8,-1,2,1,
WSPro=,,,, 1 ,,,, 0 ,,,, 0 ,,,,-1 ,-1 ,-1 , 0 , 0 , 0 , 0 , 0
BR U #Sta/Elev= 69
  4372.2  144.03  4412.2  142.53  4422.2  142.83  4482.2  143.13  4502.2  142.43
  4582.2  141.23  4592.2  140.73  4622.2  141.93  4632.2  142.03  4652.2  141.53
  4682.2  142.13  4744.2  142.43  4744.5  142.43  4773.9  142.08  4794.5  141.83
  4804.5  141.23  4814.5  140.23  4845.7  142.25  4856.8  142.53  4900.9  142.09
  4904.2  142.06  4949.7  142.99  4950.8  142.96 4975.99  142.33  4976.1  142.33
 4976.21  142.32  4976.3  142.32 4978.71  141.95  4978.8  141.94  4978.9  141.92
  4979.5  141.83  4985.4  140.92  4989.4   140.1  4990.5  138.79  4991.8  135.27
  4994.8  133.76    5000  132.58  5000.2  132.59  5000.3   132.6  5001.5  133.71
    5003  135.09  5007.6  134.99  5015.2  138.75  5016.4  136.93  5025.8  138.34
  5028.8  138.84  5036.3  142.04  5036.6  142.04 5036.69  142.04  5036.8  142.04
 5037.19  142.04  5037.3  142.04 5037.41  142.04  5037.5  142.04  5082.6  142.06
  5084.5  142.06  5151.4  142.42  5162.1  142.48  5177.1  142.73  5201.4  144.03
  5207.1  144.33  5217.1  144.63  5241.4  145.99  5261.4  147.11  5267.1  147.43
  5267.7  147.43  5287.1  147.33  5327.1  146.43  5327.5  146.43
BR U #Mann= 4
  4372.2      .1  4582.2     .06  4976.3     .06  5036.3     .06
BR U Banks=4976.3,5036.3
BR D #Sta/Elev= 69
  4372.2  143.99  4412.2  142.49  4422.2  142.79  4482.2  143.09  4502.2  142.39
  4582.2  141.19  4592.2  140.69  4622.2  141.89  4632.2  141.99  4652.2  141.49
  4682.2  142.09  4744.2  142.39  4744.5  142.39  4773.9  142.04  4794.5  141.79
  4804.5  141.19  4814.5  140.19  4845.7  142.21  4856.8  142.49  4900.9  142.05
  4904.2  142.02  4949.7  142.95  4950.8  142.92 4975.99  142.29  4976.1  142.29
 4976.21  142.28  4976.3  142.28 4978.71  141.91  4978.8   141.9  4978.9  141.88
  4979.5  141.79  4985.4  140.88  4989.4  140.06  4990.5  138.75  4991.8  135.23
  4994.8  133.72    5000  132.54  5000.2  132.55  5000.3  132.56  5001.5  133.67
    5003  135.05  5007.6  134.95  5015.2  138.71  5016.4  136.89  5025.8   138.3
  5028.8   138.8  5036.3     142  5036.6     142 5036.69     142  5036.8     142
 5037.19     142  5037.3     142 5037.41     142  5037.5     142  5082.6  142.02
  5084.5  142.02  5151.4  142.38  5162.1  142.44  5177.1  142.69  5201.4  143.99
  5207.1  144.29  5217.1  144.59  5241.4  145.95  5261.4  147.07  5267.1  147.39
  5267.7  147.39  5287.1  147.29  5327.1  146.39  5327.5  146.39
BR D #Mann= 4
  4372.2      .1  4582.2     .06  4976.3     .06  5036.3     .06
BR D Banks=4976.3,5036.3
BC Design=,, 0 ,, 0 ,,,,,,
BC HTab Sub Flow Curves= 50
BC HTab Sub Flow Pts= 30
BC HTab HWMax=150
BC HTab MaxFlow=2800

Type RM Length L Ch R = 1 ,714     ,94.9,94,85.91
BEGIN DESCRIPTION:
K150-00-00-S0a_1st WOOD BRIDGE-DS - XS2
END DESCRIPTION:
XS GIS Cut Line= 6
     3007863.297    13910045.219     3008217.701    13910022.862
     3008308.349    13909916.386     3008387.049     13909809.44
     3008440.392    13909736.959     3008578.174    13909544.044
#Sta/Elev= 30
  4372.2  143.96  4412.2  142.46  4482.2  143.06  4582.2  141.16  4592.2  140.66
  4622.2  141.86  4652.2  141.46  4744.5  142.36  4794.5  141.76  4814.5  140.16
  4845.7  142.18  4856.8  142.46  4904.2  141.99  4949.7  142.92  4976.3  142.25
  4989.4  140.03  4990.5  138.72  4991.8   135.2  4994.8  133.69    5000  132.51
    5003  135.02  5007.6  134.92  5015.2  138.68  5016.4  136.86  5025.8  138.27
  5028.8  138.77  5036.3  141.97  5177.1  142.66  5267.1  147.36  5327.5  146.36
#Mann= 4 ,-1 , 0
  4372.2      .1       0  4582.2     .06       0  4976.3     .06       0
  5036.3     .06       0
Bank Sta=4976.3,5036.3
Exp/Cntr=0.5,0.3

Type RM Length L Ch R = 1 ,620     ,186,205,168.39
BEGIN DESCRIPTION:
K150-00-00-S0a_1st WOOD BRIDGE-DS - XS1
END DESCRIPTION:
XS GIS Cut Line= 5
      3007916.36    13910085.444     3008297.091    13910061.407
     3008387.729    13909954.951     3008476.527    13909834.296
     3008583.183    13909686.606
#Sta/Elev= 30
  4328.8  142.89  4398.8  141.67  4488.8  141.63  4608.8  142.68  4648.8  141.44
  4668.8  138.98  4719.6  139.45  4739.6  138.76  4789.6  140.12  4839.6  138.77
  4879.4  141.45  4919.4  142.92  4939.4   141.5  4955.3  142.53  4976.3  142.01
  4989.4  139.79  4990.5  138.48  4991.8  134.96  4994.8  133.45    5000  132.26
    5003  134.33  5007.6  134.68  5015.2  137.73  5016.4  136.62  5025.8  138.28
  5036.3  141.73 5037.25  141.73  5059.4  140.59  5142.2   144.3  5182.2  143.92
#Mann= 5 ,-1 , 0
  4328.8      .1       0  4648.8     .07       0  4839.6     .08       0
  4976.3     .06       0  5036.3     .06       0
Bank Sta=4976.3,5037.25
Exp/Cntr=0.3,0.1

Type RM Length L Ch R = 1 ,415     ,24,24,24
BEGIN DESCRIPTION:
Cross Section K150-00-00_Interpolated XS1
END DESCRIPTION:
XS GIS Cut Line= 3
     3008440.512    13910090.983     3008676.151    13909796.081
     3008652.504    13909713.332
#Sta/Elev= 27
  4687.8   144.8  4717.8   143.6  4747.8   143.9  4797.8   141.3  4837.8   137.2
  4845.7  141.46  4856.8  141.74  4904.2  141.27  4949.7   142.2  4976.3  141.53
  4989.4  139.31  4990.5     138  4991.8  134.48  4994.8  132.97    5000  131.77
  5000.2  131.78  5000.3  131.79    5003  132.97  5007.6   134.2  5016.4  136.14
  5025.8  138.31  5036.3  141.25  5084.5  141.27  5106.4   141.6  5126.4   142.7
  5136.4   143.8  5151.4   144.6
#Mann= 4 ,-1 , 0
  4687.8     .09       0  4904.2     .06       0  4976.3     .06       0
  5036.3     .06       0
Bank Sta=4976.3,5036.3
Exp/Cntr=0.5,0.3

Type RM Length L Ch R = 5 ,411     ,,,
IW Pilot Flow=0
#Inline Weir SE= 27
  4687.8   144.8  4717.8   143.6  4747.8   143.9  4797.8   141.3  4837.8   137.2
  4845.7  141.46  4856.8  141.74  4904.2  141.27  4949.7   142.2  4976.3  141.53
  4989.4  139.31  4990.5     138  4991.8  134.48  4994.8  132.97    5000  131.77
  5000.2  131.78  5000.3  131.79    5003  132.97  5007.6   134.2  5016.4  136.14
  5025.8  138.31  5036.3  141.25  5084.5  141.27  5106.4   141.6  5126.4   142.7
  5136.4   143.8  5151.4   144.6
IW Dist,WD,Coef,Skew,MaxSub,Min_El,Is_Ogee,SpillHt,DesHd
4,2,2.6,0,0.95,, 0 ,,,0,0,

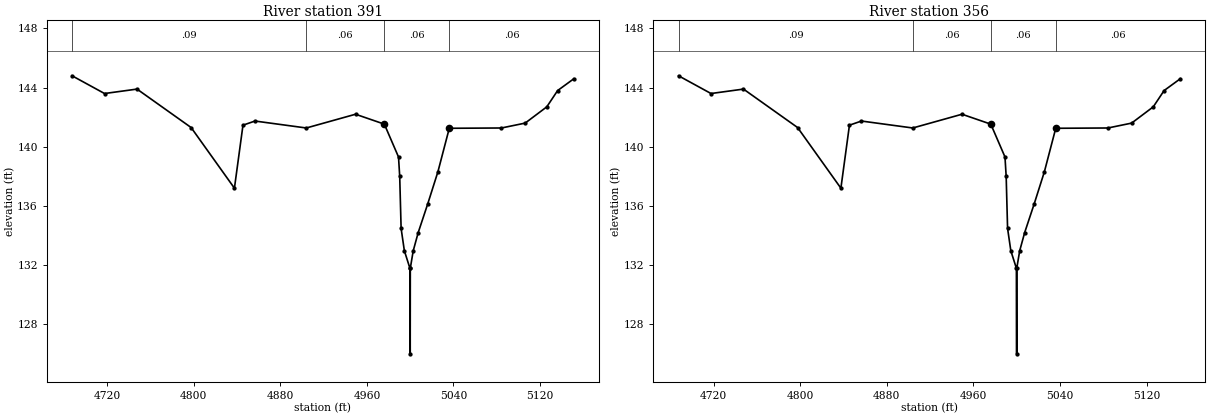
Type RM Length L Ch R = 1 ,391     ,35,35,35
BEGIN DESCRIPTION:
Cross Section K150-00-00_Interpolated XS1
END DESCRIPTION:
XS GIS Cut Line= 4
     3008491.675    13910108.861     3008662.603    13909847.425
     3008693.739    13909799.791     3008676.871    13909707.033
#Sta/Elev= 27
  4687.6   144.8  4717.6   143.6  4747.6   143.9  4797.6   141.3  4837.6   137.2
  4845.5  141.46  4856.6  141.74    4904  141.27  4949.5   142.2  4976.1  141.53
  4989.2  139.31  4990.3     138  4991.6  134.48  4994.6  132.97  4999.8  131.77
    5000     126  5000.1  131.79  5002.8  132.97  5007.4   134.2  5016.2  136.14
  5025.6  138.31  5036.1  141.25  5084.3  141.27  5106.2   141.6  5126.2   142.7
  5136.2   143.8  5151.2   144.6
#Mann= 4 ,-1 , 0
  4687.6     .09       0    4904     .06       0  4976.1     .06       0
  5036.1     .06       0
Bank Sta=4976.1,5036.1
Exp/Cntr=0.5,0.3

Type RM Length L Ch R = 1 ,356     ,356,356,356
BEGIN DESCRIPTION:
Cross Section K150-00-00_Interpolated XS1
END DESCRIPTION:
XS GIS Cut Line= 4
     3008557.987    13910087.993     3008712.956    13909816.789
     3008721.455    13909801.921     3008694.309    13909670.638
#Sta/Elev= 27
  4687.6   144.8  4717.6   143.6  4747.6   143.9  4797.6   141.3  4837.6   137.2
  4845.5  141.46  4856.6  141.74    4904  141.27  4949.5   142.2  4976.1  141.53
  4989.2  139.31  4990.3     138  4991.6  134.48  4994.6  132.97  4999.8  131.77
    5000     126  5000.1  131.79  5002.8  132.97  5007.4   134.2  5016.2  136.14
  5025.6  138.31  5036.1  141.25  5084.3  141.27  5106.2   141.6  5126.2   142.7
  5136.2   143.8  5151.2   144.6
#Mann= 4 ,-1 , 0
  4687.6     .09       0    4904     .06       0  4976.1     .06       0
  5036.1     .06       0
Bank Sta=4976.1,5036.1
Exp/Cntr=0.3,0.1

Chan Stop Cuts=-1
Use User Specified Reach Order=0
User Specified Reach Order=K150-01-00      ,DS_DIVERSION